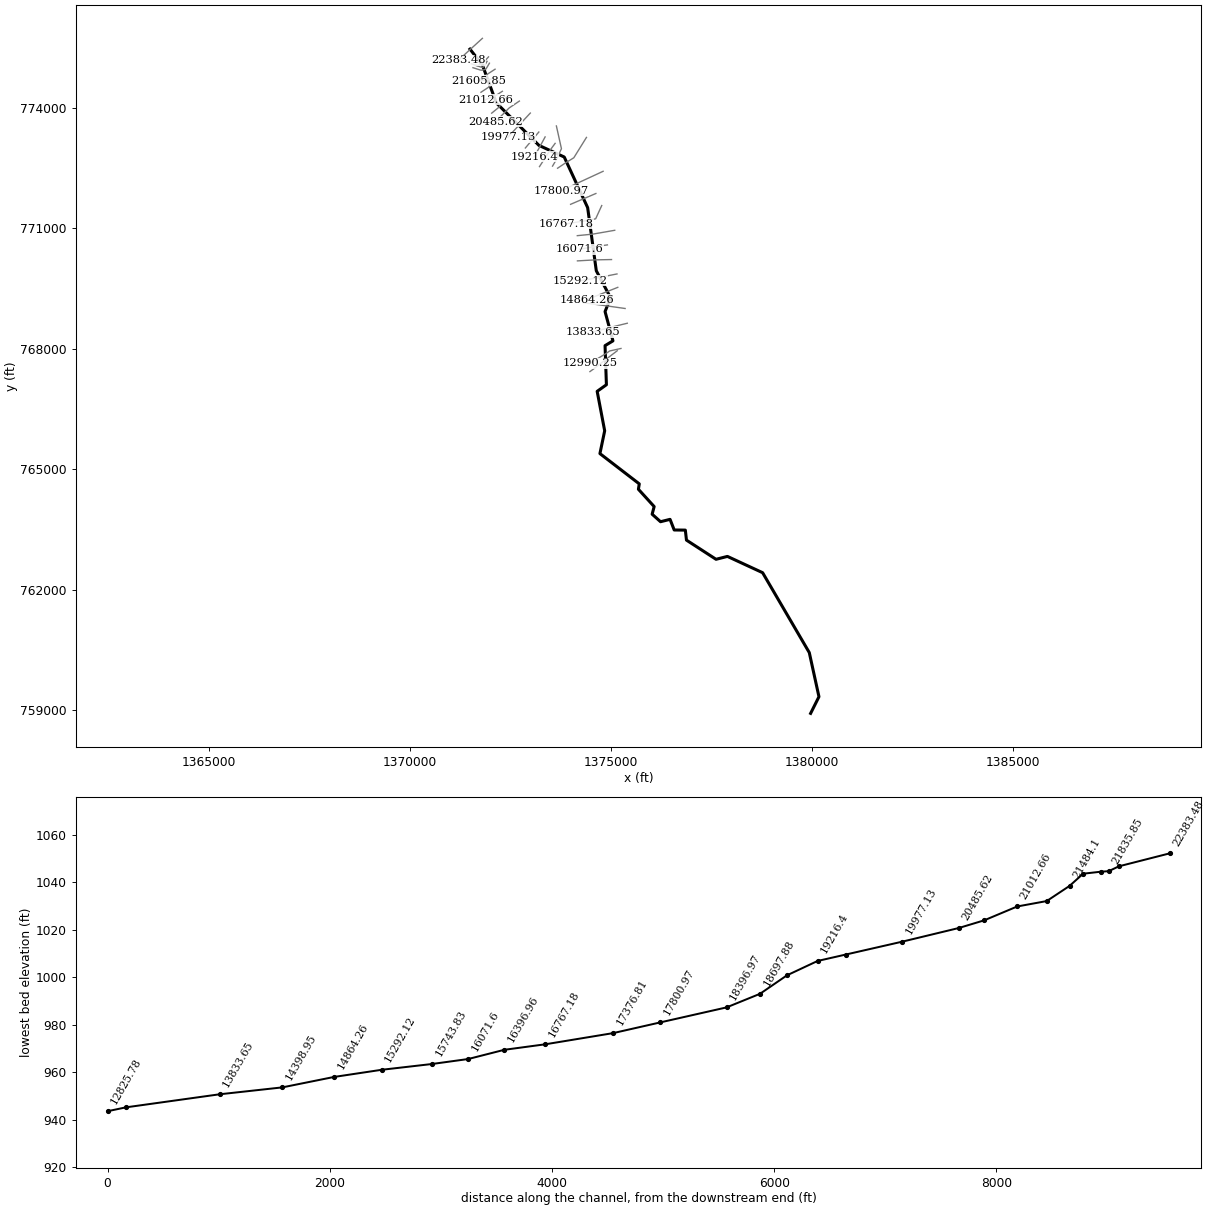
--- BigBranch.prj (project) ---

Proj Title=BigBranch
Current Plan=p01
Default Exp/Contr=0.3,0.1
English Units
Geom File=g01
Flow File=f01
Plan File=p01
Y Axis Title=Elevation
X Axis Title(PF)=Main Channel Distance
X Axis Title(XS)=Station
BEGIN DESCRIPTION:
END DESCRIPTION:
DSS Export Rating Curves= 0
DSS Export Rating Curve Sorted= 0
DSS Export Volume Flow Curves= 0
DXF OffsetX= 0
DXF OffsetY= 0
DXF ScaleX= 1
DXF ScaleY= 10

--- BigBranch.p01 (plan) ---

Plan Title=LD Study_100 YR
Program Version=3.12
Short Identifier=Plan 01
Geom File=g01
Flow File=f01
Subcritical Flow
K Sum by GR= 0
Std Step Tol= 0.01
Critical Tol= 0.01
Num of Std Step Trials= 20
Max Error Tol= 0.3
Flow Tol Ratio= 0.001
Split Flow NTrial= 30
Split Flow Tol= 0.02
Split Flow Ratio= 0.02
Log Output Level= 0
Friction Slope Method= 1
Unsteady Friction Slope Method= 2
Unsteady Bridges Friction Slope Method= 1
Calc Critical at every XS
Parabolic Critical Depth
Global Vel Dist= 0 , 0 , 0
Global Log Level= 0
CheckData=True
Encroach Param=-1 ,10,10, 2
Encroach River=BigBranch
Encroach Reach=Main
Encroach Node=22383.48
       1  394.89   425.3
Encroach Node=21928.14
       1  213.24  259.55
Encroach Node=21835.85
       1     160   212.5
Encroach Node=21763.63
       1   218.8   259.5
Encroach Node=21605.85
       1     245     305
Encroach Node=21484.1
       1     225     265
Encroach Node=21278.29
       1     269   295.6
Encroach Node=21012.66
       1     228     255
Encroach Node=20715.8
       1     275     308
Encroach Node=20485.62
       1     341     373
Encroach Node=19977.13
       1     405     430
Encroach Node=19469.25
       1     220     250
Encroach Node=19216.4
       1  241.39  278.02
Encroach Node=18940.21
       1     185     210
Encroach Node=18697.88
       1  708.11  750.67
Encroach Node=18396.97
       1  813.88  845.55
Encroach Node=17800.97
       1   749.8  783.91
Encroach Node=17376.81
       1  311.95   344.5
Encroach Node=16767.18
       1     493     529
Encroach Node=16396.96
       1     541     566
Encroach Node=16071.6
       1     332     359
Encroach Node=15743.83
       1  376.09   419.1
Encroach Node=15292.12
       1  448.04  490.99
Encroach Node=14864.26
       1   250.5     315
Encroach Node=14398.95
       1  474.52  520.22
Encroach Node=13833.65
       1     430     489
Encroach Node=12990.25
       1  351.27     450
Encroach Node=12825.78
       1  319.34  362.67
Encroach Node=12746.13
       1     350     405
Encroach Node=12442.07
       1  505.19     550
Encroach Node=12034.87
       1     133  178.11
Encroach Node=11637.53
       1  335.57   382.8
Encroach Node=11216.31
       1  351.11  394.62
Encroach Node=10680.93
       1     200     258
Encroach Node=10060.59
       1     315  376.59
Encroach Node=9355.869
       1     400     458
Encroach Node=8676.243
       1  365.72     440
Encroach Node=8146.31
       1     228     285
Encroach Node=7674.886
       1   321.6  397.45
Encroach Node=7163.646
       1     555  626.39
Encroach Node=6570.493
       1     715  831.03
Encroach Node=6019.653
       1     375     600
Encroach Node=5834.838
       1   397.5   466.8
Encroach Node=5778.774
       1     400     470
Encroach Node=5337.685
       1     400     585
Encroach Node=4977.741
       1     395  526.02
Encroach Node=4480.163
       1  581.68  733.93
Encroach Node=4224.905
       1  324.93  460.38
Encroach Node=3686.454
       1  479.72  641.41
Encroach Node=2970.798
       1  414.54     613
Encroach Node=2383.477
       1  381.02  567.73
Encroach Node=1661.606
       1  422.04  633.64
Encroach Node=883.477
       1 1022.29  1249.5
Encroach Node=383.477
       1 1373.58 1449.91
Computation Interval=1HOUR
Output Interval=1HOUR
Run HTab= 0
Run UNet= 0
Run PostProcess= 0
UNET Theta= 1
UNET Theta Warmup= 1
UNET ZTol= 0.02
UNET ZSATol= 0.05
UNET MxIter= 20
UNET MaxInSteps= 0
UNET DtIC= 0
UNET DtMin= 0
UNET MaxCRTS= 20
UNET WFStab= 2
UNET SFStab= 1
UNET WFX= 1
UNET SFX= 1
UNET DSS MLevel= 4
UNET DZMax Abort= 100
UNET Convert EG Bridges=-1
UNET Use Existing IB Tables=-1
UNET Froude Reduction=False
UNET Froude Limit= 1
UNET Froude Power= 10
Instantaneous Interval=1HOUR
Write IC File= 0
Echo Input=False
Echo Output=False
Write Detailed= 0
Detailed Automatic Start=False, 10

--- BigBranch.f01 (steady flow) ---

Flow Title=BigBranch
Program Version=3.12
Number of Profiles= 2
Profile Names=P100yr,PF 2
River Rch & RM=BigBranch,Main            ,22383.48
     606     606
River Rch & RM=BigBranch,Main            ,21605.85
     660     660
River Rch & RM=BigBranch,Main            ,21278.29
     709     709
River Rch & RM=BigBranch,Main            ,20485.62
     761     761
River Rch & RM=BigBranch,Main            ,18940.21
     964     964
River Rch & RM=BigBranch,Main            ,18396.97
    1070    1070
River Rch & RM=BigBranch,Main            ,16396.96
    1220    1220
River Rch & RM=BigBranch,Main            ,16071.6
    1350    1350
River Rch & RM=BigBranch,Main            ,13833.65
    1480    1480
River Rch & RM=BigBranch,Main            ,11216.31
    1620    1620
River Rch & RM=BigBranch,Main            ,9355.869
    1780    1780
River Rch & RM=BigBranch,Main            ,6019.653
    1840    1840
River Rch & RM=BigBranch,Main            ,5337.685
    1990    1990
Boundary for River Rch & Prof#=BigBranch,Main            , 1
Up Type= 0
Dn Type= 3
Dn Slope=0.004255
DSS Import GetInterval= 0
DSS Import GetPeak= 0
DSS Import FillOption= 0

--- BigBranch.g01 (geometry) ---

Geom Title=BigBranch
Program Version=3.12

River Reach=BigBranch       ,Main
Reach XY= 30
  1371492.160118   775455.831018  1371802.498162   775058.501469
  1372148.630647   774116.999003  1373208.630394   773060.128596
  1373838.378101   772770.189129  1374421.251189   771510.689608
  1374636.381305    769939.38209  1374992.297276    769266.18114
   1374854.63257   768923.057999  1375051.129971   768193.560393
   1374854.63257   768075.059028  1374888.241419   767101.415455
  1374658.249835   766937.128783  1374845.248633   765955.129154
  1374726.874235   765387.689794  1375706.544686   764633.675503
  1375684.748404   764500.000585  1376076.751994   764068.941645
  1376026.879085   763878.809424  1376235.750522   763691.749198
  1376472.749168    763750.94048  1376575.628409    763485.99891
  1376853.001334   763482.877762  1376881.128571   763233.443651
  1377616.880749   762756.439875  1377900.500079   762828.189505
  1378776.634479   762422.882123  1379938.427589   760433.934773
  1380179.129451   759335.808833  1379971.630206   758920.998713

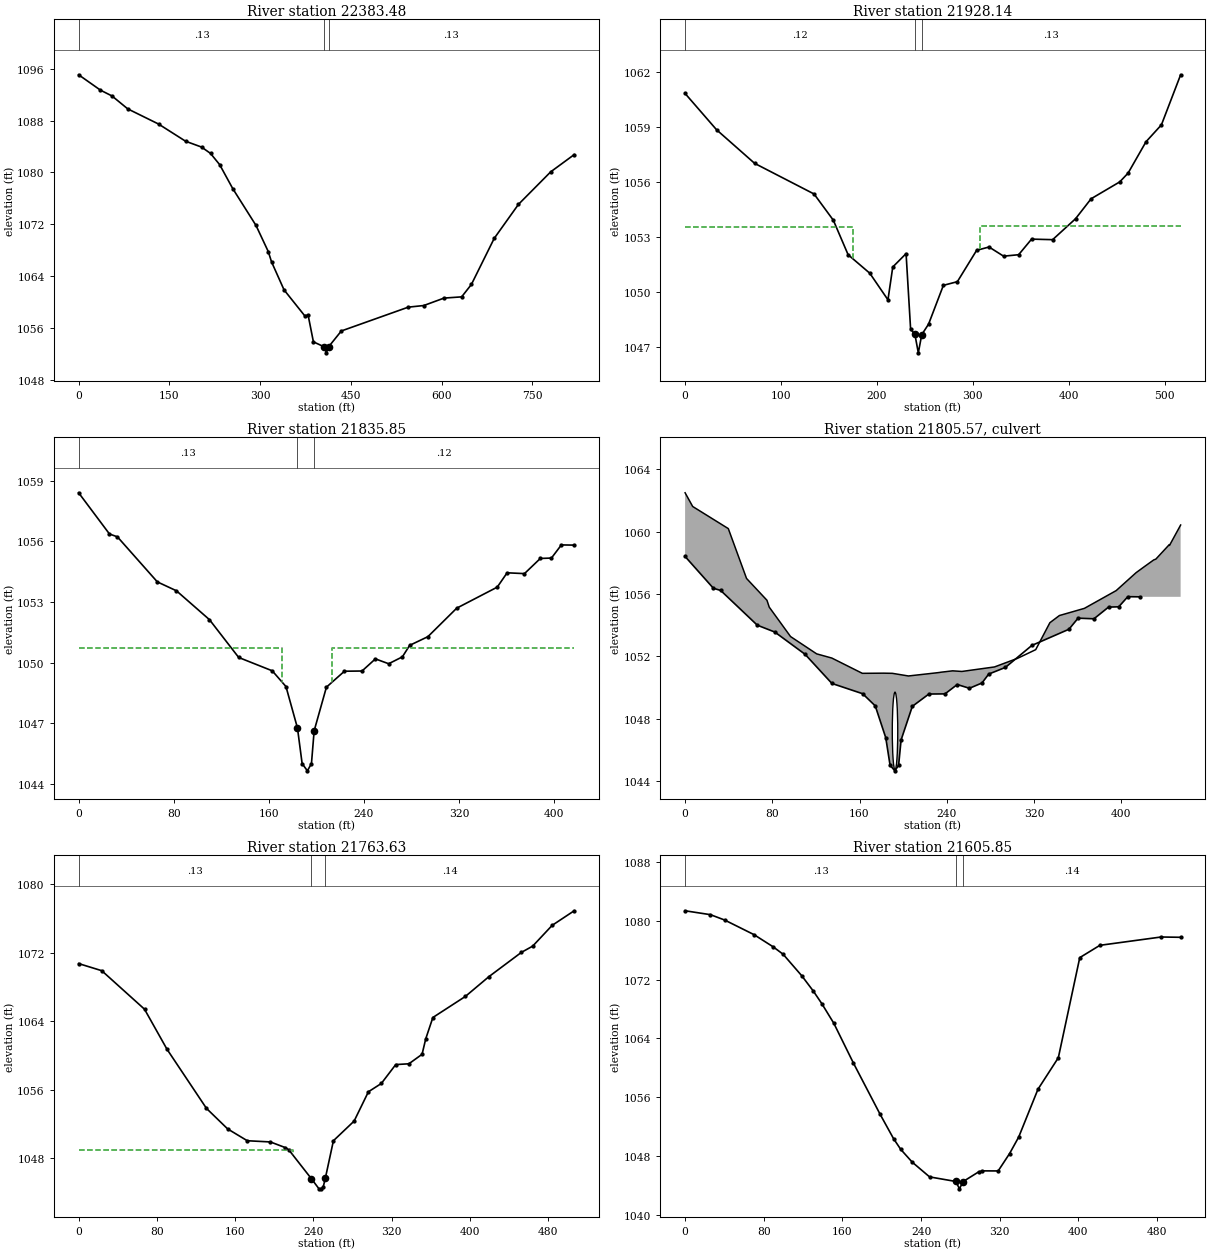
Type RM Length L Ch R = 1 ,22383.48,461.45,455.34,446.59
XS GIS Cut Line= 3
  1371801.561592   775724.279006   1371498.89603   775448.439984
  1371196.236529   775172.606502
#Sta/Elev= 30
       0  1095.1   36.13 1092.72   55.09 1091.83   81.19 1089.83  132.04 1087.49
  176.79 1084.83   203.1 1083.93  217.95 1082.95  233.09 1081.21  254.71 1077.51
  293.14 1071.82  313.41 1067.78  318.82 1066.19   339.5 1061.86  373.47 1057.88
  379.34 1057.93  388.03 1053.83  405.99 1053.05   409.5 1052.13  413.02 1053.05
  434.19 1055.51   544.8 1059.19   570.4 1059.44  603.84 1060.59  633.03 1060.78
  649.15  1062.7  686.85 1069.82  726.97 1075.08  780.21  1080.1     819 1082.76
#Mann= 3 , 0 , 0
       0     .13       0  405.99     .05       0  413.02     .13       0
Bank Sta=405.99,413.02
Exp/Cntr=0.3,0.1

Type RM Length L Ch R = 1 ,21928.14,98.26,92.29,77.98
XS GIS Cut Line= 5
  1371953.440939    775262.87694  1371819.934288   775115.519435
  1371781.222934   775092.557043  1371680.794195   775044.496341
  1371525.952343     775089.9602
#Sta/Elev= 30
       0 1060.84   32.85 1058.86    72.5 1057.03  134.45 1055.36  154.53 1053.93
  169.93 1052.05  192.54 1051.04  211.47 1049.59  216.48 1051.38  230.36 1052.11
  235.07    1048  239.57  1047.7  243.12  1046.7  246.68 1047.69  253.85 1048.27
  269.24 1050.38  283.83 1050.58  303.92 1052.29  316.84 1052.47  332.02 1051.97
   347.7 1052.05  361.19  1052.9  383.13 1052.87     407 1054.01  423.23  1055.1
  453.09 1056.02  461.81  1056.5  480.49 1058.21  496.54 1059.13  516.57 1061.86
#Mann= 3 , 0 , 0
       0     .12       0  239.57     .05       0  246.68     .13       0
#XS Ineff= 2 , 0
          174.83 1053.57  307.69         1053.61
Permanent Ineff=
       F       F
Bank Sta=239.57,246.68
Exp/Cntr=0.5,0.3

Type RM Length L Ch R = 1 ,21835.85,73.92,72.21,77.34
XS GIS Cut Line= 6
  1371917.279694    775152.48386  1371849.089458    775033.93316
  1371823.570612   775009.608719  1371790.931754   775004.103363
  1371767.586666   775008.116193  1371589.588487   775064.917935
#Sta/Elev= 30
       0 1058.41   25.95 1056.37   32.62 1056.23   66.22    1054   82.28 1053.56
  110.08 1052.13  134.67 1050.26  162.89  1049.6  174.44 1048.82   184.1 1046.77
  188.03 1045.01  192.44 1044.65  195.88 1045.01  198.14 1046.63  208.46 1048.79
  223.63 1049.58  238.43 1049.59  249.67 1050.19  260.84 1049.95  272.36 1050.29
  278.51 1050.86  293.85 1051.29  318.09  1052.7  352.16 1053.74  360.49 1054.45
  375.09 1054.41  388.43 1055.16  397.79 1055.18  406.13 1055.83   416.9 1055.82
#Mann= 3 , 0 , 0
       0     .13       0   184.1     .05       0  198.14     .12       0
#XS Ineff= 2 , 0
       0  171.49 1050.73  212.86       0 1050.75
Permanent Ineff=
       F       F
Bank Sta=184.1,198.14
Exp/Cntr=0.5,0.3

Type RM Length L Ch R = 2 ,21805.57,,,
BEGIN DESCRIPTION:
Culvert 37003-0064 (Matherson Road)
END DESCRIPTION:
Bridge Culvert--1,0,-1,-1, 0
Deck Dist Width WeirC Skew NumUp NumDn MinLoCord MaxHiCord MaxSubmerge Is_Ogee
17.78,25,2.6,0, 32, 32, 1050.75, , 0.95, 0, 0,0,,
       0    6.96   39.64   56.37    75.1   77.18   96.74  120.68  134.61  162.58
  182.13  190.15  204.87  230.39  233.87  234.58  245.47  253.89  283.83  304.89
  321.65  334.64  343.37  366.29  395.44   413.7  420.94  429.89  431.82  444.14
  444.35  454.59
  1062.5 1061.62  1060.2    1057  1055.6 1055.16 1053.27 1052.16 1051.89 1050.91
 1050.92 1050.91 1050.74 1050.94 1050.97 1050.98 1051.07 1051.03 1051.32 1051.87
 1052.43 1054.16 1054.62 1055.08 1056.22 1057.37 1057.74 1058.19 1058.24 1059.17
 1059.12 1060.43
                                                                                
                                                                                
                                                                                
                
       0    6.96   39.64   56.37    75.1   77.18   96.74  120.68  134.61  162.58
  182.13  190.15  204.87  230.39  233.87  234.58  245.47  253.89  283.83  304.89
  321.65  334.64  343.37  366.29  395.44   413.7  420.94  429.89  431.82  444.14
  444.35  454.59
  1062.5 1061.62  1060.2    1057  1055.6 1055.16 1053.27 1052.16 1051.89 1050.91
 1050.92 1050.91 1050.74 1050.94 1050.97 1050.98 1051.07 1051.03 1051.32 1051.87
 1052.43 1054.16 1054.62 1055.08 1056.22 1057.37 1057.74 1058.19 1058.24 1059.17
 1059.12 1060.43
                                                                                
                                                                                
                                                                                
                
BR Coef=-1 , 0 , 0 ,, 0 ,,,0.8,-1,,0,
WSPro=,,,, 1 ,,,, 0 ,,,, 0 ,,,,-1 ,-1 ,-1 , 0 , 0 , 0 , 0 , 0
Culvert=1,5,,35,0.024,0.9,1,2,3,1044.7,192.57,1044.68,247.46,Culvert #1  , 0 ,12.78
Culvert Bottom n=0.024
BC Design=,, 0 ,, 0 ,,,,,,

Type RM Length L Ch R = 1 ,21763.63,147.83,157.79,170.27
XS GIS Cut Line= 6
  1371975.976293   775105.746014  1371890.960867   774961.532049
  1371847.995726   774945.164351  1371794.969161   774930.702588
   1371752.40942    774934.40341  1371566.369534   774993.602599
#Sta/Elev= 30
       0 1070.74   23.63 1069.91   67.37 1065.41   90.38 1060.73  130.75 1053.82
  152.43 1051.42  172.49 1050.04  196.14  1049.9  211.11 1049.25  214.87 1048.99
  237.93 1045.62   245.7 1044.44  247.49 1044.42  250.02 1044.58  252.35 1045.68
  260.57 1050.04  281.76 1052.34  296.35 1055.76  309.57 1056.73  324.31 1058.94
  337.76 1059.03  351.24 1060.14  355.02 1061.96  362.29 1064.44  395.52  1066.9
  419.68 1069.22  452.84 1072.05  464.38 1072.78  484.32 1075.21   506.8 1076.91
#Mann= 3 , 0 , 0
       0     .13       0  237.93     .05       0  252.35     .14       0
#XS Ineff= 2 , 0
       0  218.78 1048.99  274.46       0    1049
Permanent Ineff=
       F       F
Bank Sta=237.93,252.35
Exp/Cntr=0.5,0.3

Type RM Length L Ch R = 1 ,21605.85,119,121.75,123
XS GIS Cut Line= 3
  1372116.931246   774956.358466  1371857.252385   774786.933243
  1371699.049131   774674.568247
#Sta/Elev= 30
       0 1081.33   25.83  1080.8   40.31 1080.07   70.11 1078.09   89.54 1076.44
   99.71 1075.43  118.73  1072.5  130.43 1070.43  139.04 1068.73  151.28 1066.06
  171.25 1060.65  198.43 1053.69  212.03  1050.4  219.36 1048.94  231.07  1047.2
  248.73  1045.2  275.41 1044.58  279.12 1043.58  282.72 1044.56  298.58 1045.88
  302.38 1046.02  318.48 1046.01  330.06 1048.36  339.34  1050.6  358.97  1057.1
  379.69 1061.38  401.49 1074.97  421.95 1076.64  484.23 1077.77  504.11 1077.73
#Mann= 3 , 0 , 0
       0     .13       0  275.41     .05       0  282.72     .14       0
Bank Sta=275.41,282.72
Exp/Cntr=0.3,0.1

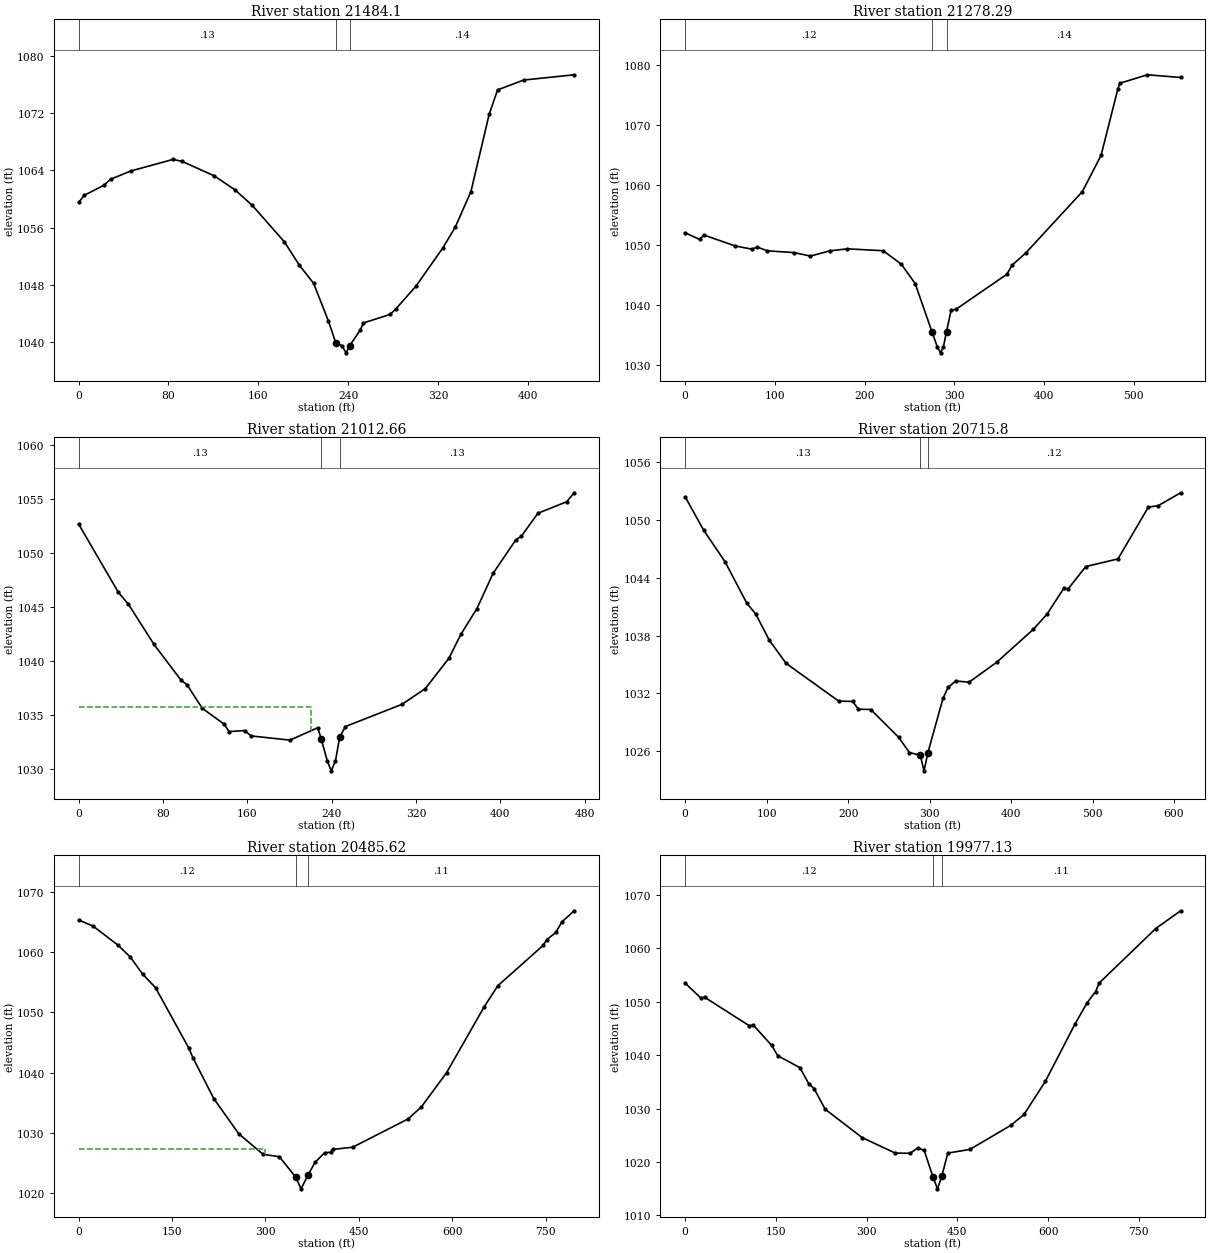
Type RM Length L Ch R = 1 ,21484.1 ,188.61,205.81,217.15
XS GIS Cut Line= 3
   1372170.90429   774729.630394  1371933.108836   774696.945633
  1371734.131572   774667.725575
#Sta/Elev= 30
       0 1059.52    5.04 1060.52    22.2 1061.91   28.51 1062.78   46.72 1063.94
   84.14 1065.55   92.05 1065.27  120.71 1063.25  139.13 1061.29  154.66  1059.1
  183.23 1053.99  196.43 1050.75  209.19 1048.19  222.42 1042.89  228.98 1039.84
  234.42 1039.46   238.1 1038.46  241.33 1039.47  250.76 1041.67  253.52 1042.64
  277.57 1043.86  282.54 1044.64  300.16 1047.77  324.08 1053.12  335.16 1056.03
  349.21 1061.03   365.5 1071.88  372.95 1075.28  396.15 1076.66  441.14  1077.4
#Mann= 3 , 0 , 0
       0     .13       0  228.98     .05       0  241.33     .14       0
Bank Sta=228.98,241.33
Exp/Cntr=0.3,0.1

Type RM Length L Ch R = 1 ,21278.29,262,265.63,268
XS GIS Cut Line= 3
  1372226.024954   774686.998172  1371988.351993   774529.410663
  1371765.714201   774381.792151
#Sta/Elev= 30
       0 1052.07   16.07 1050.96   20.98 1051.69   56.05 1049.86   74.46 1049.34
   80.55 1049.68   91.77 1049.06  121.16 1048.77  139.64 1048.19  161.45 1049.06
  180.93 1049.39  220.74 1049.08  240.95 1046.84   256.4 1043.61  275.11 1035.59
  281.07 1033.07  284.78 1032.07  287.96 1033.11  291.37 1035.61  296.45 1039.16
  301.69  1039.3  358.61 1045.16  364.47 1046.67  380.07 1048.76  442.72 1058.92
  463.59 1064.95  482.27 1075.98  484.39 1076.96  515.13 1078.38   552.3 1077.93
#Mann= 3 , 0 , 0
       0     .12       0  275.11     .05       0  291.37     .14       0
Bank Sta=275.11,291.37
Exp/Cntr=0.3,0.1

Type RM Length L Ch R = 1 ,21012.66,277.42,296.86,316.25
XS GIS Cut Line= 4
   1372298.52302   774406.509299  1372155.297276   774314.116207
  1372091.063123   774285.047199    1371879.3284    774197.74353
#Sta/Elev= 30
       0 1052.69   37.73 1046.35   47.24 1045.25   71.53 1041.52   97.15  1038.2
  102.74 1037.79  117.18  1035.6  138.04 1034.12  142.69 1033.43   157.4 1033.53
  163.57 1033.03   200.5 1032.64  226.78 1033.79  230.05 1032.75  235.74 1030.74
  239.58 1029.79  243.61 1030.73  247.58 1032.91  252.99  1033.9  306.59 1035.96
  328.89 1037.43   351.3 1040.26  362.51 1042.46  377.72 1044.85  393.11 1048.13
  414.71 1051.24  419.78 1051.56  435.61  1053.7  462.71 1054.76  469.97  1055.6
#Mann= 3 , 0 , 0
       0     .13       0  230.05     .05       0  247.58     .13       0
#XS Ineff= 2 , 0
          220.66 1035.75
Permanent Ineff=
       F       F
Bank Sta=230.05,247.58
Exp/Cntr=0.3,0.1

Type RM Length L Ch R = 1 ,20715.8 ,233.9,230.18,220.29
XS GIS Cut Line= 4
   1372433.00611   774309.574287  1372314.039399   774178.361027
  1372221.315366   774015.656553   1372032.36824   773861.699648
#Sta/Elev= 30
       0 1052.43   22.74 1048.96   49.07 1045.67   75.65 1041.38   86.77 1040.24
  103.25 1037.54  123.96 1035.12  188.51  1031.2  205.72 1031.17  212.65 1030.36
   227.8 1030.33  261.98 1027.45  275.27 1025.86  288.62 1025.58  293.24 1023.96
  297.86 1025.81  316.46 1031.48  322.65 1032.62  332.05 1033.29   348.5 1033.17
  382.43 1035.24  427.42 1038.66   444.1 1040.23   464.6  1042.9  470.07 1042.86
  491.78 1045.18  531.21 1045.97  568.48 1051.35  580.62  1051.5  608.12 1052.84
#Mann= 3 , 0 , 0
       0     .13       0  288.62     .05       0  297.86     .12       0
Bank Sta=288.62,297.86
Exp/Cntr=0.3,0.1

Type RM Length L Ch R = 1 ,20485.62,505.59,508.49,507.7
XS GIS Cut Line= 4
  1372721.292742   774162.517555  1372466.104776    773990.02533
  1372439.297378   773963.678104  1372122.528251   773643.601123
#Sta/Elev= 30
       0 1065.33   23.53 1064.28   63.54 1061.12   83.14 1059.16  102.68 1056.35
  123.54 1054.08  176.93 1044.07  183.44 1042.49  216.98  1035.7  257.13 1029.85
  296.26 1026.44  322.38 1026.04  348.66 1022.66  357.21 1020.71   368.2 1022.93
  379.69 1025.12  395.19 1026.69  404.72 1026.78  408.07 1027.25   440.2 1027.62
  529.19 1032.31  550.45  1034.3  591.03 1039.99  651.65 1050.96  673.38 1054.42
  746.03  1061.1  751.77 1062.05  766.36 1063.25  776.29 1065.01  795.93 1066.85
#Mann= 3 , 0 , 0
       0     .12       0  348.66     .05       0   368.2     .11       0
#XS Ineff= 2 , 0
          299.97  1027.4
Permanent Ineff=
       F       F
Bank Sta=348.66,368.2
Exp/Cntr=0.3,0.1

Type RM Length L Ch R = 1 ,19977.13,505.18,507.88,507.38
XS GIS Cut Line= 3
  1372994.050954   773864.161228  1372715.020616   773564.434556
  1372435.996572   773264.714569
#Sta/Elev= 30
       0 1053.52   25.82 1050.74   32.23 1050.86  106.05 1045.53  112.51 1045.66
   143.1 1041.84  153.09 1039.92  189.68 1037.67  204.29 1034.68  213.25 1033.74
  231.44 1029.89  292.76 1024.56  347.46 1021.66  372.06 1021.63  384.68 1022.65
  395.17 1022.17   409.5 1017.24  417.12 1014.97  424.24 1017.34   434.2 1021.67
  470.61 1022.35  538.98 1026.91  560.25 1028.92  595.41 1035.11  644.41 1045.85
  664.38 1049.82  678.38 1051.92  684.43 1053.53  777.82 1063.73     819 1067.06
#Mann= 3 , 0 , 0
       0     .12       0   409.5     .05       0  424.24     .11       0
Bank Sta=409.5,424.24
Exp/Cntr=0.3,0.1

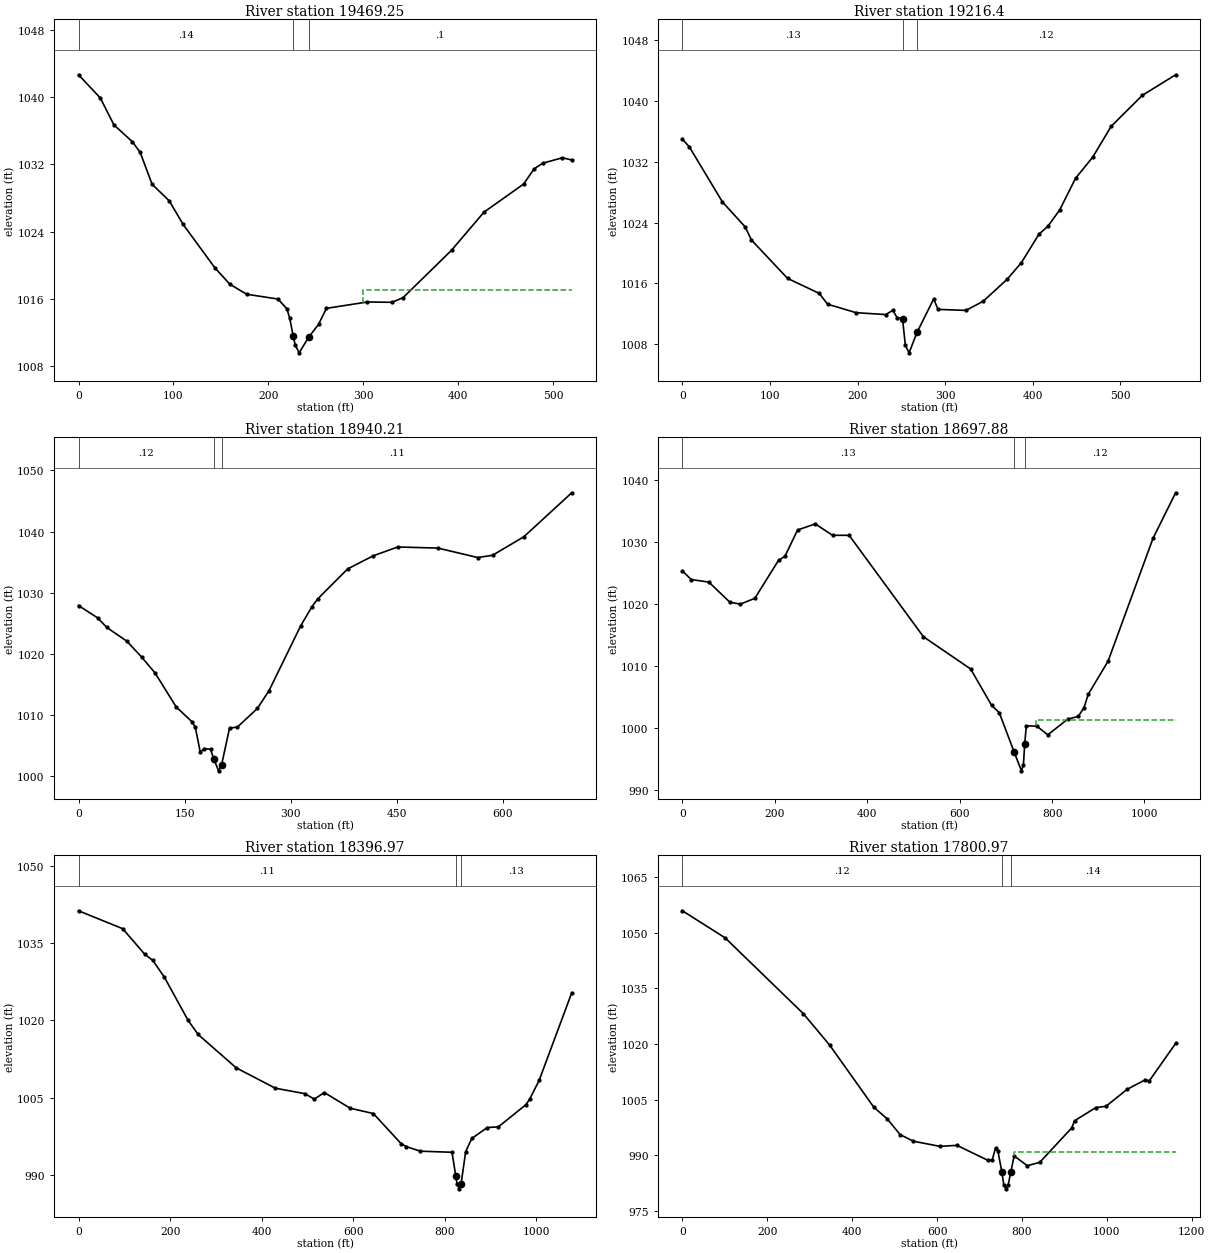
Type RM Length L Ch R = 1 ,19469.25,250,252.85,255
XS GIS Cut Line= 2
  1373205.805364   773392.039963  1372870.943847   772994.989861
#Sta/Elev= 30
       0 1042.68   22.94 1039.92   37.29 1036.71   56.74  1034.7   64.96 1033.43
   77.51 1029.63   95.55 1027.66  110.12 1024.86   143.6 1019.68   159.4 1017.72
  177.15 1016.53  210.12 1015.96  219.44 1014.79  222.34 1013.71  226.09 1011.58
  228.12 1010.52  232.33 1009.55  242.28  1011.4  252.74 1012.94  261.07 1014.85
  304.19 1015.61  330.22 1015.57  341.82 1016.13  392.82 1021.77  426.96 1026.31
  468.74 1029.66  479.68 1031.46     489 1032.15  509.59 1032.79   519.4 1032.53
#Mann= 3 , 0 , 0
       0     .14       0  226.09     .05       0  242.28      .1       0
#XS Ineff= 2 , 0
                           299.9            1017
Permanent Ineff=
       F       F
Bank Sta=226.09,242.28
Exp/Cntr=0.3,0.1

Type RM Length L Ch R = 1 ,19216.4 ,280.4,276.19,273.64
XS GIS Cut Line= 3
  1373362.329829   773270.111943  1373239.426046   773042.128765
  1373092.302398   772775.733367
#Sta/Elev= 30
       0 1034.99    7.92 1033.98   45.71 1026.73   71.57 1023.46   78.88 1021.71
  120.07 1016.67  156.37 1014.68  165.76 1013.27  198.31 1012.15  232.23  1011.9
  240.37 1012.46  245.09 1011.51  251.39 1011.34  254.64 1007.86  258.89 1006.86
  268.02 1009.57  286.96 1013.95  291.95 1012.58   323.9 1012.45  343.75 1013.67
  370.99 1016.56  387.06 1018.72  407.27 1022.49  417.49 1023.54  430.75 1025.65
  449.04 1029.85  468.63 1032.63  489.69 1036.69  525.28 1040.77  563.32 1043.48
#Mann= 3 , 0 , 0
       0     .13       0  251.39     .05       0  268.02     .12       0
Bank Sta=251.39,268.02
Exp/Cntr=0.3,0.1

Type RM Length L Ch R = 1 ,18940.21,236.18,242.33,248.88
XS GIS Cut Line= 3
  1373611.775643   773109.919608  1373491.516557   772947.398225
   1373222.54845   772531.206655
#Sta/Elev= 30
       0 1027.88   27.49 1025.82   39.95 1024.29   68.28 1022.05   89.22 1019.45
  108.39 1016.82  138.15 1011.27  160.75 1008.82  165.23 1007.94  172.23 1003.86
  178.02 1004.44  186.75 1004.35  191.28 1002.75  198.22  1000.8  202.47 1001.81
  213.64  1007.8  224.81 1007.97   253.1 1011.03  269.47 1013.93  314.29 1024.55
  330.17 1027.68   338.6 1028.99  380.79 1033.88   416.8 1036.02  451.63 1037.47
  508.44 1037.29  564.74 1035.74  585.65 1036.11  629.96 1039.14  697.72 1046.35
#Mann= 3 , 0 , 0
       0     .12       0  191.28     .05       0  202.47     .11       0
Bank Sta=191.28,202.47
Exp/Cntr=0.3,0.1

Type RM Length L Ch R = 1 ,18697.88,318.12,300.91,281.29
XS GIS Cut Line= 5
  1373643.262045   773543.120109  1373768.950287   772977.092004
  1373703.610985   772837.299781  1373678.482455   772769.561966
  1373547.630123   772543.737852
#Sta/Elev= 30
       0 1025.29   18.85 1023.89   57.26 1023.47  102.64 1020.23   125.5 1019.92
  156.72 1020.86  207.94 1026.97  221.86 1027.64  249.31 1031.88  287.55 1032.86
  324.91 1031.02  360.83 1031.02  521.57 1014.66  623.76 1009.46  669.32 1003.57
  685.67 1002.42  718.11  996.03  733.66  993.03  738.01  993.99  740.67  997.28
   744.2 1000.28  766.66 1000.25  790.72  998.84  834.04 1001.38  856.54  1001.8
  868.98  1003.2  878.31 1005.38     921 1010.69 1018.41 1030.53 1067.37 1037.88
#Mann= 3 , 0 , 0
       0     .13       0  718.11     .05       0  740.67     .12       0
#XS Ineff= 2 , 0
                          766.17         1001.25
Permanent Ineff=
       F       F
Bank Sta=718.11,740.67
Exp/Cntr=0.3,0.1

Type RM Length L Ch R = 1 ,18396.97,599.05,596,590.75
XS GIS Cut Line= 4
  1374391.589008   773257.905732  1374076.835776   772751.320216
  1373874.127964   772625.868093  1373672.649356   772491.211691
#Sta/Elev= 30
       0  1041.3   96.53 1037.82  144.49 1032.87  162.37 1031.65  187.48 1028.41
  239.04 1020.07  261.14 1017.29  344.46  1010.8   430.1 1006.84  493.94  1005.8
  515.14 1004.73   536.7 1006.01  593.42 1002.96  643.93 1001.93  704.19  996.11
  715.84  995.51  746.65  994.62  815.66  994.41  823.88  989.83  826.55  988.31
  831.34  987.31  835.55   988.3  845.55  994.55  858.94   997.1  892.85  999.22
  916.92  999.34  977.54 1003.68  985.68  1004.8 1005.95 1008.36 1077.13 1025.37
#Mann= 3 , 0 , 0
       0     .11       0  823.88     .05       0  835.55     .13       0
Bank Sta=823.88,835.55
Exp/Cntr=0.3,0.1

Type RM Length L Ch R = 1 ,17800.97,424.96,424.16,422.83
XS GIS Cut Line= 3
  1374806.432548   772414.696998  1374123.384707   772098.713236
  1373751.731972   771926.774392
#Sta/Elev= 30
       0  1055.9  100.62 1048.61  285.06 1028.17  347.02  1019.7  451.25 1002.95
  482.53  999.85  513.02   995.6  544.45  993.82   606.5  992.45  646.99  992.71
   719.6  988.69  729.96  988.79  737.77     992  743.28  991.22   752.6  985.57
  757.27  982.05  762.41     981   767.6  982.06  773.91  985.62  781.64  989.87
  812.59  987.23  841.92  988.14  917.18   997.4  923.89  999.33  974.38 1002.91
  997.95 1003.23 1048.09 1007.83 1089.67 1010.31 1100.19 1010.11 1162.09 1020.16
#Mann= 3 , 0 , 0
       0     .12       0   752.6     .05       0  773.91     .14       0
#XS Ineff= 2 , 0
                          781.59          990.92
Permanent Ineff=
       F       F
Bank Sta=752.6,773.91
Exp/Cntr=0.3,0.1

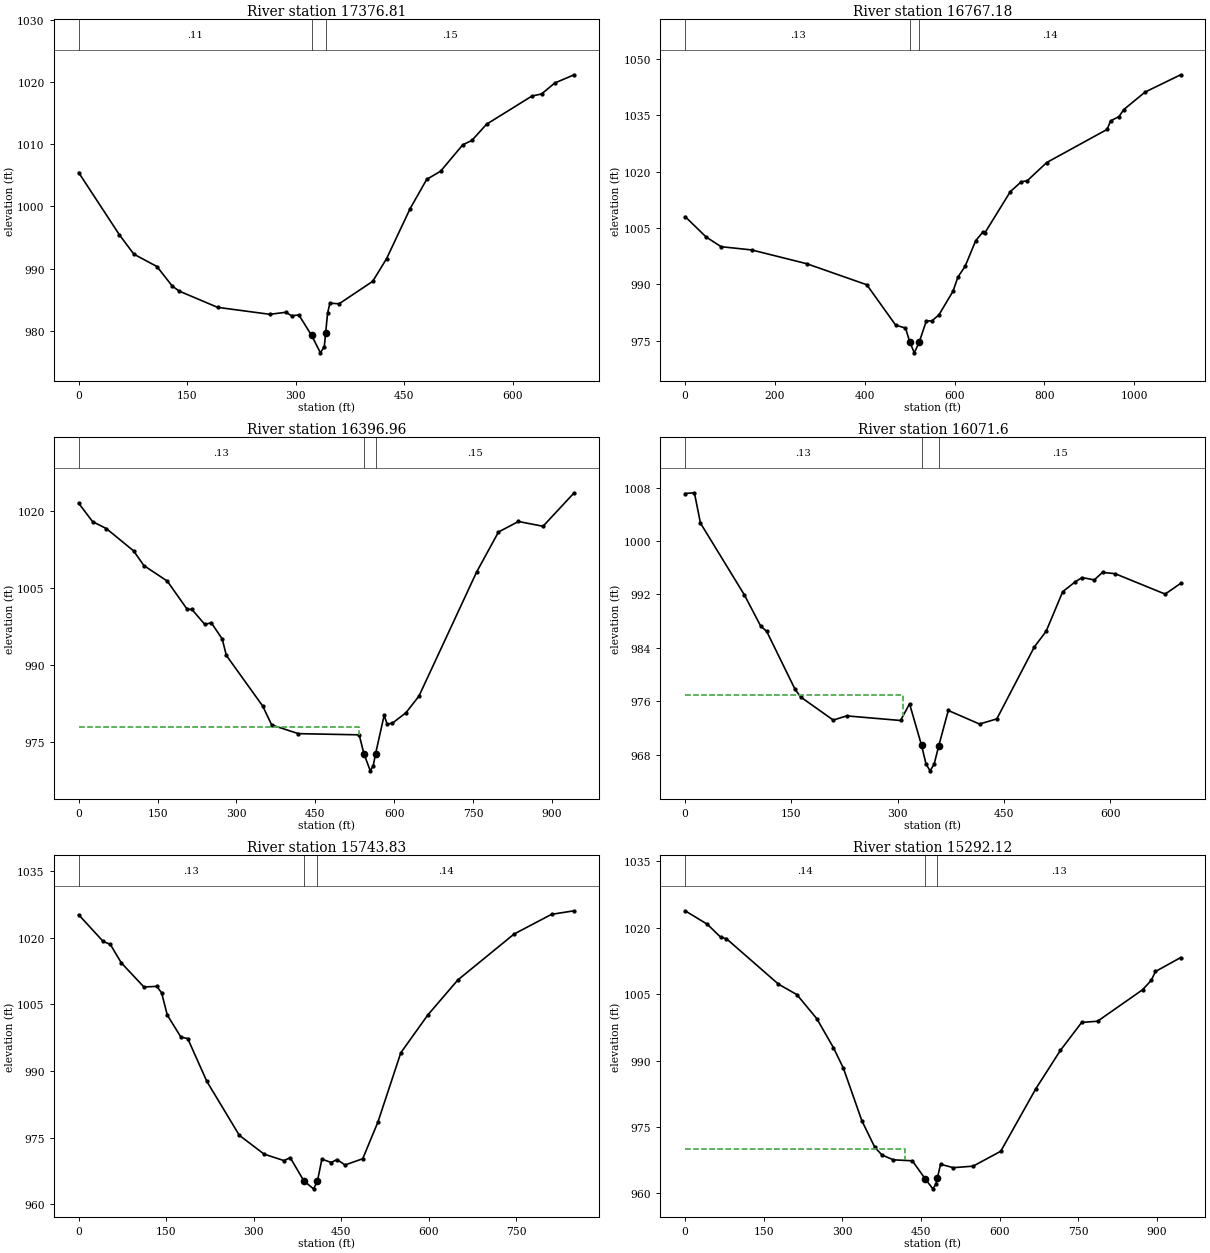
Type RM Length L Ch R = 1 ,17376.81,608.47,609.63,598.88
XS GIS Cut Line= 2
  1374626.111953   771861.879657  1373996.641718   771592.616187
#Sta/Elev= 30
       0 1005.45   56.43  995.43   76.28  992.34  108.25  990.35   129.4  987.21
  139.12   986.4  191.88   983.8  264.04  982.68  286.15     983  294.37  982.45
  304.28  982.57  321.95  979.28  334.06  976.49  339.41  977.49  341.24  979.64
  343.93  982.85  347.14  984.47  359.92  984.37  406.33  987.98  425.55  991.64
  458.04  999.66   480.9 1004.35  500.07 1005.66  530.87 1009.92   543.3  1010.6
   563.6 1013.21  626.41 1017.74  639.65 1018.07   657.8 1019.83  684.64 1021.15
#Mann= 3 , 0 , 0
       0     .11       0  321.95     .05       0  341.24     .15       0
Bank Sta=321.95,341.24
Exp/Cntr=0.3,0.1

Type RM Length L Ch R = 1 ,16767.18,370.94,370.21,367.39
XS GIS Cut Line= 4
  1374771.793581   771561.685038  1374621.039512   771232.443621
  1374475.526515   771201.963931  1373890.888033   771106.148267
#Sta/Elev= 30
       0 1008.06   46.84 1002.62   80.13 1000.04  147.96  999.18  270.45  995.52
  404.46  989.91  468.89  979.15  490.66  978.39  500.51  974.59  510.27  971.79
  521.27  974.65  537.05   980.3  549.16  980.27  565.04  981.88  596.36  988.16
  607.41  991.97  623.27  994.78  646.92 1001.63  662.53 1003.88  667.04 1003.64
  724.12  1014.7  748.65 1017.34  761.43 1017.56  805.14 1022.44  939.45 1031.25
  947.23 1033.52  966.08 1034.67  976.42 1036.51 1023.93 1041.18 1103.22 1045.79
#Mann= 3 , 0 , 0
       0     .13       0  500.51     .05       0  521.27     .14       0
Bank Sta=500.51,521.27
Exp/Cntr=0.3,0.1

Type RM Length L Ch R = 1 ,16396.96,326.06,325.37,326.61
XS GIS Cut Line= 3
  1375095.539837   770946.160946  1374548.861647   770850.445593
  1374163.816878   770812.420803
#Sta/Elev= 30
       0 1021.57   26.48 1017.98   52.72 1016.62  104.49 1012.28  124.06 1009.42
  168.44  1006.4  206.47 1000.89  215.03 1000.91  239.97  997.95   252.1   998.3
  272.95  995.13  280.72  991.94  349.93  982.07  366.92  978.39  417.71   976.7
  533.27  976.47  542.31  972.77  554.39  969.46  560.01  970.47  564.44  972.79
  580.71  980.27   586.3  978.58  596.14  978.72   622.2  980.77  646.92  984.02
  756.57 1008.18  798.07 1015.96  836.03    1018  882.71 1017.07  941.91 1023.59
#Mann= 3 , 0 , 0
       0     .13       0  542.31     .05       0  564.44     .15       0
#XS Ineff= 2 , 0
          532.88  977.92
Permanent Ineff=
       F       F
Bank Sta=542.31,564.44
Exp/Cntr=0.3,0.1

Type RM Length L Ch R = 1 ,16071.6 ,331.39,327.76,324.55
XS GIS Cut Line= 3
  1374912.761641   770582.610671  1374571.707917   770533.672435
  1374221.770946   770476.287274
#Sta/Elev= 30
       0 1007.11   13.11 1007.22   21.66 1002.68   83.68  991.92   106.6  987.27
  115.14  986.46   155.2  977.77  163.45  976.61  209.03  973.18  227.95  973.81
  303.99  973.12  316.68  975.62  333.61   969.4  339.98  966.58  345.68  965.58
  351.35  966.58  357.82   969.3  371.34  974.62  415.38  972.59   439.8  973.36
  492.77  984.14  509.38  986.48   532.8  992.41  549.63  993.82  560.01  994.53
  577.23  994.17  588.96   995.3  606.78   995.1   677.3  992.05  699.16  993.65
#Mann= 3 , 0 , 0
       0     .13       0  333.61     .05       0  357.82     .15       0
#XS Ineff= 2 , 0
          307.58  976.91
Permanent Ineff=
       F       F
Bank Sta=333.61,357.82
Exp/Cntr=0.3,0.1

Type RM Length L Ch R = 1 ,15743.83,447.19,451.71,455.17
XS GIS Cut Line= 3
  1375015.365075    770217.74719  1374613.859709    770209.85518
  1374167.176173   770184.544079
#Sta/Elev= 30
       0 1025.19   41.95 1019.19   54.27 1018.51   73.23 1014.33  111.91 1008.92
   133.9 1009.06  142.14 1007.61  151.89  1002.6  175.25  997.64  186.91  997.31
  219.59  987.68  275.27  975.53  317.79  971.28  351.78  969.83  362.45   970.5
  386.09  965.22  402.49  963.47   409.1  965.21   416.8  970.17  432.74   969.4
   442.7  970.07  456.29  968.84  486.74  970.25  512.72   978.5  552.01  994.12
  598.42 1002.65  649.67  1010.5  746.11 1020.85  810.23 1025.28  848.98 1026.08
#Mann= 3 , 0 , 0
       0     .13       0  386.09     .05       0   409.1     .14       0
Bank Sta=386.09,409.1
Exp/Cntr=0.3,0.1

Type RM Length L Ch R = 1 ,15292.12,420.92,427.86,433.7
XS GIS Cut Line= 3
  1375151.395229   769859.327482  1374686.350648   769767.402103
  1374222.220896   769687.369887
#Sta/Elev= 30
       0 1023.83   42.26  1020.8   67.73 1017.87   78.95 1017.51  177.98 1007.27
  213.21 1004.89  251.08  999.48  282.88  992.92  302.05  988.23  337.13  976.41
  361.92  970.38  375.62  968.67  397.27  967.59  433.35  967.37  458.04  963.28
  472.48  961.04  478.21  962.06  480.99  963.42  487.21   966.6  511.25  965.82
  549.19  966.16   601.9  969.52  668.82  983.63   715.7   992.3  756.32  998.62
   786.6  998.89  872.35 1005.99  888.96 1008.12  897.04 1010.12  945.02 1013.26
#Mann= 3 , 0 , 0
       0     .14       0  458.04     .05       0  480.99     .13       0
#XS Ineff= 2 , 0
          420.18  970.04
Permanent Ineff=
       F       F
Bank Sta=458.04,480.99
Exp/Cntr=0.3,0.1

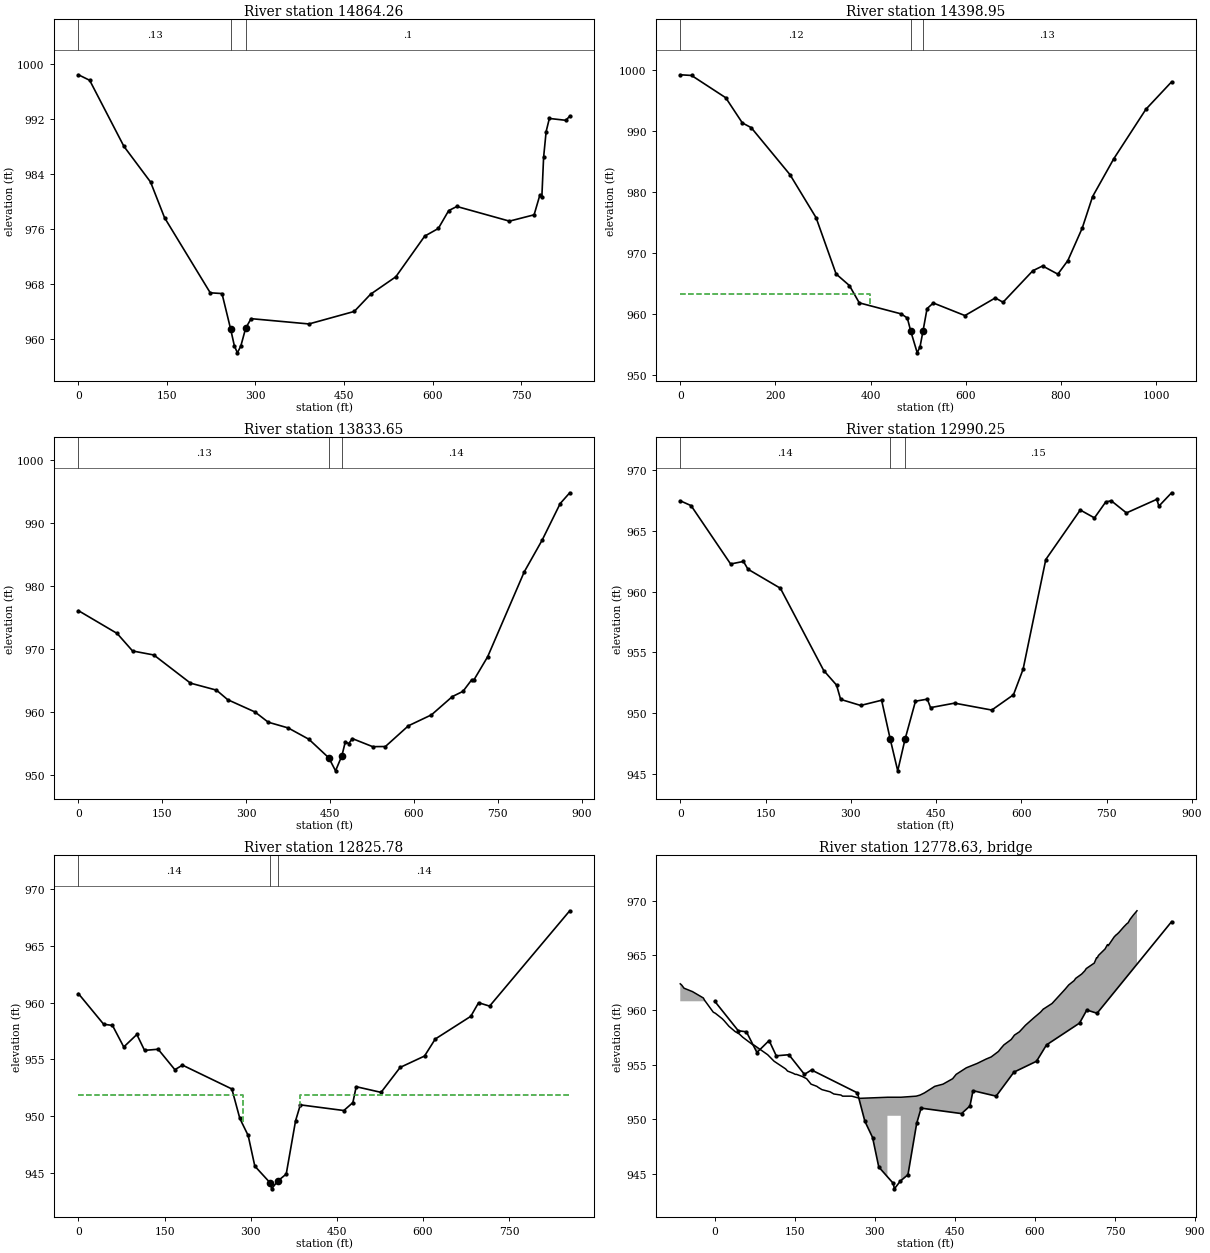
Type RM Length L Ch R = 1 ,14864.26,474.99,465.31,445.04
XS GIS Cut Line= 2
  1375171.325912   769525.840704  1374397.862123   769218.238381
#Sta/Elev= 30
       0  998.46   19.04  997.66   77.02  988.06  122.25  982.86  145.92  977.68
  223.32  966.76  243.25  966.65  257.97  961.45  264.27  959.02  269.35  958.03
  275.17  959.03  283.34  961.61   292.5     963  390.57  962.23  467.32  964.05
  494.95  966.55  537.78  969.09  586.67     975  609.71  976.11   627.3  978.71
  641.17  979.31  730.24  977.18  772.02   978.1  781.57  980.91  785.12  980.66
   788.1  986.45   792.4  990.21  797.86  992.11  825.75  991.84  832.39  992.44
#Mann= 3 , 0 , 0
       0     .13       0  257.97     .05       0  283.34      .1       0
Bank Sta=257.97,283.34
Exp/Cntr=0.3,0.1

Type RM Length L Ch R = 1 ,14398.95,553.78,565.3,577.5
XS GIS Cut Line= 3
  1375353.990794    768999.50151  1374825.214909    769074.46425
  1374331.363238   769142.202663
#Sta/Elev= 30
       0  999.15   23.76  999.04   95.62  995.39  130.52  991.27  149.12   990.5
  230.55  982.81  285.48  975.76  327.54  966.55  355.54  964.65  376.26  961.82
   464.5  960.01  477.21  959.34  484.52  957.16  498.04  953.64  503.98  954.65
  510.22  957.23   518.7  960.88  531.84   961.8  598.27  959.74  662.11  962.63
  678.38  961.92  741.01  967.08  761.56  967.86  793.54  966.52  814.55  968.74
  844.88  974.07  866.52  979.21  911.05   985.4  978.53   993.5 1032.54  997.99
#Mann= 3 , 0 , 0
       0     .12       0  484.52     .05       0  510.22     .13       0
#XS Ineff= 2 , 0
          399.79  963.33
Permanent Ineff=
       F       F
Bank Sta=484.52,510.22
Exp/Cntr=0.3,0.1

Type RM Length L Ch R = 1 ,13833.65,823.11,843.41,847.07
XS GIS Cut Line= 3
  1375407.823218   768632.394987  1374961.551818   768523.089944
  1374556.959192   768412.807291
#Sta/Elev= 30
       0  976.16   69.22  972.54   96.85  969.76  134.93  969.12  200.46  964.65
  246.94  963.54  266.91  962.03   315.9  960.07  339.54  958.45  375.22  957.54
  412.28  955.74  447.89  952.79  459.91  950.73  471.28  953.13  477.39  955.34
  483.47  955.05  489.93  955.85   526.3  954.57  549.08  954.59  590.19  957.88
  631.52  959.62  668.84  962.52  687.89  963.35  703.58   965.2  707.47  965.17
  731.99  968.84  797.46  982.32  829.44  987.35  861.74  993.16  878.82  994.87
#Mann= 3 , 0 , 0
       0     .13       0  447.89     .05       0  471.28     .14       0
Bank Sta=447.89,471.28
Exp/Cntr=0.3,0.1

Type RM Length L Ch R = 1 ,12990.25,129.51,164.46,181.6
XS GIS Cut Line= 4
  1375251.103128   768004.458031  1374970.497145   767942.431653
  1374893.396302   767889.054147  1374481.985477   767636.504921
#Sta/Elev= 30
       0  967.49   19.06  967.09   88.56  962.28  111.14  962.49  119.06  961.85
  176.08  960.28  252.25   953.5  274.82   952.3     282  951.12  317.23  950.62
  354.08  951.05  369.32  947.82   382.4  945.23  395.19  947.82  413.62  950.97
  434.43  951.14  440.08  950.44  482.28  950.81  547.79  950.24   585.9   951.5
  602.81   953.6  642.76  962.65  703.34  966.73  728.33  966.08  748.24   967.4
  757.88  967.49  784.58  966.49  837.91  967.61  841.62  967.05   863.9  968.15
#Mann= 3 , 0 , 0
       0     .14       0  369.32     .05       0  395.19     .15       0
Bank Sta=369.32,395.19
Exp/Cntr=0.5,0.3

Type RM Length L Ch R = 1 ,12825.78,109.83,79.65,65.84
BEGIN DESCRIPTION:
Upstream xs of Bridge 37003-0074
END DESCRIPTION:
XS GIS Cut Line= 6
  1375158.033121   767947.755974  1374968.565565    767803.90507
  1374872.672245   767728.062143  1374756.511058   767640.722896
  1374573.599394    767497.78266  1374477.929917   767428.204863
#Sta/Elev= 30
       0   960.8      44   958.1  59.299     958  78.999   956.1 101.799   957.2
   115.2   955.8   138.9   955.9     168   954.1 181.299   954.5 267.301   952.4
 281.199   949.8 295.699   948.3   307.3   945.6   334.5   944.1 336.499   943.6
 347.501   944.3     362   944.9 378.299   949.6 386.599     951   462.4   950.5
   478.1   951.2   483.9   952.6   527.2   952.1   560.5   954.3   602.9   955.3
 621.601   956.8 683.499   958.8   697.1     960 716.301   959.7   855.9   968.1
#Mann= 3 , 0 , 0
       0     .14       0   334.5     .05       0 347.501     .14       0
#XS Ineff= 2 , 0
       0   286.3   951.9   385.7       0   951.9
Permanent Ineff=
       F       F
Bank Sta=334.5,347.501
Exp/Cntr=0.5,0.3

Type RM Length L Ch R = 3 ,12778.63,,,
BEGIN DESCRIPTION:
Bridge : 37003-0074 (Middle Road)
END DESCRIPTION:
Bridge Culvert--1,0,-1,-1, 0
Deck Dist Width WeirC Skew NumUp NumDn MinLoCord MaxHiCord MaxSubmerge Is_Ogee
37.2,20,2.6,0, 94, 94, , , 0.95, 0, 0,0,,
   -64.7   -62.2   -57.6   -42.5   -42.2 -21.299 -19.199    -2.8     1.1  13.999
    17.9    26.7    38.7  38.899      46    52.5    71.5  72.799      73    99.1
   111.2   132.7 136.399   146.8   150.7   153.1   164.1   172.1   180.4 191.301
     194   200.7     216     223   236.5 239.399   255.5   255.8   256.5   271.6
   323.5   323.5   348.5   348.5   377.4   384.6   392.9     409   412.1   427.6
 445.701 452.299 471.299   491.6 508.299     518   531.5   536.4   541.7     550
   555.5 561.499 570.801   582.1   598.2   610.3 615.799   616.2 631.999   656.3
   663.2   673.4 676.201   687.5   693.4     696   707.9     711   715.4 717.001
 718.799   731.3   735.8   737.2   748.3   752.2 752.601     757   765.9   771.8
   774.5 777.899   784.2   791.1
   962.4   962.3     962   961.7   961.7   961.1   960.9   959.8   959.7   959.2
     959   958.5     958     958   957.8   957.5   956.8   956.8   956.8   955.9
   955.3   954.6   954.4   954.2   954.1   954.1   953.9   953.7   953.2     953
   952.9   952.7   952.5   952.3   952.2   952.1   952.1   952.1   952.1   951.9
     952     952     952     952   952.1   952.2   952.4   952.9     953   953.2
   953.7   954.1   954.7   955.1   955.5   955.7   956.2   956.5   956.8   957.1
   957.3   957.7     958   958.6   959.3   959.8   960.1   960.1   960.6   961.9
   962.3   962.7   962.9   963.3   963.6   963.8   964.2   964.3   964.8   964.8
     965   965.6     966   965.9   966.7   966.9   966.9   967.1   967.6   967.9
     968   968.3   968.7   969.1
                                                                                
                                                                                
                                                                                
                                                                                
           950.3   950.3
                                                                                
                                                                                
                                                                                
                                                                                
                                
   -24.5     -22 -17.499    -2.3      -2  18.801      21    37.3    41.2    54.2
    58.1    66.8    78.8  78.999  86.201    92.6   111.6 112.899 113.199   139.3
   151.3   172.8   176.5     187   190.8   193.3   204.3   212.2   220.6 231.399
   234.1   240.8   256.2 263.201   276.6   279.6 295.699   295.9   296.6   311.8
 364.499 364.499   389.5   389.5   417.6   424.8     433   449.1   452.2 467.801
   485.9   492.5   511.5   531.7 548.399   558.2   571.6   576.6   581.8   590.1
 595.701   601.7     611   622.2   638.3   650.4     656   656.4   672.2   696.4
   703.4 713.599 716.301 727.701 733.601   736.1 748.101 751.201   755.6   757.2
     759   771.4     776   777.4   788.5   792.3   792.8   797.1   806.1   811.9
   814.7   818.1   824.4   831.3
   962.4   962.3     962   961.7   961.7   961.1   960.9   959.8   959.7   959.2
     959   958.5     958     958   957.8   957.5   956.8   956.8   956.8   955.9
   955.3   954.6   954.4   954.2   954.1   954.1   953.9   953.7   953.2     953
   952.9   952.7   952.5   952.3   952.2   952.1   952.1   952.1   952.1   951.9
     952     952     952     952   952.1   952.2   952.4   952.9     953   953.2
   953.7   954.1   954.7   955.1   955.5   955.7   956.2   956.5   956.8   957.1
   957.3   957.7     958   958.6   959.3   959.8   960.1   960.1   960.6   961.9
   962.3   962.7   962.9   963.3   963.6   963.8   964.2   964.3   964.8   964.8
     965   965.6     966   965.9   966.7   966.9   966.9   967.1   967.6   967.9
     968   968.3   968.7   969.1
                                                                                
                                                                                
                                                                                
                                                                                
           950.3   950.3
                                                                                
                                                                                
                                                                                
                                                                                
                                
BR Coef=-1 , 1 , 0 ,, 0 ,,,0.8,0,1.2,0,
WSPro=,,,, 1 ,,,, 0 ,,,, 0 ,,,,-1 ,-1 ,-1 , 0 , 0 , 0 , 0 , 0
BC Design=,, 0 ,, 0 ,,,,,,