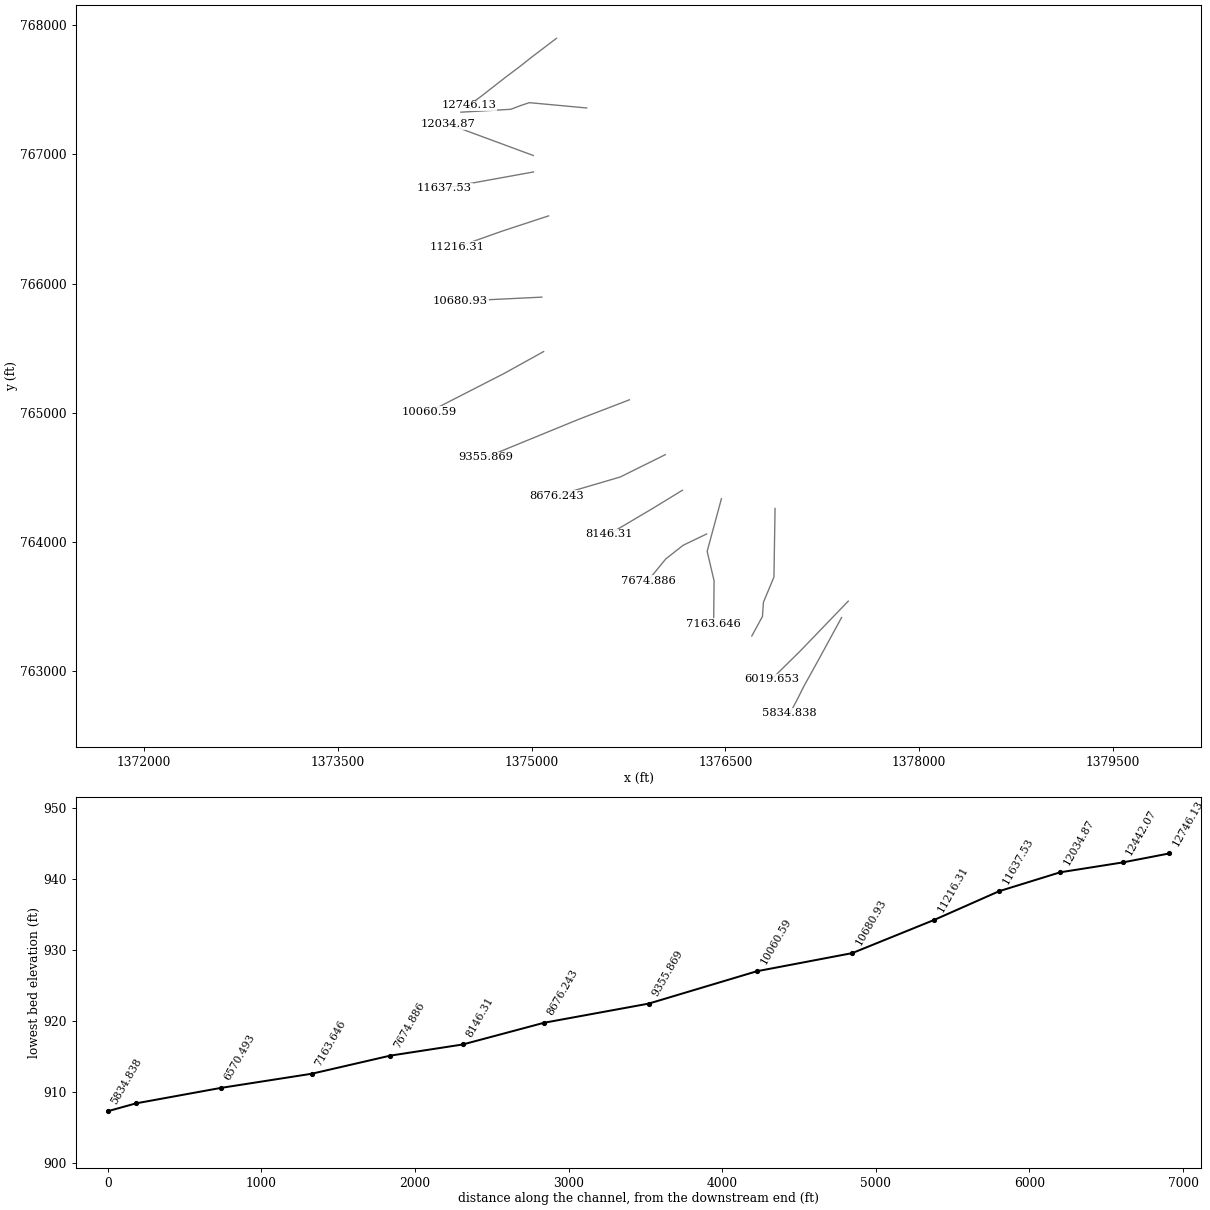
HEC-RAS study BigBranch.prj: BigBranch

--- BigBranch.g01 (geometry) --- (continued)

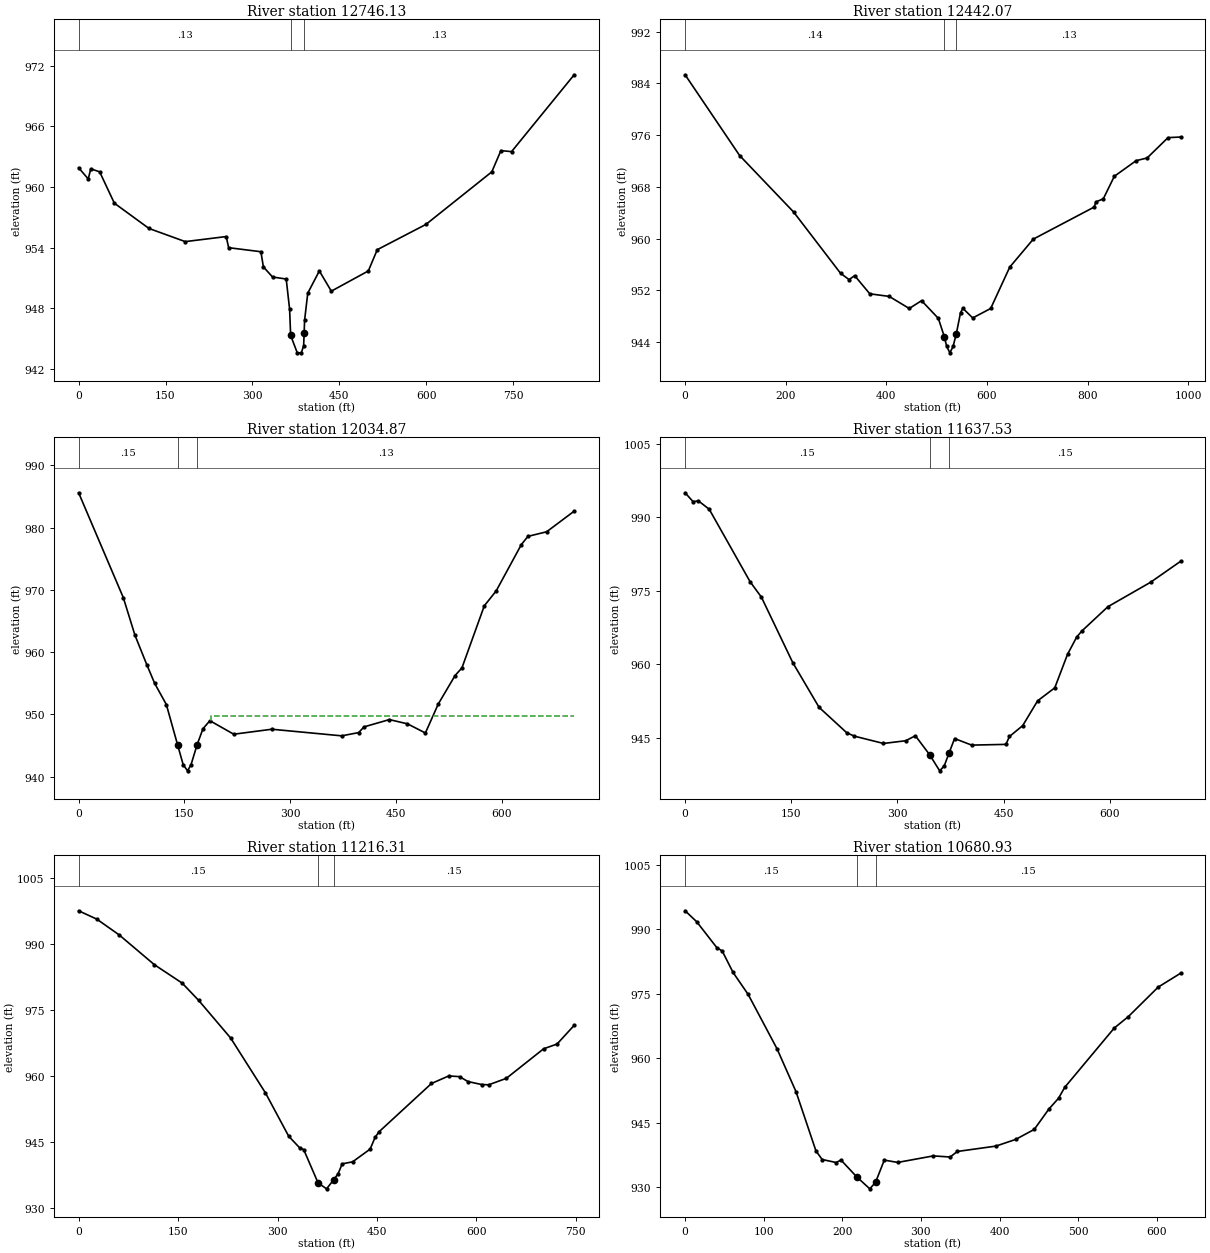
Type RM Length L Ch R = 1 ,12746.13,314.44,304.06,293.6
BEGIN DESCRIPTION:
Down stream xs of Bridge 37003-0074
END DESCRIPTION:
XS GIS Cut Line= 6
  1375193.080452   767899.043896  1375005.459303   767756.586717
  1374909.316678   767680.546655  1374793.289012   767593.307797
  1374609.586677    767449.76539  1374513.220207   767379.680713
#Sta/Elev= 30
       0   961.9    16.6   960.8      21   961.8    36.3   961.5  61.699   958.4
 121.499   955.9 184.099   954.6   254.8   955.1     259     954 314.701   953.6
     319   952.1 334.799   951.1   358.4   950.9   364.3   947.9 366.061945.3272
   377.5   943.6 384.501   943.6   388.5   944.3  389.39  945.55   390.1   946.8
 395.599   949.5 415.601   951.7   436.3   949.7   500.2   951.7   515.6   953.8
   599.6   956.3   713.4   961.5 729.101   963.6   747.5   963.5 855.601   971.1
#Mann= 3 , 0 , 0
       0     .13       0 366.061     .05       0  389.39     .13       0
#XS Ineff= 2 , 0
       0 342.001   950.5     412       0   950.5
Permanent Ineff=
       F       F
Bank Sta=366.061,389.39
Exp/Cntr=0.5,0.3

Type RM Length L Ch R = 1 ,12442.07,422.97,407.21,378.73
XS GIS Cut Line= 5
  1375427.008379    767359.92277  1374982.878671   767401.049177
  1374914.459546   767378.069022  1374839.669884   767349.742362
  1374453.471852    767327.33577
#Sta/Elev= 30
       0  985.34  108.39  972.85  215.74  964.11  308.95  954.64   325.9  953.66
  337.09  954.27  367.12  951.46  405.73  951.06  445.62  949.19  470.06   950.4
  503.41  947.66  515.19  944.85  519.97  943.33  526.38  942.33  532.69  943.33
  539.06  945.25  547.45  948.52     552  949.22  571.78  947.73  607.44  949.19
  645.35  955.59  692.15  959.92  813.17  964.88  816.56  965.67  831.35  966.16
  853.24  969.64   896.7  972.06  918.38  972.47     960  975.62  985.03  975.71
#Mann= 3 , 0 , 0
       0     .14       0  515.19     .05       0  539.06     .13       0
Bank Sta=515.19,539.06
Exp/Cntr=0.3,0.1

Type RM Length L Ch R = 1 ,12034.87,379.12,397.33,412.56
XS GIS Cut Line= 2
  1375013.271107   766992.202711  1374353.820571   767235.855114
#Sta/Elev= 30
       0  985.59   63.37  968.76      80  962.69   96.72  957.98   107.9  954.98
  124.44  951.59  140.38  945.12  148.31  941.94  154.49  940.94  159.48  941.93
  168.11  945.15  176.44  947.71  186.21  948.99  220.08  946.82  274.04  947.62
  373.17  946.56  397.21  947.08  404.95     948  440.86  949.17  466.46  948.49
  491.94  947.02   510.2  951.67  534.05  956.24  543.83  957.48  575.52  967.44
  592.35  969.83  628.07  977.27  637.44  978.59  664.01  979.33  703.02  982.64
#Mann= 3 , 0 , 0
       0     .15       0  140.38     .05       0  168.11     .13       0
#XS Ineff= 2 , 0
                          187.86          949.76
Permanent Ineff=
       F       F
Bank Sta=140.38,168.11
Exp/Cntr=0.3,0.1

Type RM Length L Ch R = 1 ,11637.53,415.88,421.22,425.34
XS GIS Cut Line= 3
   1375015.29574   766864.634878  1374665.128475   766801.174153
  1374326.534043   766739.810751
#Sta/Elev= 30
       0  995.03   11.21  993.23   18.91  993.37   34.13  991.66   91.81  976.88
  107.79  973.73  152.11  960.36  189.25  951.24  228.22  946.07  239.04  945.36
  280.21  943.87  311.61  944.42   325.3  945.44  345.57  941.54  359.62  938.28
  366.03  939.28   372.8   941.9  380.66  944.87  404.83  943.53  453.13  943.68
   458.2  945.29  476.83   947.5  497.94  952.57  522.17  955.22  540.21  962.06
  553.05  965.56  560.23  966.79  597.26  971.78  657.45  976.76  699.98  981.05
#Mann= 3 , 0 , 0
       0     .15       0  345.57     .05       0   372.8     .15       0
Bank Sta=345.57,372.8
Exp/Cntr=0.3,0.1

Type RM Length L Ch R = 1 ,11216.31,543.24,535.38,526.42
XS GIS Cut Line= 3
  1375132.265672   766524.531119  1374773.194588   766406.706357
  1374424.987016   766283.148832
#Sta/Elev= 30
       0  997.57   27.49  995.66    61.2  992.07  114.34  985.28  156.17   981.1
  181.07  977.16  229.29  968.59  281.76   956.1  316.85  946.23  333.16  943.62
  339.45  943.19  361.11  935.61  373.92  934.25  384.62   936.3  391.42   937.7
  397.46  939.94  413.24   940.4  439.59  943.29  447.18  945.98  453.13  947.25
  532.17  958.24  558.22  959.96  574.55   959.8  587.17  958.68  607.98     958
  618.39  957.94  645.05  959.41  701.29  966.14  721.54  967.22  747.39  971.48
#Mann= 3 , 0 , 0
       0     .15       0  361.11     .05       0  384.62     .15       0
Bank Sta=361.11,384.62
Exp/Cntr=0.3,0.1

Type RM Length L Ch R = 1 ,10680.93,606.8,620.34,632.72
XS GIS Cut Line= 2
  1375079.936801    765895.52043  1374450.243684   765864.871641
#Sta/Elev= 30
       0  994.31   14.72  991.77    40.3  985.74   47.24  984.94   60.96  979.97
   80.27  974.82  116.94  962.18  141.07   952.2  166.48  938.39   174.4  936.39
  192.21  935.69  198.31  936.27  218.29  932.36  234.97  929.56  242.28  931.08
  253.43  936.25   270.5  935.71   315.8  937.23  337.24  936.97  346.32  938.26
  395.34  939.51   420.5  941.06  444.27  943.41  462.73  948.12  475.07  950.65
  482.96  953.19  545.96     967     564  969.68   601.9  976.54  630.44  979.77
#Mann= 3 , 0 , 0
       0     .15       0  218.29     .05       0  242.28     .15       0
Bank Sta=218.29,242.28
Exp/Cntr=0.3,0.1

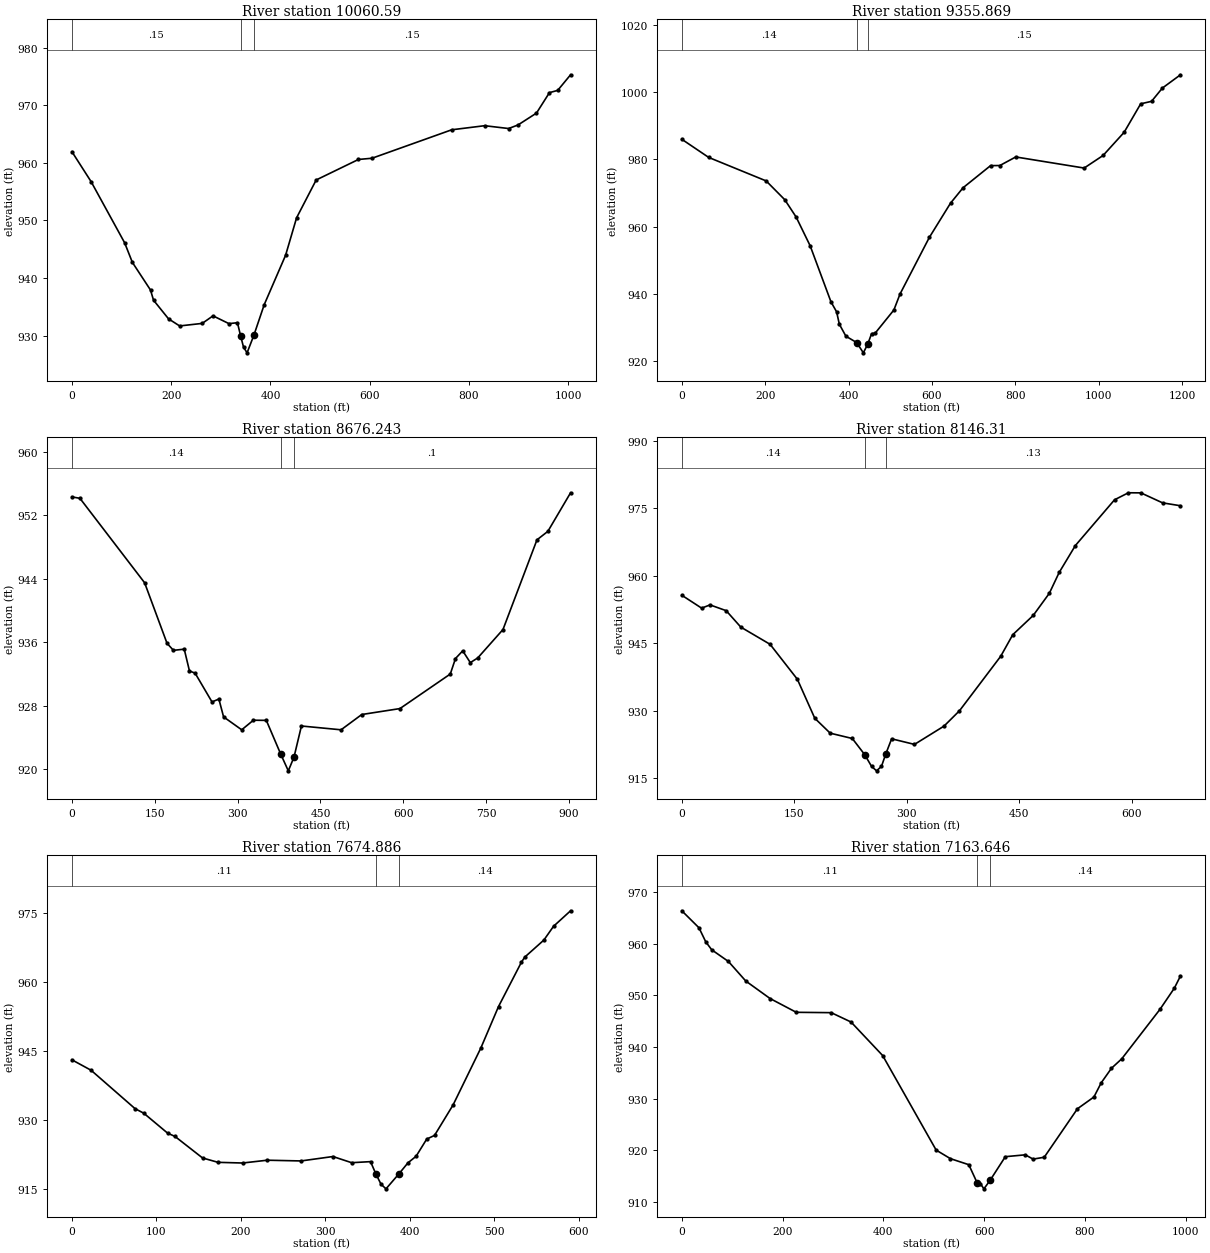
Type RM Length L Ch R = 1 ,10060.59,707.3,704.72,698.16
XS GIS Cut Line= 3
  1375093.868069   765474.238995  1374787.380258   765304.277555
  1374205.053425   765006.148504
#Sta/Elev= 30
       0  961.93   38.59  956.74  106.24  946.11  121.77  942.72  158.38  937.91
  164.41  936.15  194.69  932.91  217.03  931.68  262.48  932.12  284.29  933.43
  316.42  932.08  333.49  932.24  339.76     930  345.75     928   352.9  927.01
  366.59  930.06  387.52  935.39  430.52  943.95  452.69  950.46  492.14  957.02
  577.31  960.58  604.59  960.79  765.18  965.73  831.57  966.44  879.88  965.95
  898.81  966.57  935.98  968.63  962.08  972.18  978.69  972.57 1004.67  975.28
#Mann= 3 , 0 , 0
       0     .15       0  339.76     .05       0  366.59     .15       0
Bank Sta=339.76,366.59
Exp/Cntr=0.3,0.1

Type RM Length L Ch R = 1 ,9355.869,668.75,679.63,660.51
XS GIS Cut Line= 3
  1375757.907676   765100.565059  1375365.507113   764949.641762
  1374647.866858   764655.643172
#Sta/Elev= 30
       0  985.99   64.52  980.59  202.28   973.6   246.9  968.01   274.2  962.85
  307.84  954.29  357.79   937.6  371.28  934.64  377.79  930.97  393.57  927.39
  419.41  925.51  435.36  922.45  445.92  925.05  455.11  928.15  463.73  928.31
   508.6   935.2  523.36  939.96   593.7  956.81  644.42  966.98  674.54  971.57
  740.48  978.15  762.74  978.18  800.84  980.73  964.92  977.43 1010.31  981.17
 1060.72  988.05 1100.54  996.54 1126.56  997.28 1152.56 1001.23 1195.95 1005.18
#Mann= 3 , 0 , 0
       0     .14       0  419.41     .05       0  445.92     .15       0
Bank Sta=419.41,445.92
Exp/Cntr=0.3,0.1

Type RM Length L Ch R = 1 ,8676.243,484.77,529.93,506.38
XS GIS Cut Line= 3
   1376035.62153   764675.977564  1375687.339942   764503.229871
   1375194.17317   764358.344739
#Sta/Elev= 30
       0  954.34   14.52  954.16  131.63   943.5  172.19  935.86   183.8  934.97
  203.35  935.12   212.8  932.37  223.03  932.09  253.62  928.46  266.07  928.82
  274.58  926.57  307.41  924.94  328.54  926.15  351.96  926.13  377.72  921.92
  391.76  919.76  402.05  921.49  415.51  925.42  487.27  924.94  524.75  926.87
  593.88  927.62     685  931.98  694.42  933.94  707.52  934.91  721.25  933.42
  734.68  934.01  780.43   937.6  841.93  948.92  861.65  949.99  902.78  954.86
#Mann= 3 , 0 , 0
       0     .14       0  377.72     .05       0  402.05      .1       0
Bank Sta=377.72,402.05
Exp/Cntr=0.3,0.1

Type RM Length L Ch R = 1 ,8146.31 ,463.91,471.42,479.05
XS GIS Cut Line= 3
  1376168.362556   764400.616112  1375945.663725   764264.195356
   1375598.09013   764058.452662
#Sta/Elev= 30
       0  955.68   26.44  952.82   37.61  953.54   59.14  952.26   78.67  948.61
  117.72  944.79  154.07  937.04  177.34  928.37  197.91  925.06  227.38  923.88
  243.85  920.31  253.02   917.7  259.71   916.7  266.31   917.7  271.97  920.43
  279.83  923.81   310.3  922.57  349.69  926.63  370.33  930.04  425.33  942.14
  441.37  946.92   468.7  951.21  490.16  956.12  503.27  960.74  524.89  966.72
  577.16  976.88  595.61  978.43  612.24  978.41  641.21  976.19  665.06  975.55
#Mann= 3 , 0 , 0
       0     .14       0  243.85     .05       0  271.97     .13       0
Bank Sta=243.85,271.97
Exp/Cntr=0.3,0.1

Type RM Length L Ch R = 1 ,7674.886,503,511.24,519
XS GIS Cut Line= 4
  1376355.284502   764061.800463  1376173.219787   763974.058417
  1376039.413169   763868.767973  1375901.219451   763699.864557
#Sta/Elev= 30
       0  943.16   22.72  940.89   74.85  932.54   85.05  931.57  113.35  927.23
  122.13  926.51   154.7  921.84  173.01  920.89   202.1  920.74  231.37  921.35
  271.38  921.19  309.15  922.15  331.29  920.81  353.69  921.04  359.94  918.39
  366.15  916.12     372  915.13  387.45  918.42     398  920.78  407.61   922.2
  420.22  925.94  429.47  926.74  451.46  933.36  484.27   945.7  505.24  954.73
  532.44  964.39  536.38  965.48  558.98  969.18  570.47  972.18   590.6  975.54
#Mann= 3 , 0 , 0
       0     .11       0  359.94     .05       0  387.45     .14       0
Bank Sta=359.94,387.45
Exp/Cntr=0.3,0.1

Type RM Length L Ch R = 1 ,7163.646,597.26,593.15,580.32
XS GIS Cut Line= 4
  1376470.247381   764334.903269  1376359.845486   763927.690705
  1376413.308269   763699.582822  1376410.123274     763366.4448
#Sta/Elev= 30
       0  966.37   34.04  963.08   47.46  960.37   59.36  958.82   92.51  956.56
  126.91  952.78  175.02   949.4  227.09  946.73  296.45  946.66  335.76  944.85
  398.44  938.37  504.67  920.07  532.89  918.42  569.39  917.25  586.44  913.64
  592.47  913.57  599.36  912.58  611.67  914.23  641.83   918.8  681.47  919.16
  696.91  918.33  719.02  918.69  784.94  928.07  817.65  930.35  832.08  933.09
  852.48  935.91  872.82  937.73  948.66   947.3  977.25  951.41  989.36  953.77
#Mann= 3 , 0 , 0
       0     .11       0  586.44     .05       0  611.67     .14       0
Bank Sta=586.44,611.67
Exp/Cntr=0.3,0.1

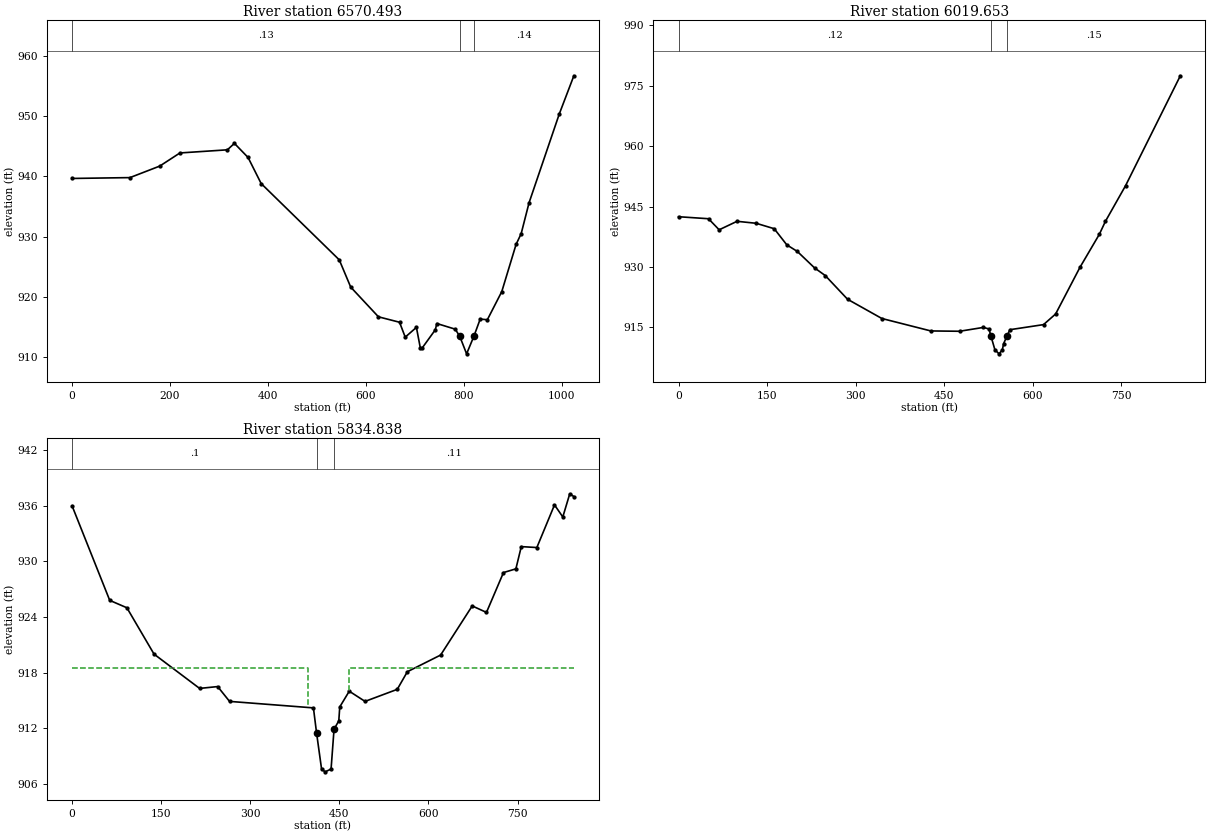
Type RM Length L Ch R = 1 ,6570.493,560.41,550.84,517.53
XS GIS Cut Line= 5
  1376885.476114   764259.407148  1376876.765034   763728.030519
  1376795.461508   763533.482798  1376787.874095   763423.465315
  1376705.446877   763272.150037
#Sta/Elev= 30
       0  939.67   118.2  939.81  179.06  941.72  220.33   943.9  317.28  944.42
  331.57  945.49  359.47  943.15  386.25  938.82  545.72  926.17  569.11  921.65
  625.78  916.72  668.83  915.82  680.47  913.35  703.31  914.97  711.28  911.57
  714.45  911.48  741.94  914.57     745  915.61  782.67  914.67  791.92  913.47
  805.81  910.58  821.03  913.56  833.54  916.34  848.21  916.24  877.65   920.9
  906.91  928.74  917.27  930.51  933.31  935.62  995.08  950.36 1024.89   956.7
#Mann= 3 , 0 , 0
       0     .13       0  791.92     .05       0  821.03     .14       0
Bank Sta=791.92,821.03
Exp/Cntr=0.3,0.1

Type RM Length L Ch R = 1 ,6019.653,174.02,184.82,190.63
XS GIS Cut Line= 3
   1377452.28134   763541.986263  1377076.725109    763152.12681
  1376856.650922   762935.815316
#Sta/Elev= 30
       0  942.48   50.76  941.98    68.8  939.23   99.09  941.34  131.48  940.85
  162.06   939.5  183.38  935.49  201.21  933.85  230.34  929.77   248.5  927.86
  286.31  921.97   344.4  917.19  427.32   914.1  476.06  914.02  516.07  914.97
  525.88   914.6  529.12  912.82  535.89  909.41  542.92  908.41  548.44  909.41
  550.62  910.94  556.24  912.82  561.29  914.41   618.2  915.67  638.67  918.31
   679.9   929.9   712.7   938.1  723.14  941.36  757.18   950.2  849.91   977.5
#Mann= 3 , 0 , 0
       0     .12       0  529.12     .05       0  556.24     .15       0
Bank Sta=529.12,556.24
Exp/Cntr=0.5,0.3

Type RM Length L Ch R = 1 ,5834.838,56.18,56.06,55.9
BEGIN DESCRIPTION:
Upstream xs of Bridge 37003-0079
END DESCRIPTION:
XS GIS Cut Line= 6
  1377400.486344   763415.106814  1377225.395066   763093.759591
   1377108.41174   762882.926875  1377057.696953   762781.451191
  1377021.610973   762713.483056   1376997.32765   762673.048311
#Sta/Elev= 30
       0     936    63.4   925.8    92.3     925     138     920   214.7   916.3
   245.1   916.5   265.1   914.9   406.3   914.2   411.6  911.49     420   907.6
     426   907.3     436   907.6     441   911.9     449   912.8   450.6   914.3
   466.6     916   493.2   914.9   547.4   916.2   564.4   918.1   620.4   919.9
   673.6   925.2   697.6   924.5   726.2   928.8   747.1   929.2   756.2   931.6
   782.4   931.5   812.1   936.1   826.1   934.8   837.8   937.3   844.7     937
#Mann= 3 , 0 , 0
       0      .1       0   411.6     .05       0     441     .11       0
#XS Ineff= 2 , 0
       0   397.2   918.5   466.8       0   918.5
Permanent Ineff=
       F       F
Bank Sta=411.6,441
Exp/Cntr=0.5,0.3