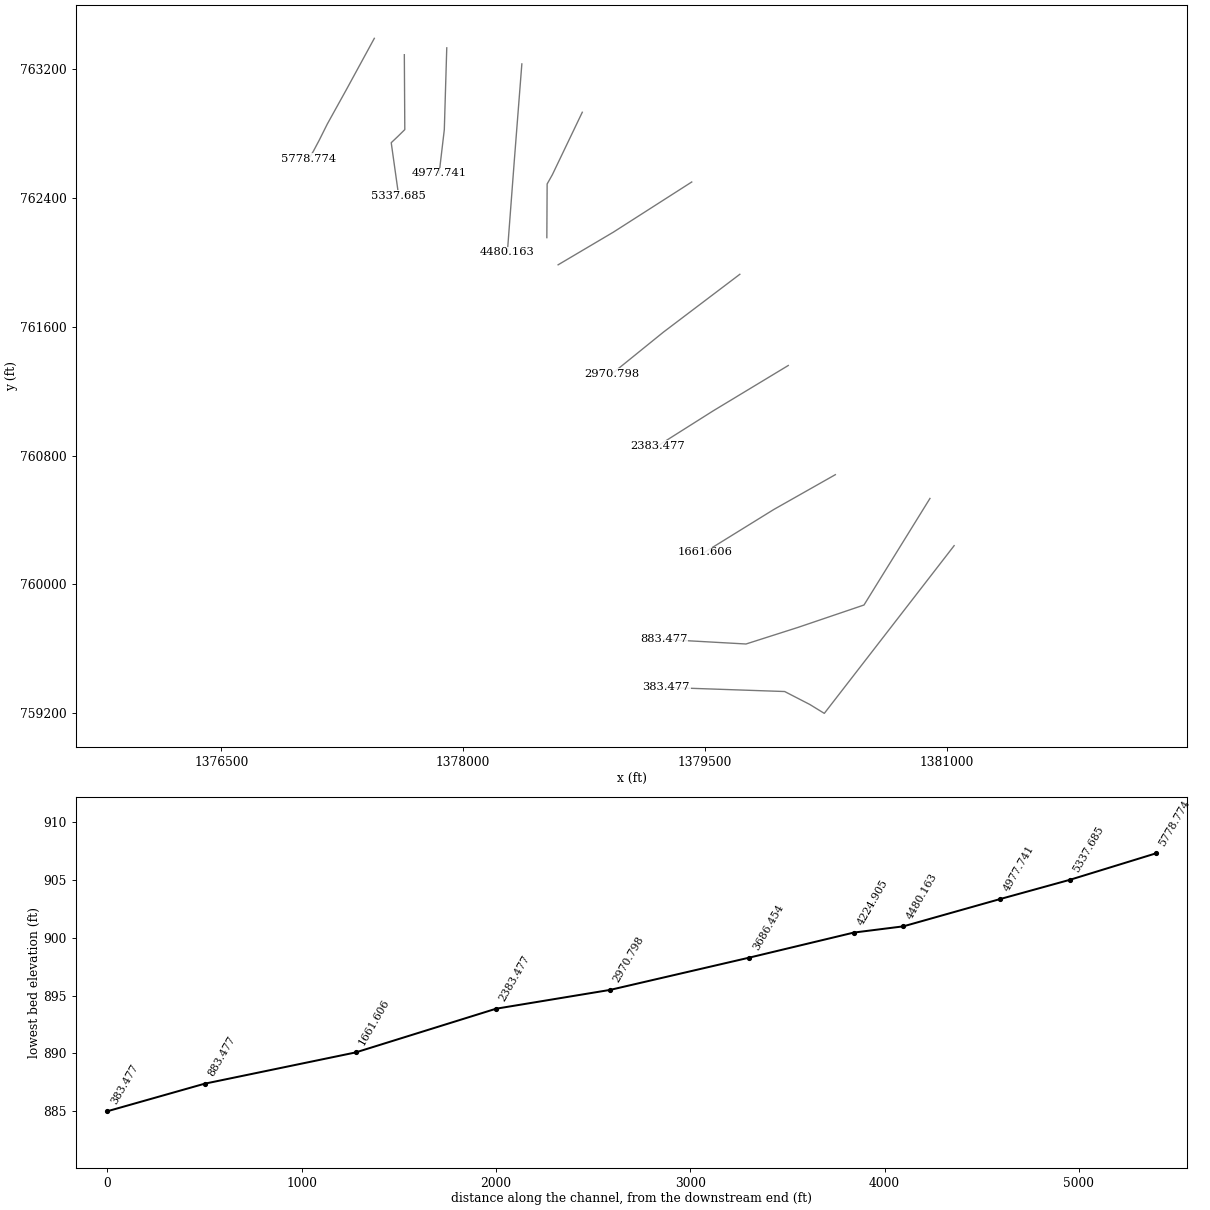
HEC-RAS study BigBranch.prj: BigBranch

--- BigBranch.g01 (geometry) --- (continued)

Type RM Length L Ch R = 3 ,5809.015,,,
BEGIN DESCRIPTION:
Bridge : 37003-0079 (Drumstand Road)
END DESCRIPTION:
Bridge Culvert--1,0,-1,-1, 0
Deck Dist Width WeirC Skew NumUp NumDn MinLoCord MaxHiCord MaxSubmerge Is_Ogee
16.8,18,2.6,0, 130, 130, , , 0.95, 0, 0,0,,
   -37.9   -31.2   -27.4   -20.9   -11.3    -9.7    -4.8      .8     9.8    11.5
    14.2    21.2    26.9    32.5    42.5      53      57    63.2    71.7    73.9
    79.5    83.1    83.8    95.5   105.2   110.2   116.9   124.4   127.6   132.9
   138.7   141.6   149.5   149.6   150.6   170.5   176.8     183   191.4   194.1
   200.2   205.7   207.5   220.3   230.6   237.2   242.3   248.6   256.3   268.2
   270.7   271.3   280.6   297.4   324.5   327.8   340.4   348.4   356.6   360.9
   366.5     414     414     450     450   458.5   465.1   471.7   475.1   484.8
   485.8     490   498.5   499.6   508.7   513.7   518.6   527.2   530.1   535.1
   539.6   549.1   551.4   555.6   561.8   566.4   568.7   574.1   580.8   584.2
   593.1   597.2   598.4   607.9   611.9   620.2   627.2   631.8     638   644.8
   654.6   655.8   659.1   668.9     671   679.1   681.8   690.1   691.9   701.4
   703.2   712.4   715.9   721.8   727.3   731.9     740   746.9   750.7   757.5
   759.7   763.5   766.2     774   776.8   786.3   791.5     797   807.7   808.7
   931.4   930.9   930.6   930.2   929.5   929.3   929.2   928.9   928.4   928.3
   928.1   927.6   927.3   926.9   926.5     926   925.7   925.4     925   924.8
   924.6   924.3   924.3   923.9   923.4   923.2     923   922.6   922.5   922.3
     922   921.8   921.6   921.6   921.5     921   920.9   920.8   920.4   920.3
   920.3   920.2   920.1     920   919.7   919.6   919.5   919.3   919.2   919.1
     919     919   918.9   918.7   918.6   918.6   918.5   918.6   918.5   918.5
   918.4   918.6   918.6   918.6   918.6   918.8   918.9     919   919.1   919.4
   919.4   919.5   919.8   919.8   920.1   920.1   920.2   920.6   920.5   920.7
   920.7     921   921.1   921.2   921.2   921.6   921.6   921.8   922.2   922.4
   922.7   922.8   922.9   923.3   923.5   923.8   924.1   924.3   924.5   924.8
   925.4   925.5   925.7     926   926.2   926.6   926.8   927.4   927.5   927.9
     928   928.6     929   929.3   929.6   929.9   930.5   930.9   931.2   931.8
   931.9   932.3   932.4   932.8   932.9   933.7     934   934.3   935.3   935.4
                                                                                
                                                                                
                                                                                
                                                                                
                                                                                
                                                                                
                   916.6   916.6
                                                                                
                                                                                
                                                                                
                                                                                
                                                                                
                                                                                
   -30.5   -23.8   -19.9   -13.5    -3.9    -2.2     2.6     8.2    17.2    18.9
    21.6    28.6    34.4    39.9    49.9    60.5    64.4    70.6    79.2    81.3
    86.9    90.6    91.2   102.9   112.6   117.6   124.4   131.8     135   140.3
   146.2     149     157     157     158   177.9   184.2   190.4   198.8   201.5
   207.6   213.1   214.9   227.7     238   244.6   249.7   256.1   263.7   275.7
   278.1   278.7   288.1   304.8   331.9   335.2   347.8   355.8     364   368.3
   373.9     421     421     457     457   465.9   472.6   479.1   482.5   492.2
   493.2   497.4   505.9     507   516.1   521.1     526   534.6   537.5   542.5
     547   556.5   558.8     563   569.3   573.8   576.1   581.5   588.2   591.6
   600.5   604.6   605.8   615.3   619.3   627.6   634.7   639.2   645.4   652.2
     662   663.3   666.5   676.3   678.5   686.5   689.2   697.6   699.3   708.9
   710.6   719.8   723.3   729.2   734.7   739.3   747.4   754.4   758.1   764.9
   767.1   770.9   773.7   781.4   784.2   793.7   798.9   804.4   815.1   816.1
   931.4   930.9   930.6   930.2   929.5   929.3   929.2   928.9   928.4   928.3
   928.1   927.6   927.3   926.9   926.5     926   925.7   925.4     925   924.8
   924.6   924.3   924.3   923.9   923.4   923.2     923   922.6   922.5   922.3
     922   921.8   921.6   921.6   921.5     921   920.9   920.8   920.4   920.3
   920.3   920.2   920.1     920   919.7   919.6   919.5   919.3   919.2   919.1
     919     919   918.9   918.7   918.6   918.6   918.5   918.6   918.5   918.5
   918.4   918.6   918.6   918.6   918.6   918.8   918.9     919   919.1   919.4
   919.4   919.5   919.8   919.8   920.1   920.1   920.2   920.6   920.5   920.7
   920.7     921   921.1   921.2   921.2   921.6   921.6   921.8   922.2   922.4
   922.7   922.8   922.9   923.3   923.5   923.8   924.1   924.3   924.5   924.8
   925.4   925.5   925.7     926   926.2   926.6   926.8   927.4   927.5   927.9
     928   928.6     929   929.3   929.6   929.9   930.5   930.9   931.2   931.8
   931.9   932.3   932.4   932.8   932.9   933.7     934   934.3   935.3   935.4
                                                                                
                                                                                
                                                                                
                                                                                
                                                                                
                                                                                
                   916.6   916.6
                                                                                
                                                                                
                                                                                
                                                                                
                                                                                
                                                                                
Pier Skew, UpSta & Num, DnSta & Num=  ,432, 2 ,439, 2 , 0 , 0 , 0 ,,
       1       1
   906.4   917.1
       1       1
   906.4   917.1
BR Coef=-1 , 1 , 0 ,, 0 ,,,0.8,0,1.2,0,
WSPro=,,,, 1 ,,,, 0 ,,,, 0 ,,,,-1 ,-1 ,-1 , 0 , 0 , 0 , 0 , 0
BC Design=,, 0 ,, 0 ,,,,,,

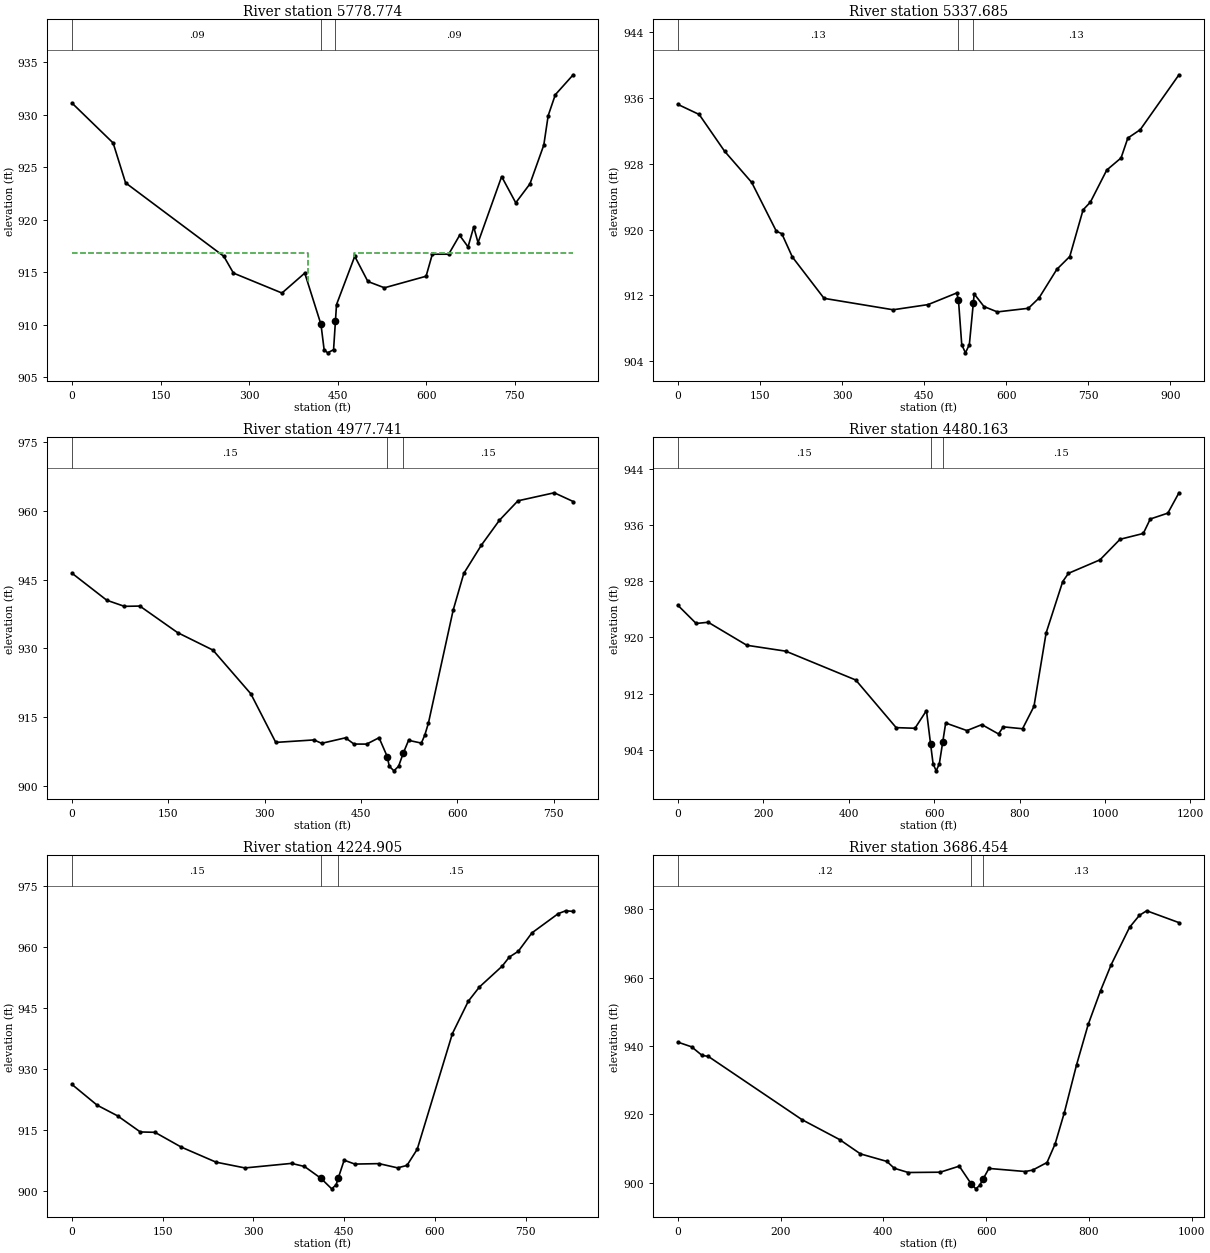
Type RM Length L Ch R = 1 ,5778.774,433,441.089,449
BEGIN DESCRIPTION:
Down stream xs of Bridge 37003-0079
END DESCRIPTION:
XS GIS Cut Line= 6
  1377448.469467   763388.225244   1377273.73316    763067.51993
  1377156.969257   762857.057608  1377106.592304   762756.257876
  1377069.508506   762686.410359   1377043.16466   762642.544564
#Sta/Elev= 30
       0   931.1    69.6   927.3    90.7   923.5   257.1   916.5   273.4   914.9
   355.6     913   394.2   914.9  421.67910.0077     427   907.6     433   907.3
     443   907.6  446.19  910.35     448   911.9   478.9   916.5   501.1   914.1
   529.2   913.5   599.7   914.6   610.3   916.7     638   916.7   656.5   918.5
   670.8   917.4   680.4   919.3   687.7   917.8   727.7   924.1   751.6   921.6
   775.6   923.4   799.1   927.1   806.5   929.9   818.6   931.9   848.9   933.8
#Mann= 3 , 0 , 0
       0     .09       0  421.67     .05       0  446.19     .09       0
#XS Ineff= 2 , 0
       0   399.7   916.8   478.3       0   916.8
Permanent Ineff=
       F       F
Bank Sta=421.67,446.19
Exp/Cntr=0.5,0.3

Type RM Length L Ch R = 1 ,5337.685,332.55,359.95,378.75
XS GIS Cut Line= 5
  1377634.630053   763286.668521  1377637.533755   762822.076933
  1377593.103838   762778.384085  1377553.326527   762740.773408
  1377599.785681   762409.751903
#Sta/Elev= 30
       0  935.25   39.08  934.02   85.48  929.55  135.09  925.75  180.04  919.82
  190.17  919.51  209.27  916.69   267.3  911.65  393.47  910.26  457.44  910.89
   509.6   912.3  512.89  911.48  518.91  906.02  525.66  905.02  532.82  906.02
  540.18  911.14  541.64  912.19  559.61  910.65  583.95     910  640.71  910.44
   659.9  911.67  692.71  915.18  716.35  916.74   740.7  922.42  753.99  923.35
  783.96  927.26  810.07  928.73  822.46  931.15  845.15  932.17  915.92  938.85
#Mann= 3 , 0 , 0
       0     .13       0  512.89     .05       0  540.18     .13       0
Bank Sta=512.89,540.18
Exp/Cntr=0.3,0.1

Type RM Length L Ch R = 1 ,4977.741,496.94,497.58,496.96
XS GIS Cut Line= 3
   1377897.84537   763329.217078  1377882.668905    762821.87054
  1377850.666286   762550.896708
#Sta/Elev= 30
       0  946.36   54.08  940.49   81.48  939.16  105.61  939.22  164.25  933.45
  219.38  929.64  278.43  920.12  317.25  909.54   376.8  910.08  388.69  909.34
  425.91  910.54  439.03  909.18  458.77  909.17  478.09  910.56   490.8  906.47
  494.03  904.35  501.25  903.35  508.49  904.34  516.02  907.28  524.07  909.99
  543.97  909.39  549.36  911.14  555.03  913.78  593.51  938.33  610.06  946.32
  637.44  952.48  665.63  957.91  694.36  962.13  750.92  963.88  780.43  961.98
#Mann= 3 , 0 , 0
       0     .15       0   490.8     .05       0  516.02     .15       0
Bank Sta=490.8,516.02
Exp/Cntr=0.3,0.1

Type RM Length L Ch R = 1 ,4480.163,266.28,255.26,241.86
XS GIS Cut Line= 3
  1378363.686031   763229.536383  1378316.558961   762625.453007
  1378273.716184   762059.928167
#Sta/Elev= 30
       0   924.6   42.93     922   71.16  922.17  161.61  918.89   252.7  918.05
  416.49  913.94  511.09  907.15  555.14  907.06  582.01  909.58  591.68   904.8
  597.53  901.99  604.82  900.99  612.11  901.99  620.12   905.1  627.01  907.81
  676.69  906.73  711.66  907.58  750.66  906.25  761.97  907.26  806.94  906.99
  833.66  910.18  862.06  920.64  900.99  927.98  914.45  929.15  988.16  931.07
 1035.15     934 1089.56  934.83 1105.87  936.89 1147.03  937.73 1173.06  940.63
#Mann= 3 , 0 , 0
       0     .15       0  591.68     .05       0  620.12     .15       0
Bank Sta=591.68,620.12
Exp/Cntr=0.3,0.1

Type RM Length L Ch R = 1 ,4224.905,555.18,538.45,522.5
XS GIS Cut Line= 4
  1378738.661938   762929.720559  1378552.973252   762542.206277
  1378520.540865   762484.684631  1378518.699712   762151.706007
#Sta/Elev= 30
       0  926.11   41.54  921.02   75.31   918.4  112.89  914.44  137.11  914.35
  180.55  910.72  238.13  907.01  286.02  905.59  363.03  906.71  384.32  905.95
  411.43  903.06  429.39  900.45   436.7  901.45  440.38  903.17  449.98   907.5
  467.61  906.54  507.58  906.65  538.31  905.61  553.85  906.21  570.82  910.19
  628.98  938.63  655.28  946.59  673.67  950.09  711.22   955.2  723.02  957.44
  737.93  958.87  760.46  963.39  804.03  968.13  816.36  968.83  828.72  968.67
#Mann= 3 , 0 , 0
       0     .15       0  411.43     .05       0  440.38     .15       0
Bank Sta=411.43,440.38
Exp/Cntr=0.3,0.1

Type RM Length L Ch R = 1 ,3686.454,712.02,715.66,717.94
XS GIS Cut Line= 3
  1379417.641527   762497.045064  1378931.805946   762186.085058
  1378588.725691    761983.31007
#Sta/Elev= 30
       0  941.13    26.9  939.75   47.12  937.26   59.31  936.96  241.84  918.47
  314.98  912.66  355.43  908.49  406.86  906.29  421.25  904.29  448.49  903.05
  510.73  903.14  547.78  904.91  570.85  899.76  580.03  898.28  587.44  899.28
  593.68  901.03  605.49  904.24     676  903.34   690.6  903.75  718.56  905.97
  734.32   911.4  752.32  920.57  776.12  934.54  798.67  946.28  822.69  956.14
  843.35  963.73  879.17  974.65  898.38  978.16   912.5  979.49  975.35  976.03
#Mann= 3 , 0 , 0
       0     .12       0  570.85     .05       0  593.68     .13       0
Bank Sta=570.85,593.68
Exp/Cntr=0.3,0.1

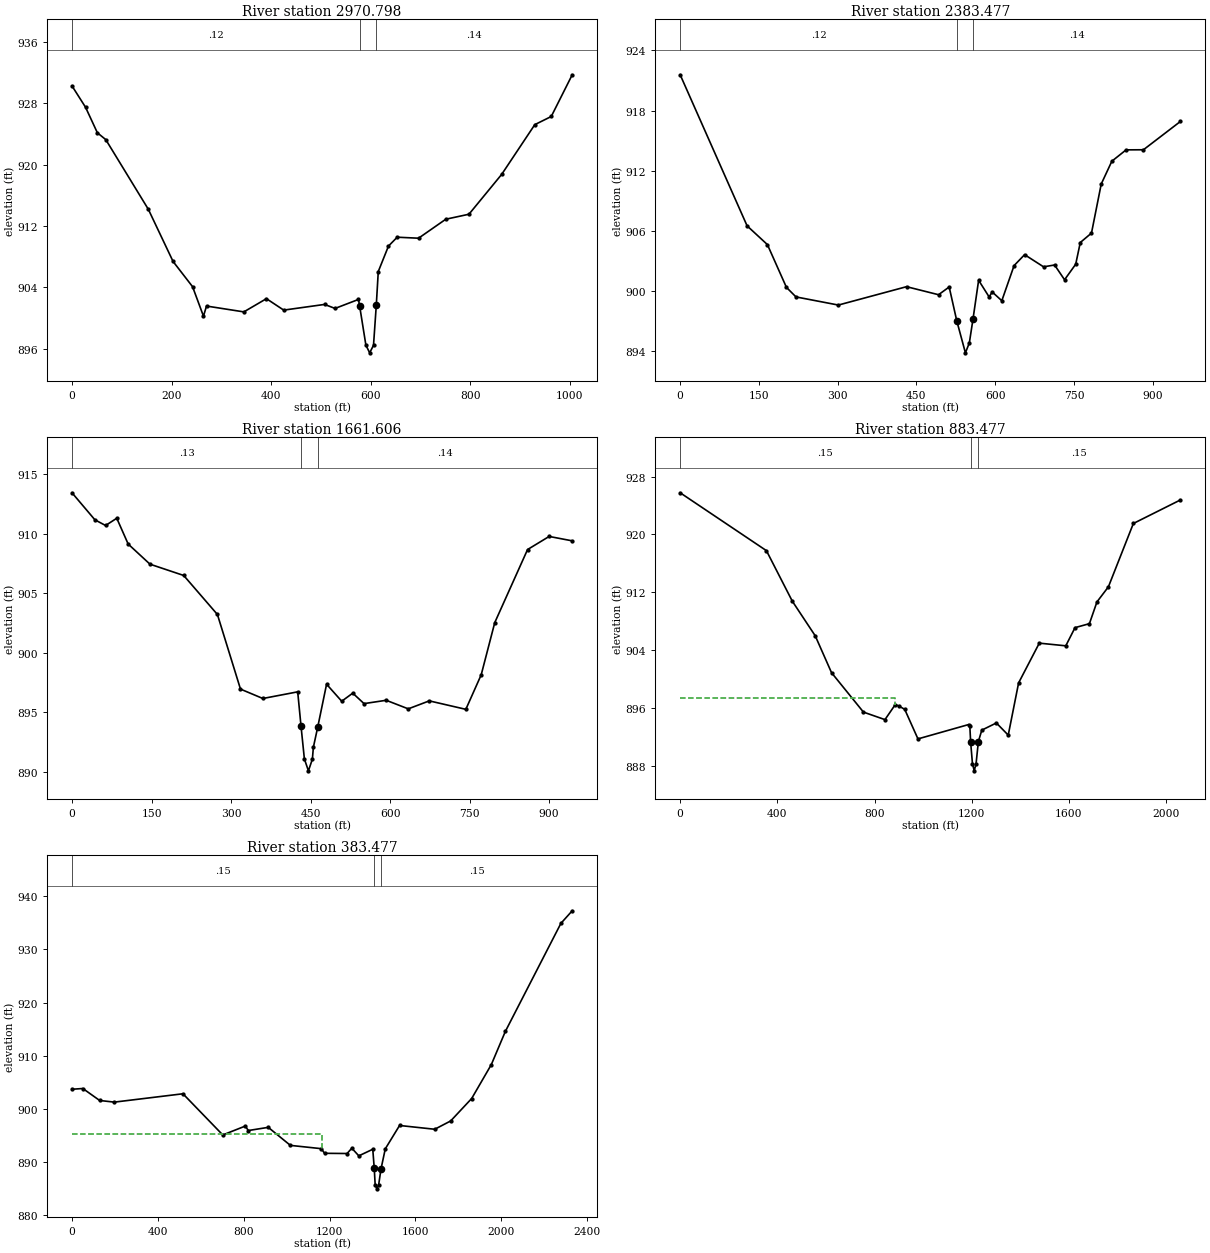
Type RM Length L Ch R = 1 ,2970.798,590.42,587.32,583.47
XS GIS Cut Line= 3
  1379715.985215    761924.46112  1379241.335921   761565.107936
  1378923.045531   761307.556723
#Sta/Elev= 30
       0  930.23   27.25  927.45   50.98  924.13   67.87  923.24  153.27  914.18
  203.04  907.38  242.18   904.1   264.1  900.26  270.19  901.58   345.2  900.82
  390.57  902.54  425.29  901.05  507.31  901.79  528.41  901.27  575.39  902.44
  577.62  901.65  590.34  896.49  597.92  895.49  605.64  896.47  611.19  901.66
   615.2  906.07  635.73  909.39  653.24  910.54  696.11  910.41  750.81  912.88
  797.35  913.53  863.11  918.72   929.6  925.19  962.65  926.25 1004.78  931.68
#Mann= 3 , 0 , 0
       0     .12       0  577.62     .05       0  611.19     .14       0
Bank Sta=577.62,611.19
Exp/Cntr=0.3,0.1

Type RM Length L Ch R = 1 ,2383.477,722.38,721.87,721.49
XS GIS Cut Line= 3
  1380016.496055   761358.660552  1379551.480732   761077.760168
  1379205.300239   760859.038641
#Sta/Elev= 30
       0  921.56  127.47  906.51  166.18  904.64  202.42  900.38  220.61  899.43
  301.29  898.62  431.16  900.45   492.1  899.65  512.36  900.42  526.77  897.06
  543.27  893.86  550.77  894.85  557.73  897.22  568.44  901.09  588.55  899.42
  594.23  899.93   612.6  899.05  635.97  902.55  656.01  903.64  692.07  902.43
  713.14  902.61  732.12  901.14  753.36  902.69  762.06  904.85  783.41  905.79
  801.97  910.68  822.21  912.95  849.34  914.08  882.36  914.09  952.76  916.91
#Mann= 3 , 0 , 0
       0     .12       0  526.77     .05       0  557.73     .14       0
Bank Sta=526.77,557.73
Exp/Cntr=0.3,0.1

Type RM Length L Ch R = 1 ,1661.606,780.53,778.13,767.05
XS GIS Cut Line= 3
  1380308.513105   760681.317412  1379926.950021   760465.455869
  1379497.340175   760199.768283
#Sta/Elev= 30
       0  913.45   43.16  911.18   63.37   910.7   84.45  911.31  105.98  909.14
  147.05  907.45   210.7   906.5   274.3  903.22   317.8  896.95  360.01  896.16
  425.73  896.72  432.04  893.81  438.33  891.08  445.96  890.08  453.41  891.06
  455.28  892.06  463.61  893.78  480.18  897.36  508.75  895.93  529.56  896.61
  550.84  895.73  592.65  896.01  634.27  895.29  673.92  895.96  742.85  895.25
  771.83  898.15  797.43  902.54  859.29  908.68  900.01  909.78  943.52  909.41
#Mann= 3 , 0 , 0
       0     .13       0  432.04     .05       0  463.61     .14       0
Bank Sta=432.04,463.61
Exp/Cntr=0.3,0.1

Type RM Length L Ch R = 1 ,883.477 ,526.33,500,476.02
XS GIS Cut Line= 5
  1380895.414524   760533.830105  1380486.203516   759872.731286
  1380076.458034   759733.712569  1379754.313249   759630.884016
  1379244.733994   759659.331635
#Sta/Elev= 30
       0  925.76  354.93  917.77  461.39   910.8  555.89  906.01  622.96  900.92
  754.24  895.48  842.82  894.44  885.39  896.52  901.64  896.29  924.16  895.86
   978.6  891.78 1187.12  893.76 1192.01  893.61 1195.47  891.32 1202.89  888.37
 1210.19  887.37 1217.78  888.36 1227.27  891.41 1241.34  892.99 1301.33  893.98
 1350.16   892.3 1392.83  899.51 1477.97     905 1587.02  904.63    1625  907.14
 1684.27  907.69 1715.24  910.69 1762.47  912.78  1865.1  921.52 2058.72  924.77
#Mann= 3 , 0 , 0
       0     .15       0 1195.47     .05       0 1227.27     .15       0
#XS Ineff= 2 , 0
          884.88  897.48
Permanent Ineff=
       F       F
Bank Sta=1195.47,1227.27
Exp/Cntr=0.3,0.1

Type RM Length L Ch R = 1 ,383.477 ,405.2,383.48,419.38
XS GIS Cut Line= 5
  1381045.476411   760240.950735  1380239.996012   759200.464463
  1380150.436376   759255.476598  1379994.078592    759335.99853
  1379260.257655    759361.27772
#Sta/Elev= 30
       0  903.71   50.49  903.85  128.99   901.6  197.29  901.29  517.06  902.86
  702.65  895.12  807.64  896.79  821.64  895.95  914.57  896.55 1017.69  893.16
 1162.11  892.54 1176.78  891.67 1281.92  891.63 1304.03  892.63 1336.57  891.19
 1401.62  892.43 1408.51  888.84 1412.87  885.69 1421.14  884.99    1429  885.72
 1439.91  888.71 1459.93  892.51 1526.49   896.9 1690.28  896.19 1764.59  897.75
 1862.49  901.97 1954.11  908.35 2019.55  914.59 2278.25  934.89 2331.07  937.26
#Mann= 3 , 0 , 0
       0     .15       0 1408.51     .05       0 1439.91     .15       0
#XS Ineff= 2 , 0
         1163.64  895.32
Permanent Ineff=
       F       F
Bank Sta=1408.51,1439.91
Exp/Cntr=0.3,0.1

Chan Stop Cuts=-1
Use User Specified Reach Order=0
User Specified Reach Order=BigBranch       ,Main