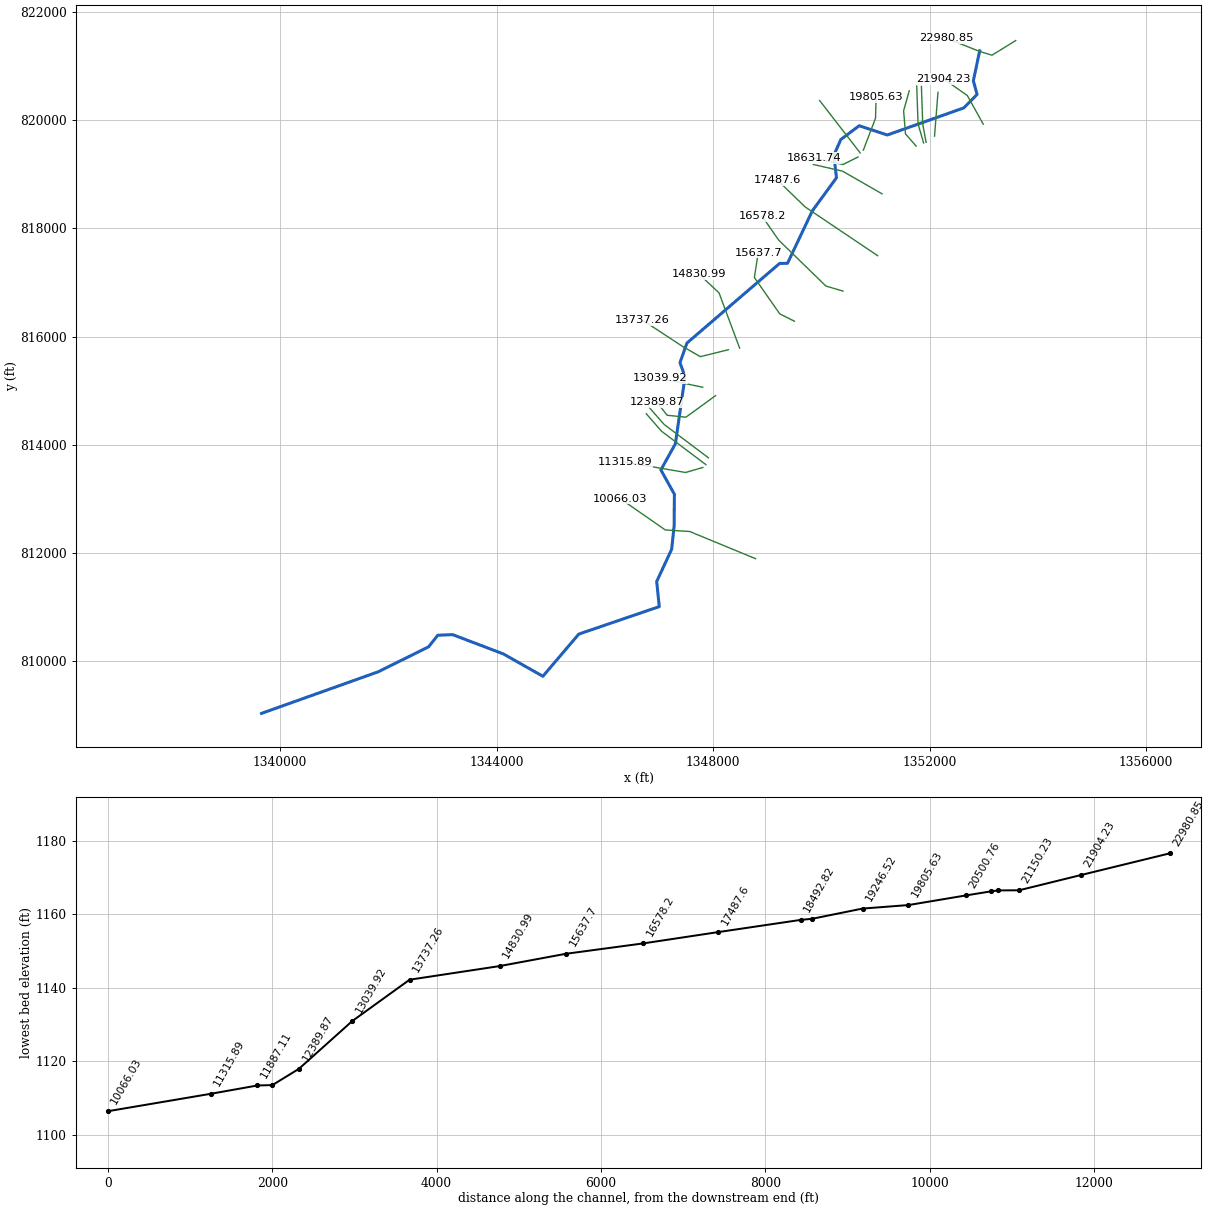
--- GrassyCreek.prj (project) ---

Proj Title=GrassyCreek
Current Plan=p01
Default Exp/Contr=0.3,0.1
English Units
Geom File=g01
Flow File=f01
Plan File=p01
Y Axis Title=Elevation
X Axis Title(PF)=Main Channel Distance
X Axis Title(XS)=Station
BEGIN DESCRIPTION:
END DESCRIPTION:
DSS Export Rating Curves= 0
DSS Export Rating Curve Sorted= 0
DSS Export Volume Flow Curves= 0
DXF OffsetX= 0
DXF OffsetY= 0
DXF ScaleX= 1
DXF ScaleY= 10

--- GrassyCreek.p01 (plan) ---

Plan Title=Approximate Study - 100 YR
Program Version=3.12
Short Identifier=100 Yr
Geom File=g01
Flow File=f01
Subcritical Flow
K Sum by GR= 0
Std Step Tol= 0.01
Critical Tol= 0.01
Num of Std Step Trials= 20
Max Error Tol= 0.3
Flow Tol Ratio= 0.001
Split Flow NTrial= 30
Split Flow Tol= 0.02
Split Flow Ratio= 0.02
Log Output Level= 0
Friction Slope Method= 1
Unsteady Friction Slope Method= 2
Unsteady Bridges Friction Slope Method= 1
Calc Critical at every XS
Parabolic Critical Depth
Global Vel Dist= 0 , 0 , 0
Global Log Level= 0
CheckData=True
Encroach Param=-1 ,0,0, 2
Encroach River=GrassyCreek
Encroach Reach=Main
Encroach Node=22980.85
       1     720  851.97
Encroach Node=21904.23
       1     445  538.82
Encroach Node=21150.23
       1     265     325
Encroach Node=20896.49
       1     390     436
Encroach Node=20809.72
       1     398     456
Encroach Node=20500.76
       1  348.29  524.81
Encroach Node=19805.63
       1     385  454.68
Encroach Node=19246.52
       1     360     428
Encroach Node=18631.74
       1     400     470
Encroach Node=18492.82
       1   880.2     950
Encroach Node=17487.6
       1 1289.02    1489
Encroach Node=16578.2
       1  935.07    1226
Encroach Node=15637.7
       1  806.96     998
Encroach Node=14830.99
       1  616.59     785
Encroach Node=13737.26
       1     795     868
Encroach Node=13039.92
       1  349.32   417.4
Encroach Node=12389.87
       1     832     885
Encroach Node=12068.4
       1     717     822
Encroach Node=11887.11
       1   667.5     755
Encroach Node=11315.89
       1     735     820
Encroach Node=10066.03
       1    1550    1645
Encroach Node=8565.117
       1     700     780
Encroach Node=7508.128
       1  400.26  504.29
Encroach Node=6734.532
       1     670     743
Encroach Node=5910.709
       1  937.97  990.83
Encroach Node=4796.162
       1  552.98  622.71
Encroach Node=3881.287
       1     345     410
Encroach Node=3045.541
       1     650  806.02
Encroach Node=2101.414
       1  756.68    1073
Encroach Node=1420.912
       1   681.3   918.1
Encroach Node=1282.49
       1   809.2  1041.3
Encroach Node=758.29
       1     890 1122.57
Computation Interval=1HOUR
Output Interval=1HOUR
Run HTab= 0
Run UNet= 0
Run PostProcess= 0
UNET Theta= 1
UNET Theta Warmup= 1
UNET ZTol= 0.02
UNET ZSATol= 0.05
UNET MxIter= 20
UNET MaxInSteps= 0
UNET DtIC= 0
UNET DtMin= 0
UNET MaxCRTS= 20
UNET WFStab= 2
UNET SFStab= 1
UNET WFX= 1
UNET SFX= 1
UNET DSS MLevel= 4
UNET DZMax Abort= 100
UNET Convert EG Bridges=-1
UNET Use Existing IB Tables=-1
UNET Froude Reduction=False
UNET Froude Limit= 1
UNET Froude Power= 10
Instantaneous Interval=1HOUR
Write IC File= 0
Echo Input=False
Echo Output=False
Write Detailed= 0
Detailed Automatic Start=False, 10

--- GrassyCreek.f01 (steady flow) ---

Flow Title=GrassyCreek
Program Version=3.12
Number of Profiles= 2
Profile Names=P100yr,PFW
River Rch & RM=GrassyCreek,Main            ,22980.85
    2120    2120
River Rch & RM=GrassyCreek,Main            ,21904.23
    2950    2950
River Rch & RM=GrassyCreek,Main            ,17487.6
    3380    3380
River Rch & RM=GrassyCreek,Main            ,10066.03
    3720    3720
River Rch & RM=GrassyCreek,Main            ,3045.541
    4180    4180
Boundary for River Rch & Prof#=GrassyCreek,Main            , 1
Up Type= 0
Dn Type= 3
Dn Slope=0.002656
DSS Import GetInterval= 0
DSS Import GetPeak= 0
DSS Import FillOption= 0

--- GrassyCreek.g01 (geometry) ---

Geom Title=USGS 10m DEM
Program Version=3.12

River Reach=GrassyCreek     ,Main
Reach XY= 30
  1352925.490668    821276.62151  1352808.629336   820724.629367
  1352877.884485   820472.438668  1352632.001635   820223.381358
  1351218.560695   819722.741271  1350699.631714   819893.751653
  1350360.978239   819640.143296  1350231.131243   819349.000077
  1350280.500327   818933.129064  1349833.385071   818320.691059
  1349375.315272   817352.561124  1349229.630531   817350.385508
  1347516.630104   815878.496115  1347389.129808   815517.130615
  1347482.129492   815256.690541  1347304.129627   814018.441064
  1347035.751517   813536.128893  1347285.607064    813086.41371
  1347281.017739   812500.818517  1347235.001417   812069.310318
  1346958.627903   811474.128742  1347006.501982   811010.441066
  1345519.336942   810502.482599  1344856.182508   809723.524723
  1344125.718272   810136.562094  1343190.631524   810492.243825
  1342914.249814   810481.635176  1342746.883138   810269.060984
  1341818.000069    809807.56038  1339658.880016   809038.061481

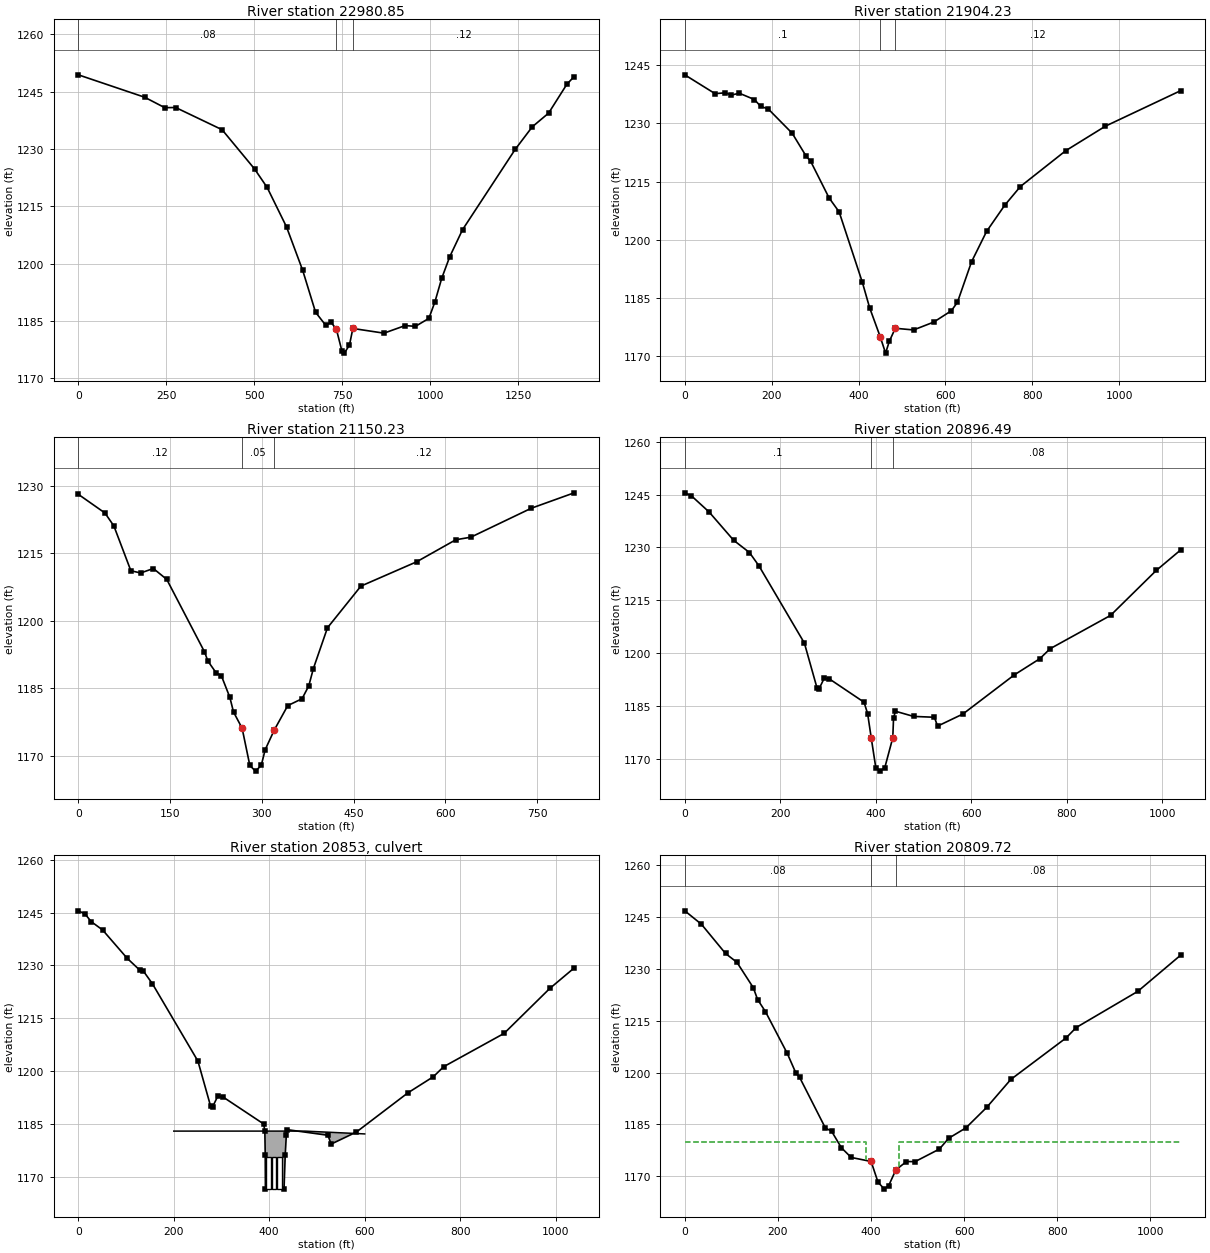
Type RM Length L Ch R = 1 ,22980.85,1090.69,1076.62,1045.39
XS GIS Cut Line= 4
  1353591.816954   821468.170769  1353153.301903   821196.983837
   1352923.45652   821266.830562  1352316.661305   821508.560319
#Sta/Elev= 30
       0 1249.41  188.46 1243.55  245.56 1240.82   276.6 1240.86  408.57 1235.05
  500.69  1224.8  536.57 1219.95  591.55 1209.65  637.63 1198.25   674.2  1187.3
  702.86 1183.92   718.2 1184.66  733.18 1182.91  748.71 1177.28  755.82 1176.62
  770.44 1178.71  780.11 1183.07  868.55 1181.84   928.8 1183.83  957.84 1183.62
  996.17 1185.71 1013.19 1189.99 1032.55 1196.17 1055.44 1201.84 1091.71 1208.89
 1241.28 1229.89 1289.95 1235.81 1336.32 1239.39 1388.11 1246.92 1408.99 1248.97
#Mann= 3 , 0 , 0
       0     .08       0  733.18     .05       0  780.11     .12       0
Bank Sta=733.18,780.11
Exp/Cntr=0.3,0.1

Type RM Length L Ch R = 1 ,21904.23,770.72,754,735.48
XS GIS Cut Line= 3
  1352991.743699   819921.828142  1352697.477011   820452.662173
   1352258.96196    820758.46874
#Sta/Elev= 30
       0 1242.52   69.56 1237.67   93.58 1237.88  107.33  1237.3  125.35 1237.78
  160.37 1236.14  174.69 1234.38  192.24  1233.7  247.31 1227.44  279.63 1221.49
  289.65 1220.24  332.24 1210.76  355.34 1207.16   408.9 1188.95  425.55 1182.44
  449.71 1175.01  462.27 1170.73  470.82 1173.76   484.6 1177.14  526.64 1176.71
  573.01 1178.73  613.62 1181.65  627.66 1183.84  660.21  1194.3  694.84 1202.13
   736.6 1208.88  772.68 1213.71  877.08 1222.95   968.5 1229.28 1141.56 1238.43
#Mann= 3 , 0 , 0
       0      .1       0  449.71     .05       0   484.6     .12       0
Bank Sta=449.71,484.6
Exp/Cntr=0.3,0.1

Type RM Length L Ch R = 1 ,21150.23,247.79,253.74,256.37
XS GIS Cut Line= 2
  1352091.633841    819702.57064  1352155.103102   820510.361565
#Sta/Elev= 30
       0 1228.09   43.48 1223.94   58.08 1221.06   85.86  1211.1  101.84 1210.61
  122.59  1211.6   144.5 1209.18  206.18 1193.08  211.72 1191.03  225.48 1188.36
  233.59 1187.82  247.58 1182.98  253.58 1179.72  267.66  1176.1  280.26 1167.83
  289.53 1166.57   298.9 1167.84  305.36 1171.33  320.15 1175.69  342.23 1181.13
  365.61 1182.66  376.61 1185.52  384.06 1189.35  407.15 1198.43   461.8 1207.69
   552.7 1213.08  616.86 1217.99  641.42 1218.56  740.13 1224.99  810.28 1228.42
#Mann= 3 , 0 , 0
       0     .12       0  267.66     .05       0  320.15     .12       0
Bank Sta=267.66,320.15
Exp/Cntr=0.5,0.3

Type RM Length L Ch R = 1 ,20896.49,86.72,86.77,86.76
XS GIS Cut Line= 3
  1351935.845599    819587.17195  1351873.723497   819922.077271
  1351849.296582   820619.990293
#Sta/Elev= 30
       0 1245.48   14.03 1244.61   50.89 1240.05  102.26 1232.03  135.45 1228.55
   155.3 1224.78  250.61 1202.85  277.16 1190.08  281.58 1189.94  291.86 1192.82
  302.79 1192.71  375.56 1186.09  383.08 1182.87  390.79 1175.84   400.2 1167.54
  409.62 1166.54  419.11 1167.54  435.82    1176  437.42 1181.65  441.41 1183.53
  479.36 1182.06  522.98 1181.82  529.73 1179.31  582.75 1182.74  690.58 1193.85
  743.85 1198.42  765.61 1201.27  892.12 1210.71   987.8 1223.45 1038.96 1229.27
#Mann= 3 , 0 , 0
       0      .1       0  390.79     .05       0  435.82     .08       0
#XS Ineff= 2 , 0
       0     375    1183     450       0  1182.2
Permanent Ineff=
       F       F
Bank Sta=390.79,435.82
Exp/Cntr=0.5,0.3

Type RM Length L Ch R = 2 ,20853   ,,,
BEGIN DESCRIPTION:
Gaston Deal Road, SR 1344; 37003-0003
END DESCRIPTION:
Bridge Culvert--1,0,-1,-1, 0
Deck Dist Width WeirC Skew NumUp NumDn MinLoCord MaxHiCord MaxSubmerge Is_Ogee
25,30,2.6,0, 3, 3, , , 0.95, 0, 0,0,,
     200     475     600
    1183    1183  1182.2
                        
     200     475     600
    1183    1183  1182.2
                        
BR Coef=-1 , 1 , 0 ,, 0 ,,,0.8,0,1.2,0,
WSPro=,,,, 1 ,,,, 0 ,,,, 0 ,,,,-1 ,-1 ,-1 , 0 , 0 , 0 , 0 , 0
Multiple Barrel Culv=2,9,10,60,0.013,0.4,1,8,1,1166.54,1166.28, 3,Culvert #1  , 0 ,15
     399     418     410     429     421     440
Culvert Bottom n=0.013
BR U #Sta/Elev= 30
       0 1245.48   14.03 1244.61   26.67 1242.45   50.89 1240.05  102.26 1232.03
  128.73 1228.66  135.45 1228.55   155.3 1224.78  250.61 1202.85  277.16 1190.08
  281.58 1189.94  291.86 1192.82  302.79 1192.71  388.47 1185.01  390.79    1183
  391.61 1176.32     392 1166.54     431 1166.54  433.57 1176.36  435.82  1181.8
  436.95 1183.42  522.98 1181.82  529.73 1179.31  582.75 1182.74  690.58 1193.85
  743.85 1198.42  765.61 1201.27  892.12 1210.71   987.8 1223.45 1038.96 1229.27
BR U #Mann= 3
       0      .1  391.61    .045  433.57      .1
BR U Banks=391.61,433.57
BR D #Sta/Elev= 196
       0 1246.83    4.96 1246.41    7.97 1246.07    9.29 1246.03   11.96  1245.8
   17.69 1244.94   19.73 1244.63   21.57 1244.49   29.52 1243.51   35.75 1242.94
   40.69 1242.17   42.41 1241.96   43.34 1241.77   57.52 1239.37   58.33 1239.33
   62.79 1238.52   64.59 1238.16   71.58 1237.19   87.19 1234.53    87.4  1234.5
   87.52 1234.48   99.73 1232.78  104.85 1232.75   111.2 1232.03  111.49 1232.01
  111.71 1231.99     112 1231.93  122.84 1229.32  131.15 1227.59  132.48 1227.41
  136.09 1226.59  137.68 1226.31  138.27 1226.22  147.08  1224.6  155.77 1221.45
  156.41 1221.15  157.95 1220.84  173.33 1217.64  178.31 1215.95  186.42 1213.91
  190.61 1213.03  193.25 1212.25  202.58 1209.72  213.77 1206.87  215.33 1206.59
  220.05 1205.58  227.53 1203.54  236.24 1200.66  238.52 1199.92  244.89 1199.02
  246.71 1198.62  260.51 1194.68  270.49 1191.94   272.6 1191.38  275.15 1190.73
  284.31 1188.38  295.69 1185.74  302.05 1183.96  303.17 1183.77  303.64 1183.71
  315.25 1183.06  322.58 1181.02  330.54 1179.57  333.55 1178.85  336.31 1178.27
  346.15 1176.78  353.53 1176.14  357.41 1175.45  361.13 1175.19  375.64 1174.94
  378.09 1174.88  379.26 1174.88  385.13 1174.94     394 1174.79   400.2 1174.29
  404.24 1172.23     414 1166.28   419.4 1166.28  421.69 1166.28  428.62 1166.28
  435.64 1166.28  437.97 1166.28  440.72 1166.28     449 1166.28  453.39 1171.85
   464.3 1172.97  468.58 1173.55  470.65 1173.68  476.27 1174.27  483.96 1174.57
  491.73 1174.55   494.6 1174.23  497.44 1174.41   503.1 1174.83  513.28  1175.4
  514.48 1175.43  520.91 1175.68  528.82 1176.18  534.66 1176.65   538.1 1177.04
  542.16 1177.45  546.89 1177.87  560.12 1179.85  562.51 1180.25  566.96 1181.01
  577.93 1181.81  579.78 1182.04  583.45 1182.12   591.7 1182.92  599.45 1183.73
  603.91 1184.01  606.08 1184.59  609.51 1184.94  619.97 1186.51  623.55 1186.89
  625.19 1187.11  628.56 1187.42  639.57 1188.89  640.89 1189.09  647.54 1189.81
  648.64 1189.95  651.47 1190.39  660.68 1191.73  666.29 1192.91  667.37 1193.13
  668.66 1193.29   680.7 1195.34  684.84 1195.82  687.71 1196.21  698.82 1197.85
  700.39 1198.03  705.84  1198.6  706.29 1198.65  706.56 1198.69  708.64 1198.88
  724.63 1200.38  724.75 1200.39  724.82  1200.4  725.16 1200.43  739.13 1201.87
   744.9 1202.57  748.69 1202.91  758.42 1203.75  758.73 1203.77  760.24 1203.93
  765.17 1204.44  766.22 1204.55  775.57 1205.51  780.78 1206.21  783.54 1206.49
  785.11 1206.68  792.37 1207.28  799.29 1208.06   802.5 1208.36     806 1208.68
  818.63 1209.99  819.15 1210.05  819.49 1210.09  827.18 1211.06  835.86 1212.29
  840.87 1213.05   844.2 1213.23   854.1 1213.75  861.83 1214.55  865.66 1214.89
  871.05  1215.2  876.79 1215.83  881.45 1215.72  894.83 1216.86  900.79 1217.56
  907.19 1218.13  913.43 1218.56  922.48 1219.72  924.55 1220.04   929.7 1220.36
  931.93 1220.62  938.78 1221.06  942.23  1221.3  944.01 1221.38  951.83 1221.63
  951.92 1221.64  952.35 1221.67  967.02 1222.99  973.16 1223.52  973.85 1223.62
  987.47 1225.41  988.65 1225.51  995.61 1226.32 1005.23 1226.92 1011.82 1227.43
 1015.62 1227.83 1020.25  1228.5 1033.88 1230.02 1036.18 1230.33 1050.95 1232.67
 1065.17 1233.99
BR D #Mann= 3
       0      .1   400.2    .045  453.39      .1
BR D Banks=400.2,
BC Design=,, 0 ,, 0 ,,,,,,

Type RM Length L Ch R = 1 ,20809.72,306.33,308.96,308.99
XS GIS Cut Line= 3
  1351889.686086   819575.632071  1351787.174479   819927.847187
  1351762.747517   820625.760255
#Sta/Elev= 30
       0 1246.83   35.75 1242.94   87.52 1234.48     112 1231.93  147.08  1224.6
  156.41 1221.15  173.33 1217.64  220.05 1205.58  238.52 1199.92  246.71 1198.62
  302.05 1183.96  315.25 1183.06  336.31 1178.27  357.41 1175.45   400.2 1174.29
  415.08  1168.3  428.62 1166.28  437.97 1167.28  453.39 1171.85  476.27 1174.27
   494.6 1174.23  546.89 1177.87  566.96 1181.01  603.91 1184.01  648.64 1189.95
  700.39 1198.03  818.63 1209.99  840.87 1213.05  973.16 1223.52 1065.17 1233.99
#Mann= 3 , 0 , 0
       0     .08       0   400.2     .05       0  453.39     .08       0
#XS Ineff= 2 , 0
       0     390    1180     460       0    1180
Permanent Ineff=
       F       F
Bank Sta=400.2,453.39
Exp/Cntr=0.5,0.3

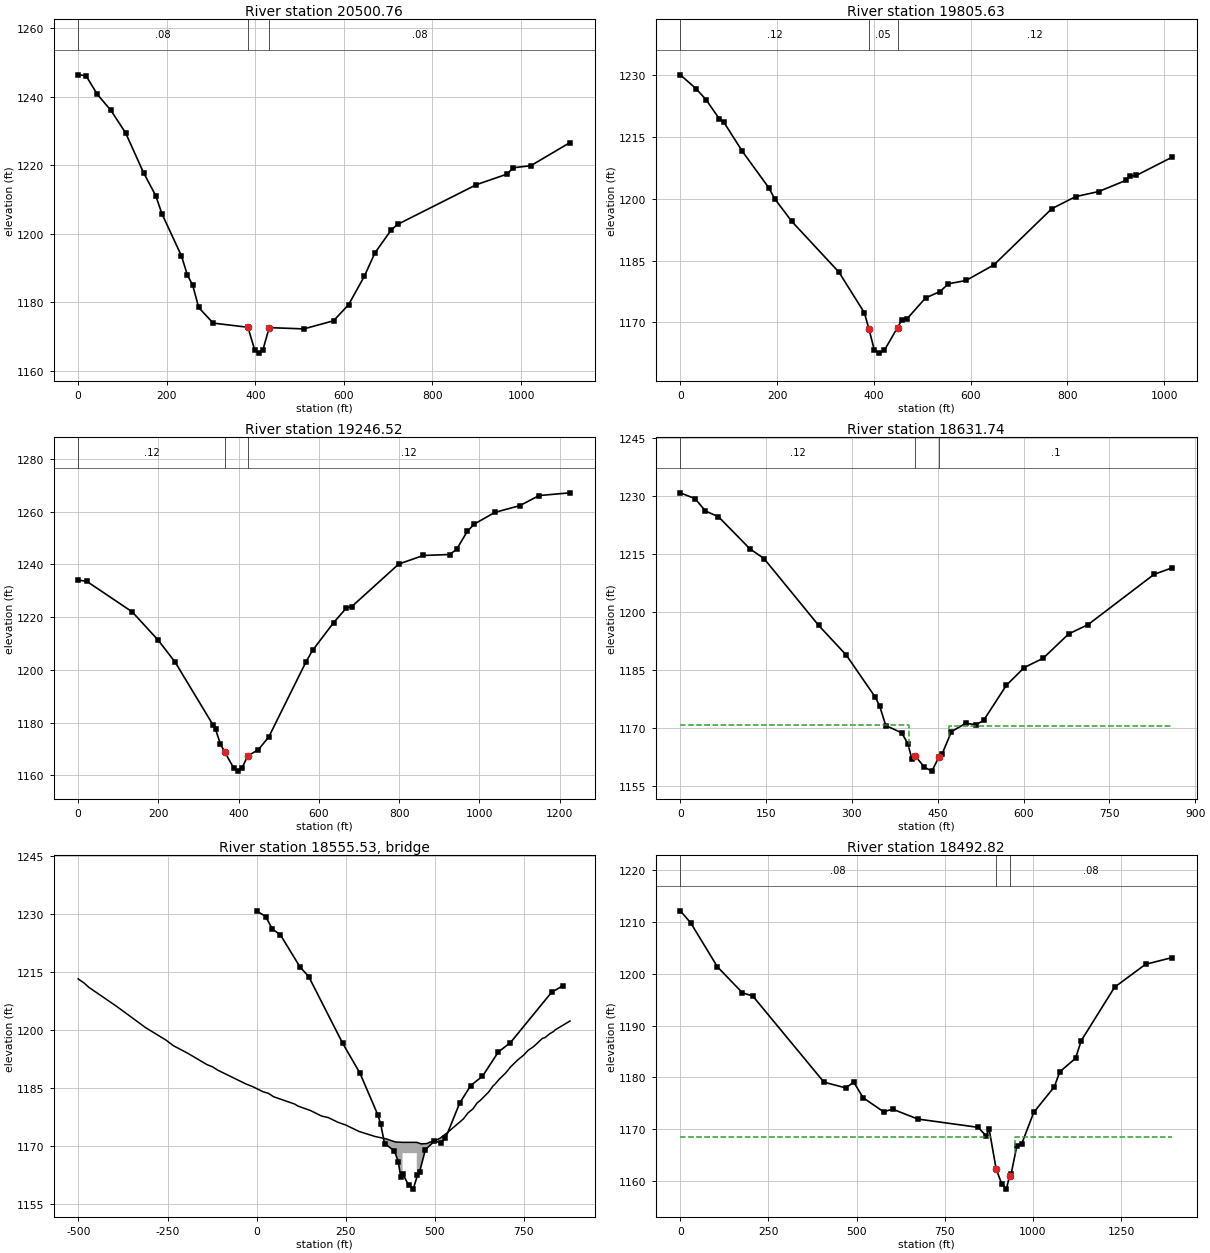
Type RM Length L Ch R = 1 ,20500.76,701.92,695.12,679.21
XS GIS Cut Line= 4
  1351751.207686   819517.932726  1351555.029894   819742.960191
  1351520.410259   820169.935363  1351624.269071   820539.211237
#Sta/Elev= 30
       0 1246.46   17.62 1246.24   43.21 1240.76   74.04 1236.07  107.25 1229.47
  147.59  1217.9  175.23 1211.14   189.2 1205.86  233.29 1193.55   246.7 1187.94
  258.73    1185  272.11 1178.49  304.84 1173.93  383.27 1172.72  398.49 1166.16
  407.83 1165.16  417.27 1166.16  431.34 1172.61  509.49 1172.24  576.62 1174.61
  610.67 1179.33  646.04 1187.58  669.86 1194.41  706.87 1201.15  721.28 1202.77
  899.31 1214.38  968.78 1217.48  981.95 1219.31 1021.94 1219.91 1110.51 1226.68
#Mann= 3 , 0 , 0
       0     .08       0  383.27     .05       0  431.34     .08       0
Bank Sta=383.27,431.34
Exp/Cntr=0.3,0.1

Type RM Length L Ch R = 1 ,19805.63,527.84,559.12,587.99
XS GIS Cut Line= 3
  1350776.088641    819442.92354  1351001.116106   820031.456916
  1351012.655984   820418.042585
#Sta/Elev= 30
       0 1230.16   32.55  1226.8   53.08 1224.15   80.83 1219.45   89.66 1218.73
  128.36 1211.56  182.85 1202.75  195.21 1200.05  230.58 1194.54  327.75 1182.26
  380.41 1172.39   389.9 1168.47  401.14 1163.28  411.43 1162.55  421.72 1163.19
   449.1 1168.76  457.57 1170.52  469.19 1170.94  507.04 1175.96  537.08 1177.51
  553.95 1179.38  590.76  1180.2  648.34 1183.99  767.82 1197.62  817.35 1200.58
  864.85  1201.8  921.06 1204.51  929.12 1205.56  942.89 1205.73 1016.84 1210.16
#Mann= 3 , 0 , 0
       0     .12       0   389.9     .05       0   449.1     .12       0
Bank Sta=389.9,449.1
Exp/Cntr=0.3,0.1

Type RM Length L Ch R = 1 ,19246.52,599.09,614.78,627.39
XS GIS Cut Line= 2
  1350718.389296   819390.994111  1349968.297716    820360.34324
#Sta/Elev= 30
       0 1234.04   21.23 1233.59  134.78 1221.98  199.42 1211.27  241.76 1202.91
  335.66 1179.22  342.47 1177.42  354.37 1171.92   365.8 1168.72  388.24 1162.59
  397.84 1161.59  407.68 1162.59  422.82 1167.39  448.88 1169.68  475.13 1174.58
  568.05 1203.12  583.98 1207.36  636.86 1217.95  668.41 1223.47  681.83 1223.99
  798.86 1240.12   860.2 1243.38  925.87 1243.74  943.23 1245.73  969.81 1252.55
  987.27 1255.29 1038.15  1259.7 1100.64 1262.28 1148.72  1266.1 1225.67 1267.13
#Mann= 3 , 0 , 0
       0     .12       0   365.8     .05       0  422.82     .12       0
Bank Sta=365.8,422.82
Exp/Cntr=0.5,0.3

Type RM Length L Ch R = 1 ,18631.74,133.55,138.92,146.1
BEGIN DESCRIPTION:
Upstream xs of Bridge 37003-0005
END DESCRIPTION:
XS GIS Cut Line= 3
  1350677.999745   819315.984972  1350401.042851   819177.506525
  1349864.438904   819298.675177
#Sta/Elev= 30
       0  1230.8    25.8  1229.3      44  1226.1    66.8  1224.6   121.8  1216.3
   146.3  1213.8   241.9  1196.5   290.3  1188.8     341  1177.9   348.6  1175.6
   359.2  1170.6     387  1168.7   397.8  1165.9   404.9  1161.9   410.8  1162.7
   426.8  1159.8   439.8  1158.8   451.8  1162.4   457.8  1163.3     474    1169
     499  1171.2   516.7  1170.8   530.1  1171.9     570    1181   601.2  1185.6
   634.3    1188   678.9  1194.3   712.8  1196.7   828.1  1209.7   859.8  1211.4
#Mann= 3 , 0 , 0
       0     .12       0   410.8     .05       0   451.8      .1       0
#XS Ineff= 2 , 0
       0     400  1170.8     470       0  1170.5
Permanent Ineff=
       F       F
Bank Sta=410.8,451.8
Exp/Cntr=0.5,0.3

Type RM Length L Ch R = 3 ,18555.53,,,
BEGIN DESCRIPTION:
St. Claire Rd, SR 1338;  Bridge : 37003-0005
END DESCRIPTION:
Bridge Culvert--1,0,-1,-1, 0
Deck Dist Width WeirC Skew NumUp NumDn MinLoCord MaxHiCord MaxSubmerge Is_Ogee
66.2,20,2.6,0, 60, 60, , , 0.95, 0, 0,0,,
    -501    -484  -470.8  -393.2  -311.9  -255.1  -233.4  -192.3    -139  -122.9
  -109.5   -29.7   -10.4    17.9    32.9    47.8   107.2   115.9   152.2   182.6
   201.5   228.3     250   288.3   333.3   364.1   389.5   409.8   409.8   449.8
   449.8   462.4   478.6   487.1   492.5   495.4   504.2   515.7   535.6   581.1
   593.4   607.9   619.2   628.7   652.4   664.7     668     681   699.9     713
     733   750.3   762.3   778.2   802.5   809.8   823.1   834.3   838.3   880.1
  1213.2  1212.1    1211  1206.1  1200.6  1197.4  1195.9  1193.9    1191  1190.4
  1189.6    1186  1185.3    1184  1183.6  1182.7  1180.8  1180.3  1179.1  1177.7
  1177.3  1176.1  1175.4  1173.7  1172.4  1171.8    1171  1170.9  1170.9  1170.9
  1170.9  1170.5  1170.6    1171    1171  1171.4  1171.5    1172  1173.4    1177
  1178.5  1179.6  1181.1  1181.8    1184  1185.6  1185.8  1187.2  1188.9  1190.4
  1192.2  1193.5  1194.7  1195.7  1197.8    1198    1199  1199.6    1200  1202.3
                                                                                
                                                                                
                                                                  1168.1  1168.1
                                                                                
                                                                                
                                                                                
   -16.1      .9    14.1    91.7     173   229.8   251.5   292.6   347.9     362
   375.4   455.1   474.5   502.8   517.8   532.7   592.1   600.8   637.1   667.5
   686.4   713.2   734.9   773.1   818.2     849   874.3   894.7   894.7   934.7
   934.7   947.3   963.4     972   977.3   980.3   989.1  1000.6  1020.5  1065.9
  1078.3  1092.7  1104.1  1113.5  1137.3  1149.5  1152.9  1165.9  1184.7  1197.9
  1217.9  1235.1  1247.2  1263.1  1287.4  1294.7  1307.9  1319.2  1323.1    1365
  1213.2  1212.1    1211  1206.1  1200.6  1197.4  1195.9  1193.9  1190.9  1190.4
  1189.6    1186  1185.3    1184  1183.6  1182.7  1180.8  1180.3  1179.1  1177.7
  1177.3  1176.1  1175.4  1173.7  1172.4  1171.8    1171  1170.6  1170.6  1170.6
  1170.6  1170.5  1170.6    1171    1171  1171.4  1171.5    1172  1173.4    1177
  1178.5  1179.6  1181.1  1181.8    1184  1185.6  1185.8  1187.2  1188.9  1190.4
  1192.2  1193.5  1194.7  1195.7  1197.8    1198    1199  1199.6    1200  1202.3
                                                                                
                                                                                
                                                                  1167.8  1167.8
                                                                                
                                                                                
                                                                                
BR Coef=-1 , 1 , 0 ,, 0 ,,,0.8,0,1.2,0,
WSPro=,,,, 1 ,,,, 0 ,,,, 0 ,,,,-1 ,-1 ,-1 , 0 , 0 , 0 , 0 , 0
BC Design=,, 0 ,, 0 ,,,,,,

Type RM Length L Ch R = 1 ,18492.82,1011.45,1005.22,985.77
BEGIN DESCRIPTION:
Down stream xs of Bridge 37003-0005
END DESCRIPTION:
XS GIS Cut Line= 3
  1351122.358659   818636.017372  1350389.502973   819056.337918
  1349852.899026   819177.506525
#Sta/Elev= 30
       0  1212.1    29.4  1209.8   105.5  1201.3   176.4  1196.3   205.5  1195.7
   407.5  1179.1   469.3    1178   492.1  1179.1   518.5  1176.1   576.5  1173.4
   602.4  1173.9   673.4    1172   844.8  1170.4   866.8  1168.8   876.1    1170
   895.7  1162.4   911.7  1159.5   924.7  1158.5   933.7    1161   938.3  1161.4
   954.4  1166.8   968.2  1167.2  1002.6  1173.3  1060.8  1178.2  1076.3  1181.1
    1121  1183.7  1137.2  1187.1  1231.8  1197.4  1319.5  1201.8    1395  1203.1
#Mann= 3 , 0 , 0
       0     .08       0   895.7     .05       0   933.7     .08       0
#XS Ineff= 2 , 0
       0     880  1168.5     950       0  1168.5
Permanent Ineff=
       F       F
Bank Sta=895.7,933.7
Exp/Cntr=0.5,0.3

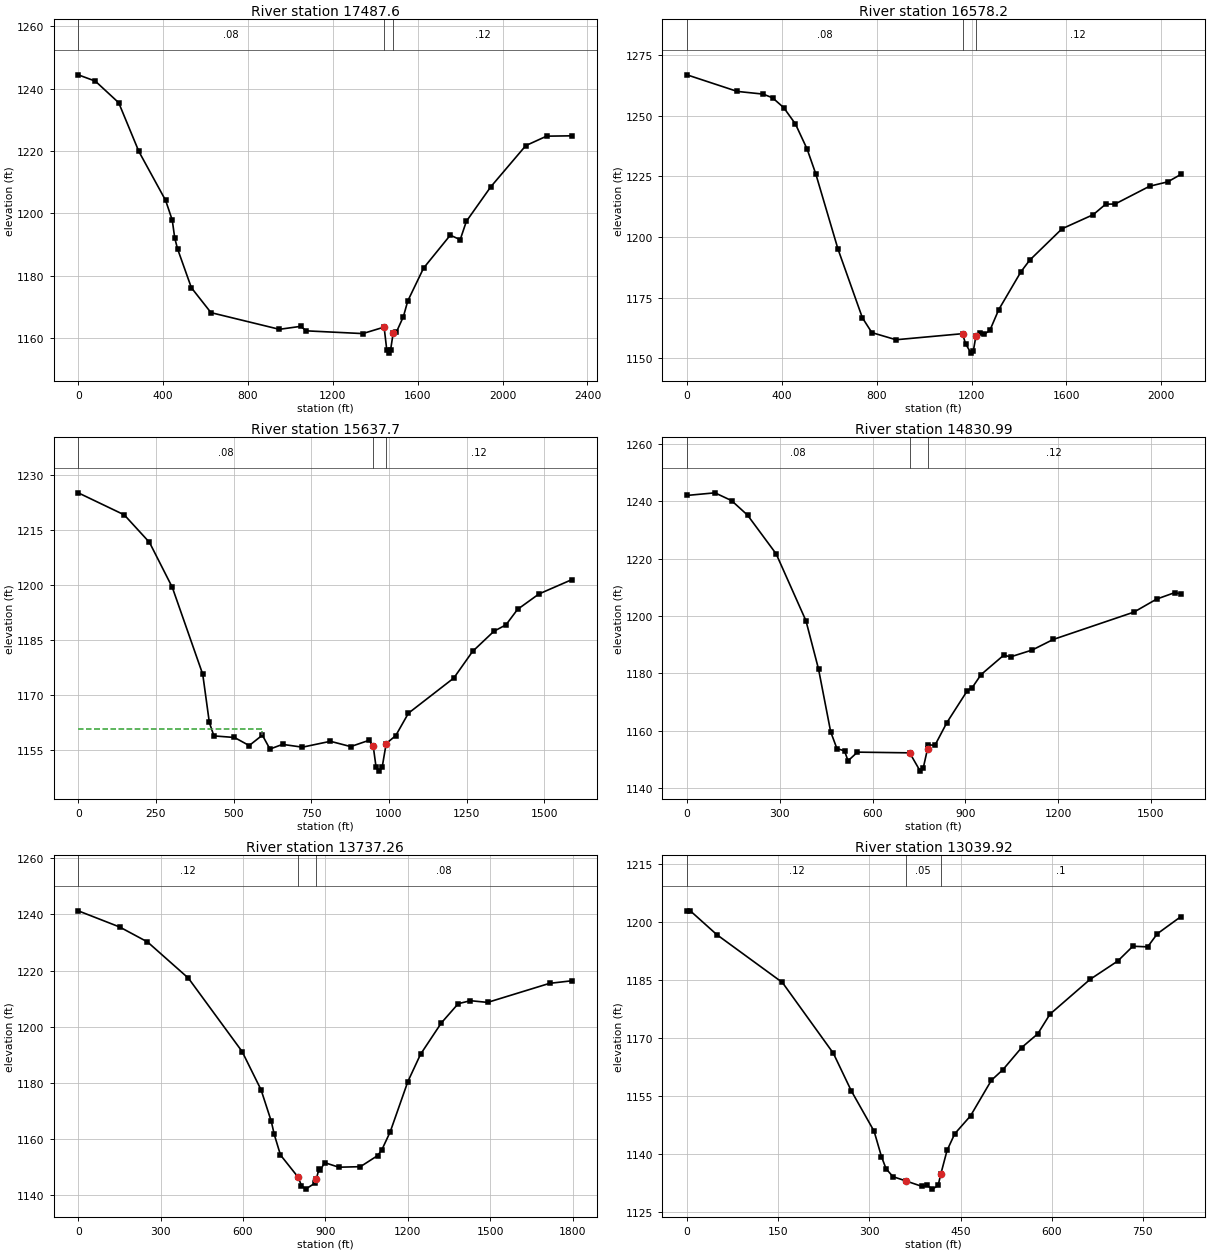
Type RM Length L Ch R = 1 ,17487.6 ,907.71,909.41,901.41
XS GIS Cut Line= 3
  1351041.505657   817492.685498  1349702.880701   818392.795356
  1349189.356464   818889.009799
#Sta/Elev= 30
       0 1244.47   80.51 1242.45  190.71 1235.52  285.77 1219.87  411.87 1204.17
  443.11 1197.85  454.77 1192.11  468.01 1188.65   533.2 1176.16   625.6 1168.16
  948.05 1162.81 1048.31 1163.76 1074.97 1162.32 1341.01 1161.44 1441.58 1163.52
 1454.18 1156.16 1463.16 1155.17 1471.98 1156.16 1484.38 1161.61  1499.3  1161.9
 1532.61 1166.91 1552.97  1171.9 1627.62 1182.46 1753.44 1193.02 1800.19 1191.57
 1829.34 1197.48 1944.43 1208.55 2109.21 1221.75 2207.26 1224.79 2327.21  1224.9
#Mann= 3 , 0 , 0
       0     .08       0 1441.58     .05       0 1484.38     .12       0
Bank Sta=1441.58,1484.38
Exp/Cntr=0.3,0.1

Type RM Length L Ch R = 1 ,16578.2 ,940.9,940.49,922.25
XS GIS Cut Line= 4
  1350401.325834   816838.588782  1350083.696406   816933.001794
   1349212.43622   817781.182223  1348906.629654   818219.697321
#Sta/Elev= 30
       0  1266.9  212.18 1260.06  321.21 1258.95  360.96 1257.42  408.19 1253.36
  457.44 1246.63  506.58 1236.31  542.84 1226.17  636.91 1195.01  739.64  1166.7
   779.6 1160.57  881.51 1157.62 1161.89 1160.12 1174.85 1155.95 1197.78  1152.1
 1207.68 1153.11 1218.24 1159.01 1233.81 1160.59 1253.18 1159.89 1277.02 1161.44
 1314.82 1170.08 1408.63 1185.72 1445.41 1190.47  1581.3 1203.39 1712.94 1209.21
 1765.44 1213.54 1805.18 1213.61 1950.49 1220.94 2027.49 1222.76 2081.92 1225.79
#Mann= 3 , 0 , 0
       0     .08       0 1161.89     .05       0 1218.24     .12       0
Bank Sta=1161.89,1218.24
Exp/Cntr=0.3,0.1

Type RM Length L Ch R = 1 ,15637.7 ,812.29,806.71,798.5
XS GIS Cut Line= 4
  1349503.556901   816282.615933  1349232.650763   816418.069025
  1348763.080062   817090.819341  1348835.321684   817551.359844
#Sta/Elev= 30
       0 1225.03  148.17 1219.03  229.29 1211.54  302.88 1199.28   400.8 1175.62
  422.02 1162.52  436.67 1158.86  502.94 1158.43  550.27 1156.23  592.68 1159.06
  617.13 1155.28  657.53 1156.55  721.68 1155.79   811.7 1157.39  877.09 1155.95
  936.45 1157.67  949.45  1156.1  958.85 1150.27  968.79 1149.27  978.19 1150.27
  991.29 1156.78 1021.97 1158.93 1062.82 1165.04 1208.86 1174.61 1269.54 1181.87
 1337.96 1187.34 1376.79 1189.09 1414.11  1193.3    1483  1197.5 1589.47 1201.42
#Mann= 3 , 0 , 0
       0     .08       0  949.45     .05       0  991.29     .12       0
#XS Ineff= 2 , 0
          592.33 1160.81
Permanent Ineff=
       F       F
Bank Sta=949.45,991.29
Exp/Cntr=0.3,0.1

Type RM Length L Ch R = 1 ,14830.99,1069.86,1093.73,1108.96
XS GIS Cut Line= 3
  1348491.194313   815784.784668  1348110.378607   816806.063179
   1347741.10278   817152.259296
#Sta/Elev= 30
       0    1242   90.57 1242.91  144.23  1240.2  195.82 1235.15  288.54 1221.62
   384.8 1198.31  425.41 1181.48  464.62 1159.64  484.72  1153.8  509.35 1152.97
  520.79 1149.51  551.16 1152.54  720.02 1152.29  754.05 1145.92  763.74 1146.92
  777.68 1153.66  779.93 1155.14  801.45 1154.87  840.35 1162.85  906.67 1174.01
  921.76 1174.96  950.76 1179.56 1024.19 1186.34 1046.08 1185.74 1115.87 1188.12
 1184.09 1191.81 1444.88 1201.34  1518.1 1205.87 1577.37 1208.15 1596.15 1207.65
#Mann= 3 , 0 , 0
       0     .08       0  720.02     .05       0  777.68     .12       0
Bank Sta=720.02,777.68
Exp/Cntr=0.3,0.1

Type RM Length L Ch R = 1 ,13737.26,685.82,697.34,706.43
XS GIS Cut Line= 4
  1348283.476643   815755.934995  1347766.877412    815627.93402
  1347443.532691   815813.037456  1346697.013664   816302.600811
#Sta/Elev= 30
       0 1241.26  150.49 1235.52  252.08 1230.19  400.97  1217.3   596.5 1191.19
  665.56 1177.55  702.64 1166.38  713.56 1161.67   736.2 1154.36  800.77 1146.42
  812.47  1143.5  827.89 1142.21  863.57 1144.46  866.39 1145.71   876.6 1149.49
  881.48 1148.94   896.7 1151.65  948.65 1150.01  1027.1  1150.2 1090.01 1154.15
  1104.9 1156.14 1135.75 1162.62 1199.97 1180.51 1246.05  1190.2 1321.78 1201.36
  1383.2 1208.21 1427.77 1209.27 1490.13 1208.67 1715.83 1215.45 1797.53 1216.37
#Mann= 3 , 0 , 0
       0     .12       0  800.77     .05       0  866.39     .08       0
Bank Sta=800.77,866.39
Exp/Cntr=0.3,0.1

Type RM Length L Ch R = 1 ,13039.92,644.45,650.05,650.63
XS GIS Cut Line= 2
   1347809.56868   815062.509691   1347014.86889    815230.01993
#Sta/Elev= 30
       0 1202.86    5.51 1202.94   49.21 1196.77  157.03  1184.4  240.84 1166.09
  270.42 1156.35  307.84 1145.93  319.98 1139.35  327.51 1136.23  338.77 1134.18
  360.03 1133.08  387.06 1131.63  394.41 1131.97  403.86 1130.95  413.12 1131.89
   417.4 1134.74   427.8 1140.95  440.53 1145.28  466.42  1149.9  500.82 1159.12
  519.79 1161.86   550.6 1167.58  577.05 1171.13  597.12 1176.21  663.06 1185.21
  708.74 1189.97  733.44 1193.78  757.77 1193.62  773.56    1197  812.16 1201.41
#Mann= 3 , 0 , 0
       0     .12       0  360.03     .05       0   417.4      .1       0
Bank Sta=360.03,417.4
Exp/Cntr=0.3,0.1

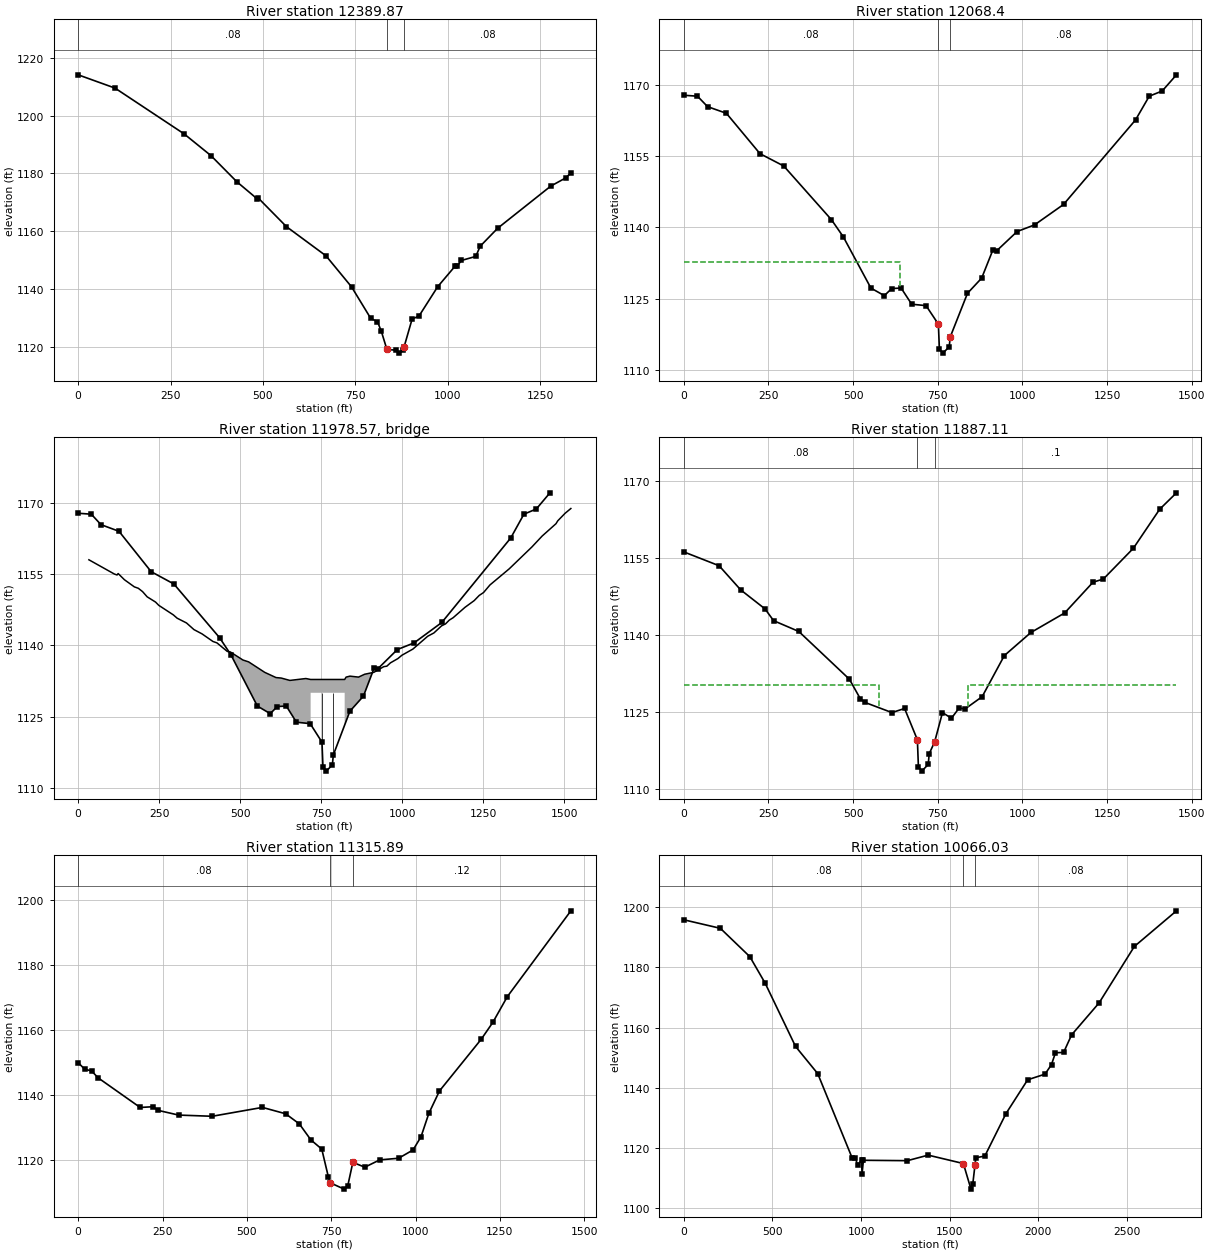
Type RM Length L Ch R = 1 ,12389.87,344.29,321.47,293.46
XS GIS Cut Line= 4
    1348046.9093   814907.754566  1347498.765474   814509.629019
  1347152.056245   814544.987053  1346962.161527   814786.585913
#Sta/Elev= 30
       0  1214.1   99.63 1209.52  286.63 1193.69  359.36 1186.17  429.44 1177.13
  484.52 1171.22  487.96 1171.43  563.47 1161.64  670.64 1151.54  739.85  1140.8
  791.89 1129.88  809.87 1128.81   820.4 1125.44  835.36 1119.21  859.33 1118.92
  869.39 1117.91  879.63 1118.99  882.03  1120.1  903.64 1129.68  922.31 1130.73
  972.85 1140.86 1019.58 1147.92 1025.98 1148.09 1037.13 1149.94 1075.99 1151.34
  1087.8 1154.85 1135.08 1161.06 1278.97 1175.65 1318.93 1178.44 1333.27  1180.2
#Mann= 3 , 0 , 0
       0     .08       0  835.36     .05       0  882.03     .08       0
Bank Sta=835.36,882.03
Exp/Cntr=0.5,0.3

Type RM Length L Ch R = 1 ,12068.4 ,173.94,181.29,176.19
BEGIN DESCRIPTION:
Upstream xs of Bridge 37003-0008
END DESCRIPTION:
XS GIS Cut Line= 3
  1347914.200815   813759.537439  1347094.870012   814376.920535
  1346812.143202   814700.036895
#Sta/Elev= 30
       0  1167.8    40.5  1167.6    70.3  1165.4   125.9    1164   225.1  1155.5
   295.3  1152.9   436.1  1141.6   471.1    1138   552.7  1127.2   592.4  1125.6
   614.1  1127.1     642  1127.2   673.2  1123.8   715.6  1123.5     752  1119.6
     755  1114.4     765  1113.5     784  1114.8     787  1116.9     838  1126.1
   879.9  1129.3   913.4  1135.3     925  1135.1   984.5  1139.1    1036  1140.5
  1121.6  1144.8  1334.3  1162.6  1374.8  1167.6  1413.1  1168.7  1455.2  1172.1
#Mann= 3 , 0 , 0
       0     .08       0     752     .05       0     787     .08       0
#XS Ineff= 2 , 0
       0   639.7  1132.7   899.3       0  1132.7
Permanent Ineff=
       F       F
Bank Sta=752,787
Exp/Cntr=0.5,0.3

Type RM Length L Ch R = 3 ,11978.57,,,
BEGIN DESCRIPTION:
Little River Church Rd, SR 1331;  Bridge : 37003-0008
END DESCRIPTION:
Bridge Culvert--1,0,-1,-1, 0
Deck Dist Width WeirC Skew NumUp NumDn MinLoCord MaxHiCord MaxSubmerge Is_Ogee
77.3,25,2.6,0, 60, 60, , , 0.95, 0, 0,0,,
    33.1   111.7   119.9   123.3   142.7   173.2   185.5   198.6   212.8   238.6
   248.8   293.5   305.3   334.1   357.1     382   415.7   428.1     460   469.2
   508.1   525.9   575.4   610.2   626.3     653   702.3     717     717     822
     822   826.4   838.4   864.7   883.5   911.9   942.6   952.1   963.2   986.2
   998.5  1032.4  1078.1  1097.3    1121    1133  1144.7  1156.5  1193.3  1221.4
  1237.1  1250.3  1270.1  1329.6  1399.5  1431.1  1473.8  1479.2    1502  1519.7
    1158    1155  1154.8  1155.1  1153.8  1152.3    1152  1151.3  1150.2  1149.1
  1148.4  1146.4  1145.7  1144.7  1143.3  1142.4  1140.8  1140.5  1138.7  1138.6
  1136.9  1136.5  1134.3  1133.2  1133.1  1132.6    1133  1132.8  1132.8  1132.8
  1132.8  1133.3  1133.5  1133.3  1133.9  1134.3  1135.5  1135.6  1136.3  1137.2
  1137.9  1139.2  1141.9  1142.6  1144.1  1144.5  1145.3  1145.8    1148  1149.4
  1150.5  1151.1  1152.7  1156.1  1160.7    1163  1165.6  1166.2  1167.8  1168.8
                                                                                
                                                                                
                                                                    1130    1130
                                                                                
                                                                                
                                                                                
     -30    48.6    56.8    60.1    79.6     110   128.2   149.7   175.5   185.7
   230.4   242.2     271     294   318.9   352.6     365   396.8   406.1     445
   462.8   512.2   547.1   563.2   589.9   639.2     655     655     760     760
   763.3   775.3   801.6   820.3   848.8   879.5     889   900.1     923   935.4
   969.3    1015  1034.2  1057.9  1069.9  1081.6  1093.4  1130.2  1158.3    1174
  1187.2  1206.9  1266.5  1322.5  1336.4    1368  1410.7    1416  1438.9  1456.6
    1158    1155  1154.8  1155.1  1153.8  1152.3  1151.7  1150.2  1149.1  1148.4
  1146.4  1145.7  1144.7  1143.3  1142.4  1140.8  1140.5  1138.7  1138.6  1136.9
  1136.5  1134.3  1133.2  1133.1  1132.6    1133  1132.7  1132.7  1132.7  1132.7
  1133.3  1133.5  1133.3  1133.9  1134.3  1135.5  1135.6  1136.3  1137.2  1137.9
  1139.2  1141.9  1142.6  1144.1  1144.5  1145.3  1145.8    1148  1149.4  1150.5
  1151.1  1152.7  1156.1  1159.9  1160.7    1163  1165.6  1166.2  1167.8  1168.8
                                                                                
                                                                                
                                                          1129.9  1129.9
                                                                                
                                                                                
                                                                                
Pier Skew, UpSta & Num, DnSta & Num=  ,752, 2 ,690, 2 , 0 , 0 , 0 ,,
       1       1
  1118.6  1130.5
       1       1
  1118.5  1130.4
Pier Skew, UpSta & Num, DnSta & Num=  ,787, 2 ,725, 2 , 0 , 0 , 0 ,,
       1       1
  1115.9  1130.5
       1       1
  1115.8  1130.4
Abutment Skew #Up #Dn= , 2 , 2
     717     735
  1128.5  1121.9
     655     673
  1128.4  1121.8
Abutment Skew #Up #Dn= , 2 , 2
     803     822
  1119.2  1129.1
     741     760
  1119.1    1129
BR Coef=-1 , 1 , 0 ,, 0 ,,,0.8,0,1.2,0,
WSPro=,,,, 1 ,,,, 0 ,,,, 0 ,,,,-1 ,-1 ,-1 , 0 , 0 , 0 , 0 , 0
BC Design=,, 0 ,, 0 ,,,,,,

Type RM Length L Ch R = 1 ,11887.11,554.72,571.22,599.7
BEGIN DESCRIPTION:
Down stream xs of Bridge 37003-0008
END DESCRIPTION:
XS GIS Cut Line= 3
  1347868.041348   813632.598871  1347048.710545   814249.981966
  1346765.983735   814573.098327
#Sta/Elev= 30
       0  1156.1   104.4  1153.4   168.1  1148.7   239.9    1145   265.4  1142.7
   339.8  1140.6   489.2  1131.3   521.4  1127.5   534.4  1126.8   614.8  1124.8
   652.2  1125.6     690  1119.5     693  1114.3     703  1113.4     722  1114.7
     725  1116.8     741  1119.1   764.1  1124.8   790.6  1123.7   813.4  1125.7
   830.6  1125.5   881.3  1127.9   946.8  1135.9  1025.3  1140.4  1124.9  1144.2
  1208.9  1150.2  1239.1  1150.8  1327.9  1156.8  1405.6  1164.4  1455.2  1167.6
#Mann= 3 , 0 , 0
       0     .08       0     690     .05       0     741      .1       0
#XS Ineff= 2 , 0
       0     576  1130.1     839       0  1130.1
Permanent Ineff=
       F       F
Bank Sta=690,741
Exp/Cntr=0.5,0.3

Type RM Length L Ch R = 1 ,11315.89,1246.17,1249.86,1251.74
XS GIS Cut Line= 3
  1347810.342003   813580.669488  1347492.995559   813488.350508
  1346379.398067   813678.758384
#Sta/Elev= 30
       0 1150.03   19.43    1148   39.89 1147.48   58.76 1145.38  183.76 1136.24
  221.86 1136.47  237.64 1135.33  297.54  1133.9  397.12 1133.53  546.07 1136.26
  614.95  1134.3  655.43 1131.19  689.75 1126.26  721.97 1123.43  741.78 1114.76
  747.33 1113.05  788.43 1111.12  798.95 1112.12  814.06 1119.35  849.54 1117.87
  893.64 1120.11  949.79 1120.62  992.49 1123.17 1016.09 1127.22  1039.2 1134.39
 1070.87 1141.33 1194.44 1157.21 1228.79 1162.38 1272.03 1170.35 1460.26 1196.73
#Mann= 3 , 0 , 0
       0     .08       0  747.33     .05       0  814.06     .12       0
Bank Sta=747.33,814.06
Exp/Cntr=0.3,0.1

Type RM Length L Ch R = 1 ,10066.03,1509.06,1500.92,1481.86
XS GIS Cut Line= 4
  1348785.461001   811895.848414  1347568.004698   812397.832773
  1347117.949769   812426.682446  1346287.079133   813003.675943
#Sta/Elev= 30
       0 1195.83  206.45 1192.99  372.58 1183.59  458.82 1174.81  630.53 1153.77
  755.78 1144.73  949.83 1116.74  967.76 1116.77   980.3 1114.45 1002.73 1115.94
 1005.72 1111.44 1013.42 1115.96 1261.46 1115.83 1378.68 1117.67 1577.28 1114.88
 1620.08 1106.38  1630.6 1108.19  1642.9 1114.36 1647.39  1116.8 1698.32 1117.36
 1817.77 1131.47 1940.01 1142.69 2038.04 1144.57  2074.5 1147.75  2096.8 1151.67
 2142.87 1151.77 2187.89 1157.61 2342.81 1168.21  2541.8 1186.96 2779.43  1198.8
#Mann= 3 , 0 , 0
       0     .08       0 1577.28     .05       0  1642.9     .08       0
#XS Ineff= 2 , 0
       0 1378.68 1117.67               0
Permanent Ineff=
       F       F
Bank Sta=1577.28,1642.9
Exp/Cntr=0.3,0.1