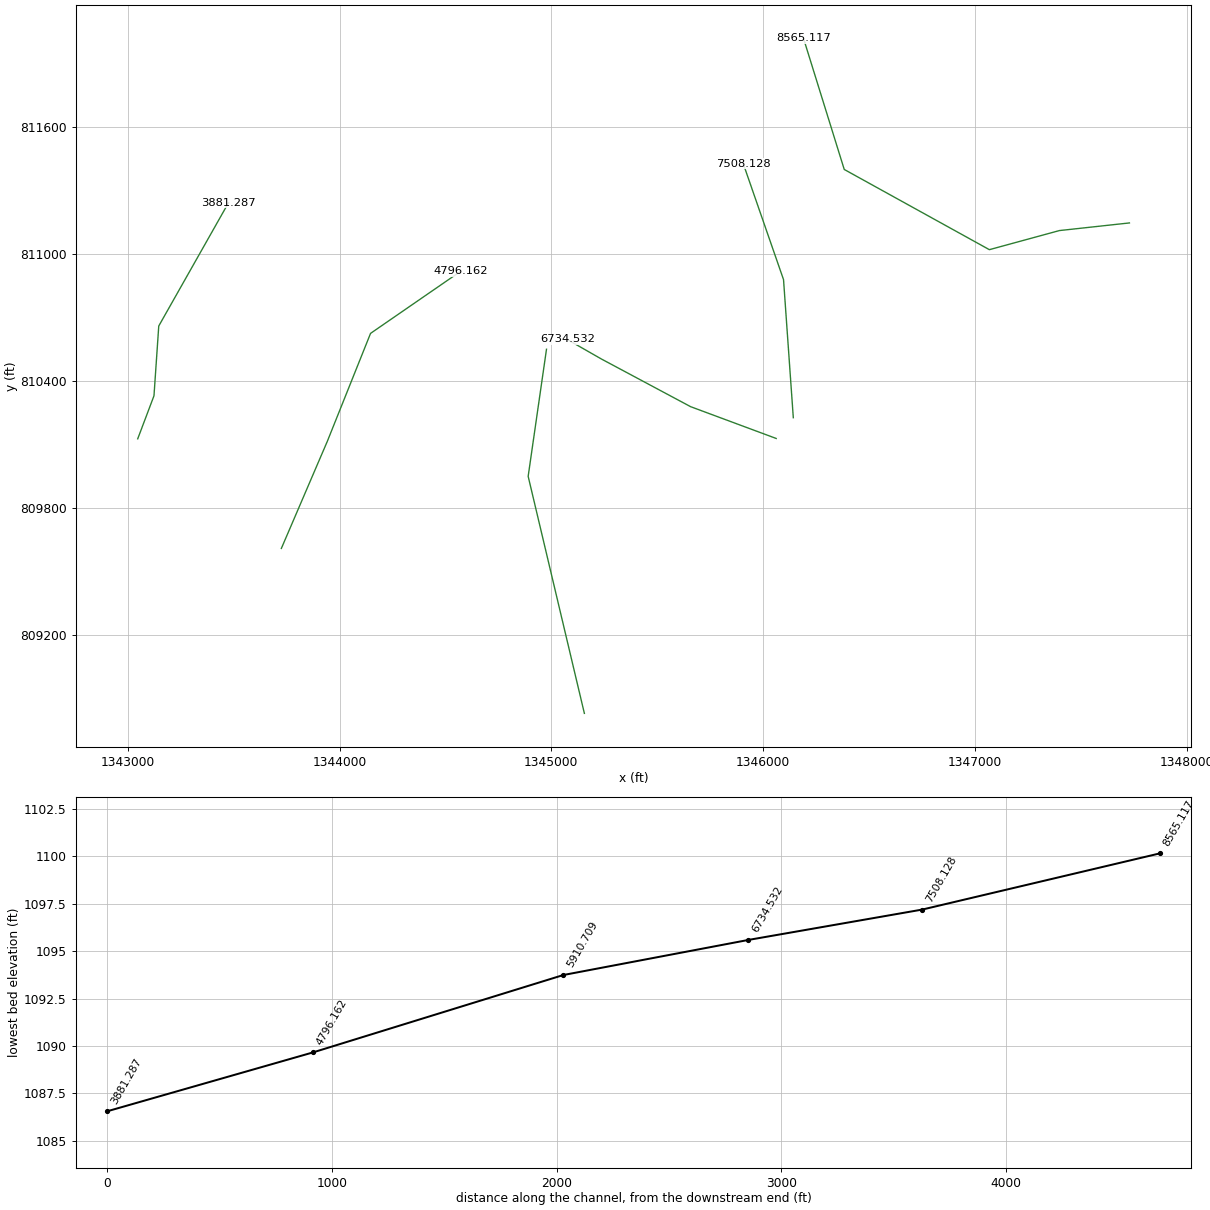
HEC-RAS study GrassyCreek.prj: GrassyCreek

--- GrassyCreek.g01 (geometry) --- (continued)

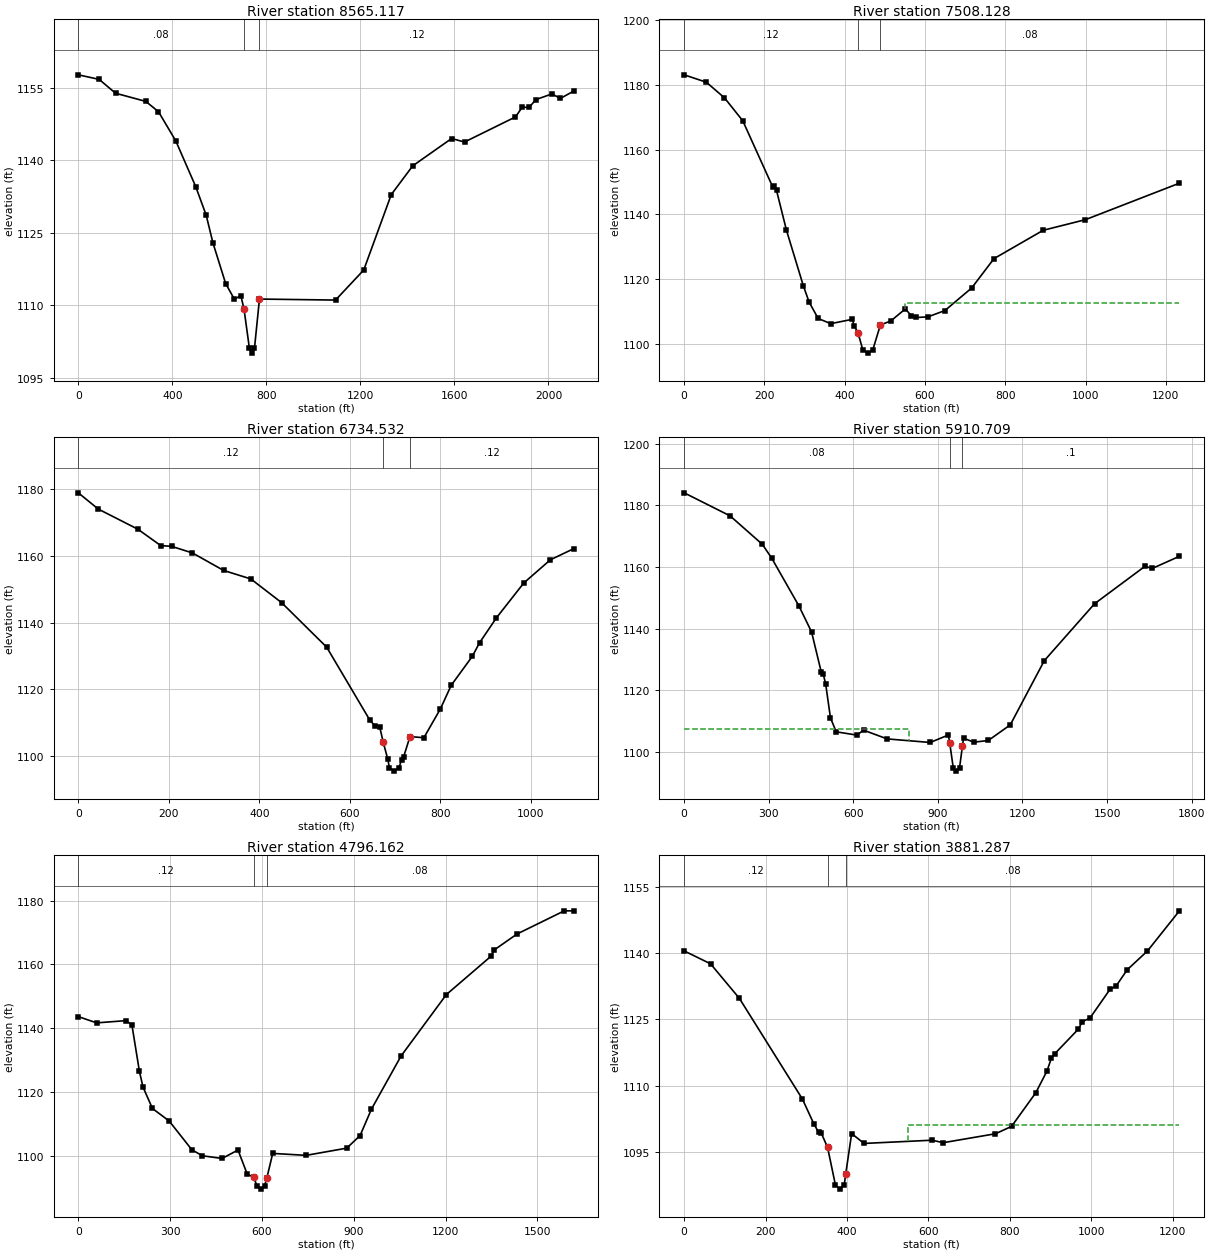
Type RM Length L Ch R = 1 ,8565.117,1084.95,1056.99,1023.23
XS GIS Cut Line= 5
  1347730.047748   811148.055572  1347399.390934   811111.983912
   1347068.73412   811021.804785  1346383.372766   811400.557145
  1346190.990579   812019.787147
#Sta/Elev= 30
       0 1157.64   88.63  1156.7  158.36 1153.84  287.18 1152.15  341.06 1150.02
  414.51 1144.01  499.63 1134.53  544.06 1128.63   572.7 1122.93  626.75 1114.53
  664.12 1111.27  691.35 1112.05  705.13 1109.19  727.82 1101.15  738.83 1100.15
   749.4 1101.15  770.63 1111.32  1094.2 1111.11 1214.21 1117.32 1331.38 1132.91
 1422.72 1138.84 1587.87 1144.48 1642.92 1143.76  1859.7 1148.94 1888.39 1150.95
 1917.69  1150.9 1946.43 1152.52 2015.06  1153.7 2050.48 1152.76 2106.83 1154.26
#Mann= 3 , 0 , 0
       0     .08       0  705.13     .05       0  770.63     .12       0
Bank Sta=705.13,770.63
Exp/Cntr=0.3,0.1

Type RM Length L Ch R = 1 ,7508.128,741.01,773.6,802.84
XS GIS Cut Line= 3
  1346142.830724   810228.337182  1346096.671257   810880.339819
  1345906.263381   811428.483691
#Sta/Elev= 30
       0 1183.13   55.29 1180.85   100.4 1176.03  145.97 1168.95  220.18 1148.63
  224.81 1148.78  230.15 1147.42  254.92 1135.12  296.74 1118.06  311.22 1112.98
  333.83 1107.89  365.21 1106.29  419.36 1107.64  422.76 1105.72  432.97 1103.55
   445.1 1098.19   457.5 1097.19     470 1098.19  488.91  1105.9  514.83 1107.12
  551.17 1110.86  565.42  1108.8  578.78  1108.2  607.01 1108.37  649.71 1110.35
  716.36 1117.31  771.85 1126.37  894.47 1135.12  999.67  1138.4 1233.91 1149.67
#Mann= 3 , 0 , 0
       0     .12       0  432.97     .05       0  488.91     .08       0
#XS Ineff= 2 , 0
                          549.99         1112.52
Permanent Ineff=
       F       F
Bank Sta=432.97,488.91
Exp/Cntr=0.3,0.1

Type RM Length L Ch R = 1 ,6734.532,849.02,823.82,797.58
XS GIS Cut Line= 4
  1346062.051622   810130.248286  1345658.156206   810280.266564
  1345236.950903   810505.294076  1345075.392746   810597.613009
#Sta/Elev= 30
       0 1178.77   44.07 1173.92  131.61  1167.9  182.25 1162.99  205.95 1162.78
  252.23  1160.8  321.16 1155.57  381.29 1153.03  449.32 1145.94  548.88 1132.64
  643.56 1110.99     655 1109.13  665.92  1108.9  673.51 1104.41  683.79 1099.21
  687.54 1096.59   697.9 1095.59  708.66 1096.59  714.59 1099.05  719.02 1099.91
  733.01 1105.92  763.61 1105.57  800.02 1114.15  824.07 1121.24  870.65 1129.89
  886.62 1133.94  923.86 1141.38  984.55 1151.84 1043.22 1158.75 1094.48 1162.06
#Mann= 3 , 0 , 0
       0     .12       0  673.51     .05       0  733.01     .12       0
Bank Sta=673.51,733.01
Exp/Cntr=0.3,0.1

Type RM Length L Ch R = 1 ,5910.709,1134.08,1114.55,1090.64
XS GIS Cut Line= 3
  1345156.171848   808832.012881  1344890.754832   809951.380288
   1344977.30385   810551.453543
#Sta/Elev= 30
       0 1184.07  162.93 1176.59  277.35 1167.35  310.17 1162.92  407.36 1147.31
  451.97  1138.9  485.93 1126.03  492.87 1125.38  501.83  1122.1  519.03 1110.98
  539.47  1106.5  612.79 1105.43  636.21 1107.04  719.91  1104.2  872.56 1103.04
  937.14 1105.46  942.11 1102.77  954.59 1094.73  965.53 1093.74  976.66 1094.75
  987.14 1101.94  990.83 1104.43 1027.54 1103.13 1078.82 1103.69 1156.67 1108.75
 1277.45  1129.6 1455.71 1148.07 1634.16  1160.2 1660.88 1159.55 1756.69 1163.47
#Mann= 3 , 0 , 0
       0     .08       0  942.11     .05       0  987.14      .1       0
#XS Ineff= 2 , 0
          799.22 1107.55
Permanent Ineff=
       F       F
Bank Sta=942.11,987.14
Exp/Cntr=0.3,0.1

Type RM Length L Ch R = 1 ,4796.162,903.16,914.88,925.53
XS GIS Cut Line= 4
  1343725.227912   809610.954133  1343942.573176   810117.342995
  1344146.433168   810626.462682  1344573.408387    810920.72937
#Sta/Elev= 30
       0 1143.66   59.76  1141.7  154.84 1142.39  174.96 1141.16  199.58 1126.56
  211.31 1121.62  242.22  1114.9  296.83 1110.99  371.22 1101.95  405.63  1100.1
  469.83 1099.26  521.72  1101.9  552.08 1094.31  573.63 1093.42  583.37 1090.62
   595.6 1089.66   608.3 1090.65   616.1  1093.2   635.1 1100.84  744.28 1100.23
  877.05 1102.49  920.64 1106.44  957.68 1114.69 1054.49 1131.34 1202.38 1150.55
 1348.56 1162.58 1359.17 1164.55 1433.38 1169.52 1587.52 1176.76 1618.04 1176.77
#Mann= 3 , 0 , 0
       0     .12       0  573.63     .05       0   616.1     .08       0
Bank Sta=573.63,616.1
Exp/Cntr=0.3,0.1

Type RM Length L Ch R = 1 ,3881.287,815.91,835.75,852.77
XS GIS Cut Line= 4
  1343046.959789   810128.530694  1343123.716555   810331.710356
  1343146.292047   810661.312866  1343475.894558    811243.76112
#Sta/Elev= 30
       0 1140.47   64.82 1137.55   135.7 1129.73  290.61 1106.93  318.19 1101.41
  330.18 1099.43  336.71 1099.26  352.34 1096.01  371.51 1087.56  382.38 1086.56
  393.38 1087.56  396.91 1089.97  411.47 1099.13  441.95  1096.9  609.01 1097.63
  636.56 1097.07  764.81 1099.09  804.42 1100.76  863.76 1108.35  891.32 1113.27
  902.32 1116.23  910.04 1117.15  968.84  1122.8  977.97 1124.46  996.87 1125.25
 1046.03 1131.74 1061.23 1132.53 1088.61 1136.21 1138.22 1140.45 1216.81 1149.54
#Mann= 3 , 0 , 0
       0     .12       0  352.34     .05       0  396.91     .08       0
#XS Ineff= 2 , 0
                          549.87         1101.12
Permanent Ineff=
       F       F
Bank Sta=352.34,396.91
Exp/Cntr=0.3,0.1