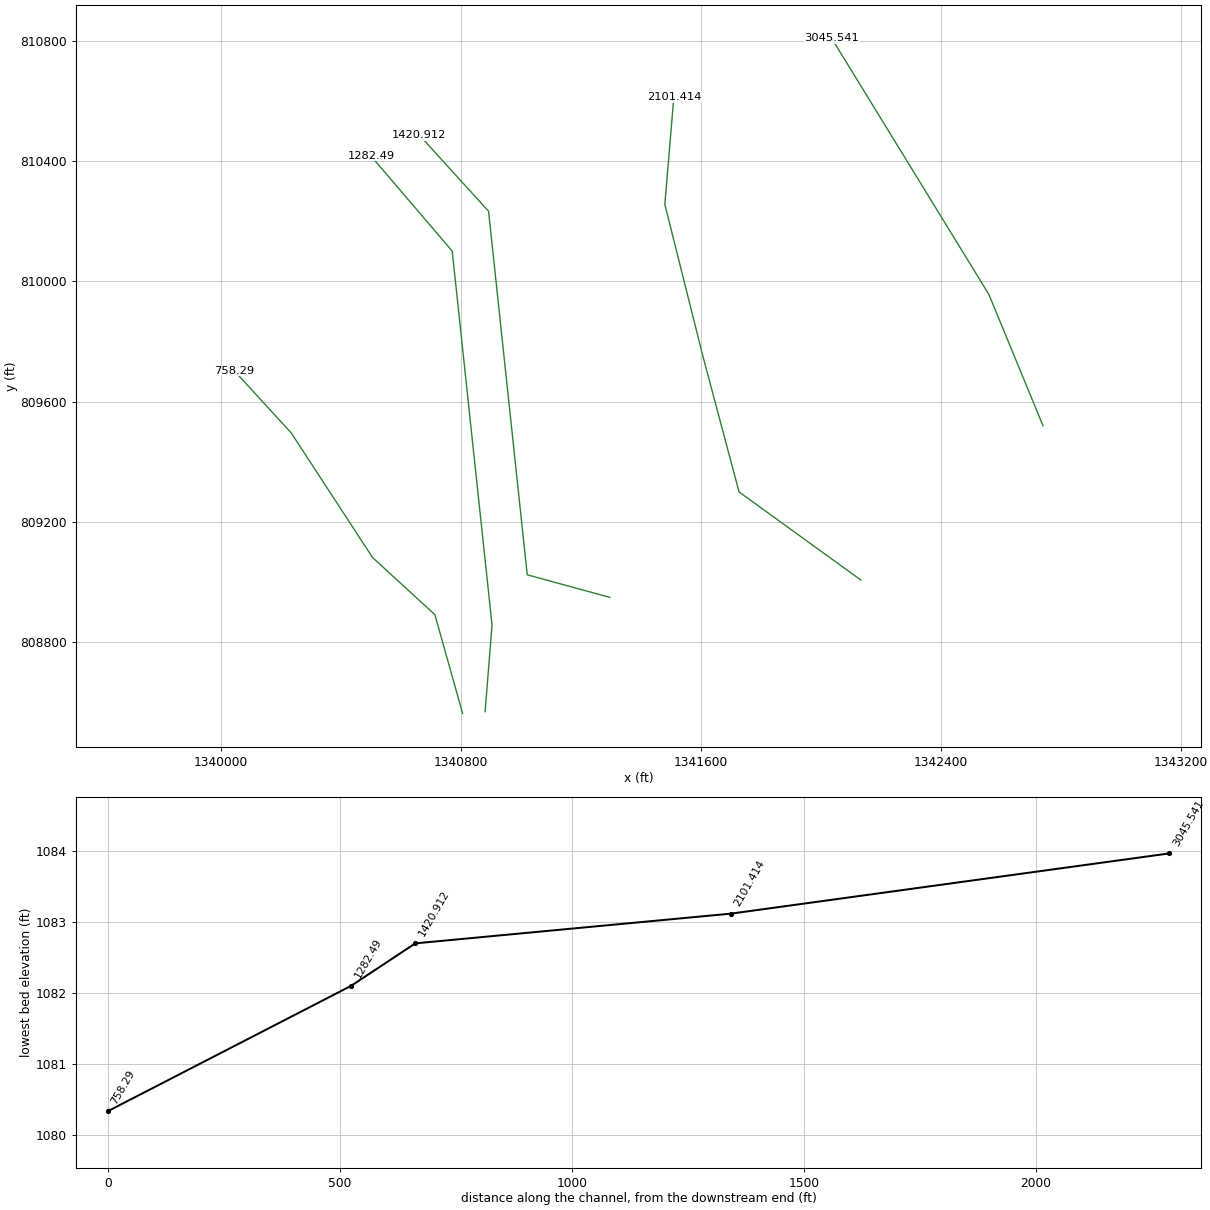
HEC-RAS study GrassyCreek.prj: GrassyCreek

--- GrassyCreek.g01 (geometry) --- (continued)

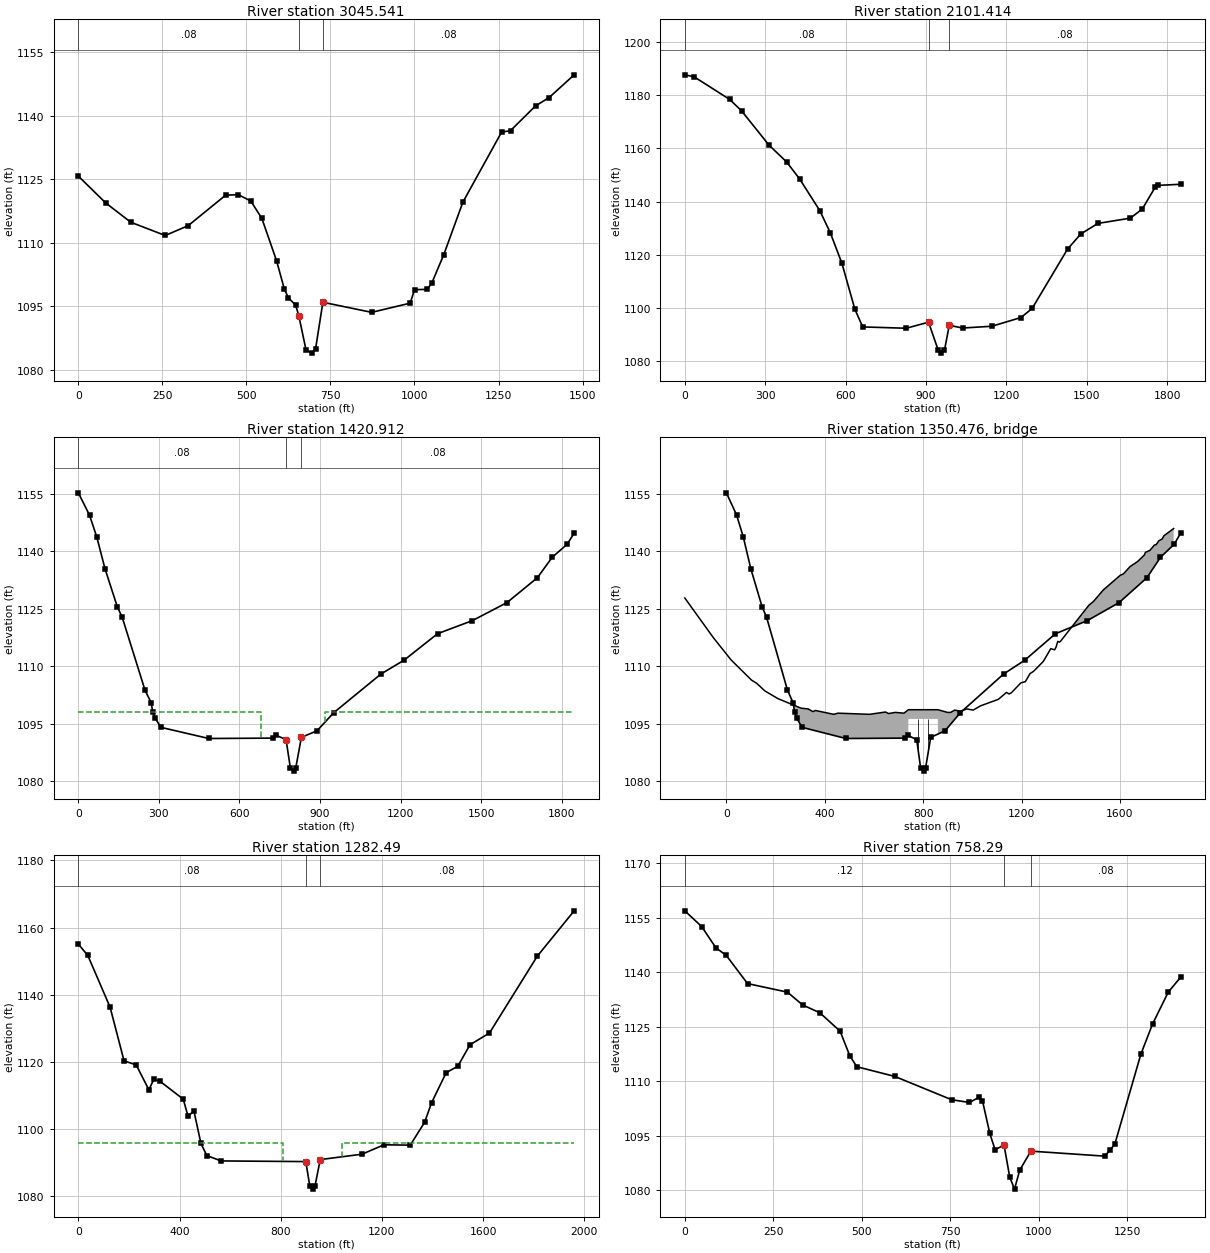
Type RM Length L Ch R = 1 ,3045.541,951.81,944.13,934.78
XS GIS Cut Line= 3
  1342739.932771   809518.991803  1342559.328695   809956.956815
   1342035.57672   810810.311253
#Sta/Elev= 30
       0 1125.77   81.19 1119.45  156.15 1114.87  258.39 1111.75  326.69 1114.06
  438.19 1121.26  475.96 1121.38  513.03 1119.89  545.99 1115.77  589.76 1105.78
  612.65 1099.15  625.19 1096.97  646.32 1095.34  655.79 1092.81  677.42  1084.7
  694.28 1083.97  705.75 1084.97   727.5 1095.98  872.58  1093.6  987.26 1095.77
 1000.11 1098.96 1037.47 1099.02 1051.05 1100.43 1087.06  1107.2 1144.07 1119.63
 1259.03 1136.14 1285.64  1136.5 1360.04 1142.34 1400.51 1144.31 1475.01 1149.68
#Mann= 3 , 0 , 0
       0     .08       0  655.79     .05       0   727.5     .08       0
Bank Sta=655.79,727.5
Exp/Cntr=0.3,0.1

Type RM Length L Ch R = 1 ,2101.414,685.38,680.5,675.43
XS GIS Cut Line= 5
  1342132.725818   809005.110916   1341726.89991   809298.863142
  1341606.734339   809749.755749  1341479.599959   810256.905269
  1341509.572854   810614.922804
#Sta/Elev= 30
       0 1187.61   34.57 1186.88  167.51 1178.37  211.55 1174.11  314.31  1161.2
  379.65 1154.92  428.43 1148.51  503.38 1136.67  543.14 1128.23  586.18 1116.84
  634.35 1099.62  663.77 1092.96   826.3 1092.46  909.32 1094.74  945.71 1084.12
  957.23 1083.12   968.6 1084.12  986.58 1093.57 1036.14 1092.55 1145.39 1093.21
 1254.28 1096.49 1296.12 1099.94 1427.92 1122.18 1477.41 1127.87 1541.04 1131.82
 1662.11  1133.8 1706.77 1137.23 1755.46 1145.52 1764.11 1146.09 1849.73 1146.52
#Mann= 3 , 0 , 0
       0     .08       0  909.32     .05       0  986.58     .08       0
Bank Sta=909.32,986.58
Exp/Cntr=0.5,0.3

Type RM Length L Ch R = 1 ,1420.912,138.38,138.43,138.43
BEGIN DESCRIPTION:
Upstream xs of Bridge 37003-0012
END DESCRIPTION:
XS GIS Cut Line= 4
  1341296.085221   808947.411571  1341021.056491   809022.626067
  1340892.189758   810234.107098  1340661.392378   810487.984235
#Sta/Elev= 30
       0  1155.2    41.6  1149.4    68.7  1143.7    99.4  1135.4   145.2  1125.5
   163.3  1122.8   248.3  1103.8   271.2  1100.5   277.5    1098   285.1  1096.6
   307.8  1094.1   485.8  1091.2   724.1  1091.3   737.9    1092   773.7  1090.9
   789.7  1083.5   803.7  1082.7   809.7  1083.5   830.7  1091.5   888.8  1093.2
   950.8  1097.9    1127    1108  1213.1  1111.6  1337.8  1118.5  1467.2  1121.9
  1596.4  1126.6  1709.9  1133.1  1764.7  1138.4  1820.4  1141.8  1846.6  1144.7
#Mann= 3 , 0 , 0
       0     .08       0   773.7     .05       0   830.7     .08       0
#XS Ineff= 2 , 0
       0   681.3    1098   918.1       0    1098
Permanent Ineff=
       F       F
Bank Sta=773.7,830.7
Exp/Cntr=0.5,0.3

Type RM Length L Ch R = 3 ,1350.476,,,
BEGIN DESCRIPTION:
Kirby Lick Rd, SR 1328;  Bridge : 37003-0012
END DESCRIPTION:
Bridge Culvert--1,0,-1,-1, 0
Deck Dist Width WeirC Skew NumUp NumDn MinLoCord MaxHiCord MaxSubmerge Is_Ogee
58.4,24,2.6,0, 60, 60, , , 0.95, 0, 0,0,,
  -169.1   -52.2    18.7   102.3   122.8   156.3   209.1   303.6   332.7   351.4
   362.1   435.9   453.5   582.3   646.8   659.4   686.8   721.9   739.7   739.7
   859.7   859.7   898.7   911.8   928.2   951.3   977.1  1003.3  1032.9  1105.5
  1138.8    1149  1158.3  1197.2  1215.4  1234.3  1248.8  1288.6  1318.6  1334.4
  1340.2  1347.2  1354.3  1359.2  1473.4  1492.2  1532.3  1600.8  1614.2  1641.3
  1671.7    1699  1703.6  1721.6    1740    1747  1757.9  1771.8  1778.4  1818.2
  1127.8  1117.4  1111.7  1106.4  1105.6  1103.6  1101.6  1099.1  1098.9  1098.2
  1098.5  1097.5  1097.8  1097.5  1098.1  1097.7    1098  1097.8  1098.7  1098.7
  1098.7  1098.7    1098    1098  1098.6  1098.3  1098.9  1098.6  1099.7  1101.4
  1103.2  1102.8  1103.1  1105.7    1106  1108.1  1108.7  1111.3  1114.6  1114.3
    1115  1116.5  1116.3  1116.6  1125.9  1126.9  1129.9  1133.7  1134.1    1136
  1137.3    1139  1139.7  1140.2  1141.6  1141.7  1142.7  1143.2    1144  1145.9
                                                                                
                                                                          1096.3
  1096.3
                                                                                
                                                                                
                                                                                
   -43.5    73.4   144.3   227.9   248.4   281.9   334.7   429.2   458.3     477
   487.7   561.5   579.1   707.9     746     760   772.4     785   865.3   865.3
   985.3   985.3  1017.5  1037.4  1053.8  1076.9  1102.7  1128.9  1158.5  1231.1
  1264.3  1274.6  1283.9  1322.8  1340.9  1359.9  1374.3  1414.2  1444.2    1460
  1465.8  1472.8  1479.9  1484.8    1599  1617.8  1657.9  1726.4  1739.8  1766.9
  1797.3  1824.6  1829.2  1847.2  1865.6  1872.6  1883.5  1897.4    1904  1943.8
  1127.8  1117.4  1111.7  1106.4  1105.6  1103.6  1101.6  1099.1  1098.9  1098.2
  1098.5  1097.5  1097.8  1097.5    1098  1097.8  1098.1  1097.7  1098.1  1098.1
  1098.1  1098.1  1098.3    1098  1098.6  1098.3  1098.9  1098.6  1099.7  1101.4
  1103.2  1102.8  1103.1  1105.7    1106  1108.1  1108.7  1111.3  1114.6  1114.3
    1115  1116.5  1116.3  1116.6  1125.9  1126.9  1129.9  1133.7  1134.1    1136
  1137.3    1139  1139.7  1140.2  1141.6  1141.7  1142.7  1143.2    1144  1145.9
                                                                                
                                                                          1095.7
  1095.7
                                                                                
                                                                                
                                                                                
Pier Skew, UpSta & Num, DnSta & Num=  ,779.68, 2 ,905.27, 2 , 0 , 0 , 0 ,,
       1       1
 1086.45 1096.75
       1       1
 1085.91 1096.21
Pier Skew, UpSta & Num, DnSta & Num=  ,819.68, 2 ,945.27, 2 , 0 , 0 , 0 ,,
       1       1
 1085.95 1096.75
       1       1
 1085.41 1096.21
Abutment Skew #Up #Dn= , 3 , 3
   739.7   757.7   773.7
  1093.9  1092.7  1090.9
   865.3   883.3   899.3
  1093.9  1092.7  1090.3
Abutment Skew #Up #Dn= , 2 , 2
   830.7   859.7
  1091.5  1094.7
   956.3   985.3
  1090.9  1094.7
BR Coef=-1 , 1 , 0 ,, 0 ,,,0.8,0,1.2,0,
WSPro=,,,, 1 ,,,, 0 ,,,, 0 ,,,,-1 ,-1 ,-1 , 0 , 0 , 0 , 0 , 0
BC Design=,, 0 ,, 0 ,,,,,,

Type RM Length L Ch R = 1 ,1282.49 ,507.68,524.2,540.09
BEGIN DESCRIPTION:
Down stream xs of Bridge 37003-0012
END DESCRIPTION:
XS GIS Cut Line= 4
  1340880.649926   808566.595865  1340903.729637   808855.092591
  1340771.021152   810101.398613  1340499.834174   810418.745011
#Sta/Elev= 30
       0  1155.1    37.5  1151.7   125.5  1136.3   180.8  1120.3   228.8  1119.1
   278.9  1111.7   298.4  1114.8   321.6  1114.3   414.7  1108.9   433.8  1103.8
   456.9  1105.4   484.7  1095.7   507.8  1092.1   564.4  1090.5   899.3  1090.3
   915.3  1082.9   929.3  1082.1   935.3  1082.9   956.3  1090.9  1121.2  1092.5
  1208.1  1095.3  1312.2  1095.2    1369    1102  1396.3  1107.8  1454.3  1116.8
  1500.1  1118.7  1548.3  1125.1  1625.4  1128.6  1814.5  1151.5  1960.2    1165
#Mann= 3 , 0 , 0
       0     .08       0   899.3     .05       0   956.3     .08       0
#XS Ineff= 2 , 0
       0   809.2  1095.9  1041.3       0  1095.9
Permanent Ineff=
       F       F
Bank Sta=899.3,956.3
Exp/Cntr=0.5,0.3

Type RM Length L Ch R = 1 ,758.29  ,751.67,758.29,764.09
XS GIS Cut Line= 5
  1340805.640741   808560.825903  1340713.321807   808889.712226
  1340505.604137   809080.120102  1340234.417159   809495.555396
  1340044.009329   809703.273067
#Sta/Elev= 30
       0 1156.95   47.73 1152.62   87.93 1146.76  117.17 1144.68  177.35 1136.92
  290.04 1134.56  333.15 1131.03  381.88 1128.87     439  1123.8  466.11 1117.08
  486.06 1114.03  593.69 1111.35  754.16 1104.94   804.5 1104.19  831.68 1105.63
  841.29 1104.66  862.02 1095.65  876.94 1091.18  902.21 1092.46  918.41  1083.6
   931.8 1080.33  946.56 1085.56  978.15 1090.79  1186.5 1089.41 1202.18  1091.1
 1215.56  1092.8  1288.8 1117.44 1321.87 1125.78 1366.28 1134.56 1401.28 1138.66
#Mann= 3 , 0 , 0
       0     .12       0  902.21     .05       0  978.15     .08       0
Bank Sta=902.21,978.15
Exp/Cntr=0.3,0.1

Chan Stop Cuts=-1
Use User Specified Reach Order=0
User Specified Reach Order=GrassyCreek     ,Main