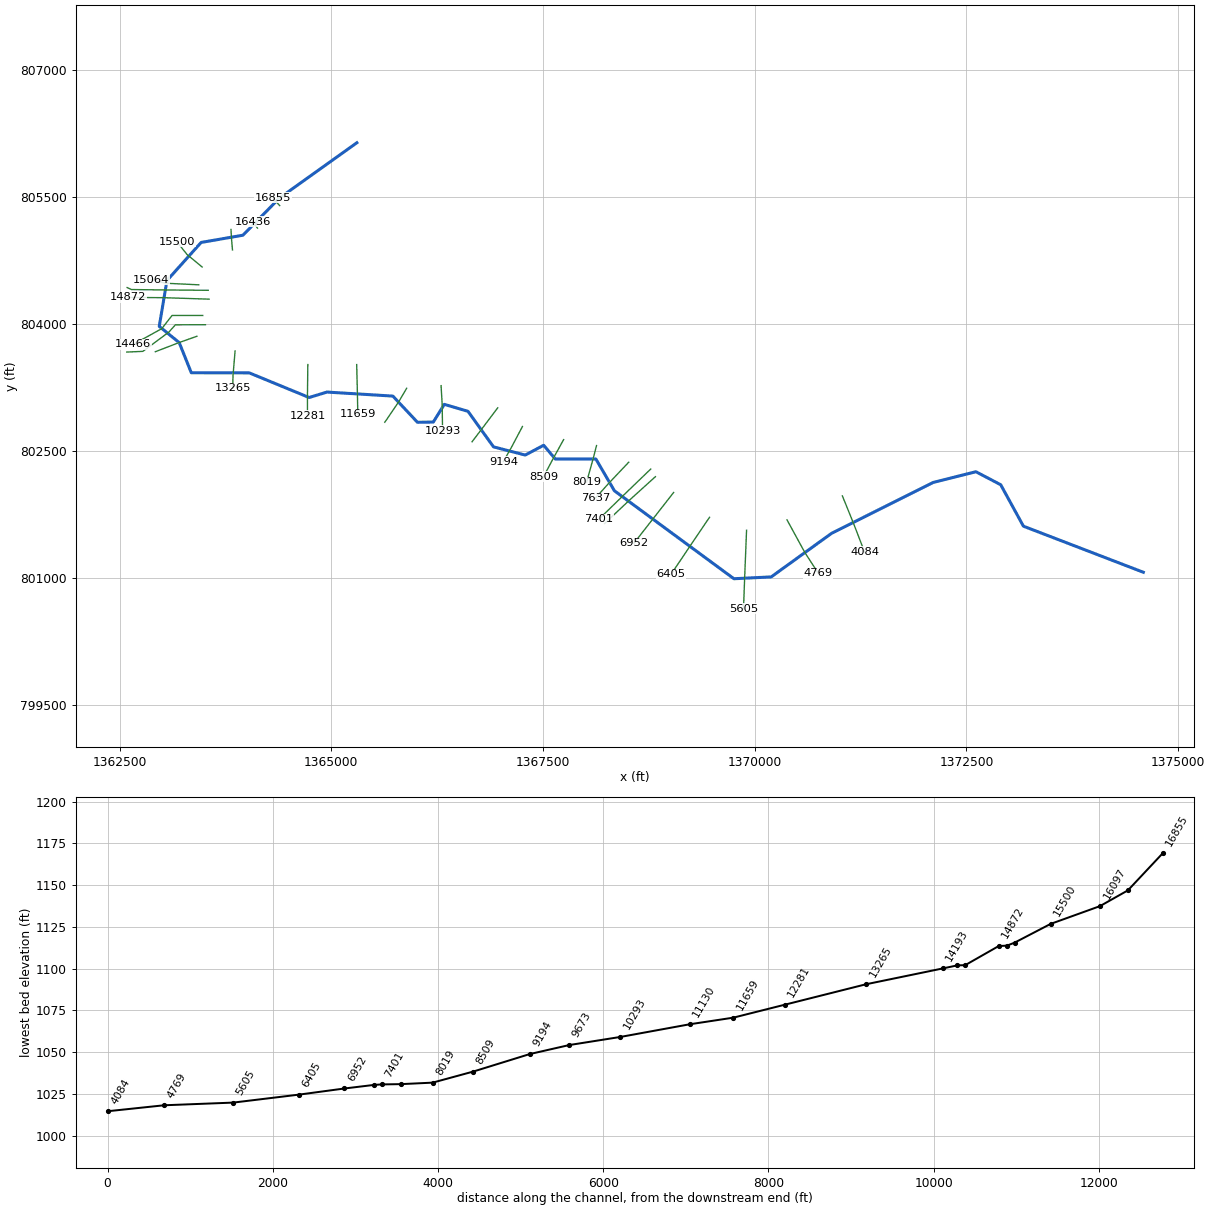
--- Greasy Creek.prj (project) ---

Proj Title=Greasy Creek Limited Detail Study
Current Plan=p01
Default Exp/Contr=0.3,0.1
English Units
Geom File=g01
Flow File=f01
Plan File=p01
Y Axis Title=Elevation
X Axis Title(PF)=Main Channel Distance
X Axis Title(XS)=Station
BEGIN DESCRIPTION:
Greasy Creek
END DESCRIPTION:
DSS Export Rating Curves= 0
DSS Export Rating Curve Sorted= 0
DSS Export Volume Flow Curves= 0
DXF OffsetX= 0
DXF OffsetY= 0
DXF ScaleX= 1
DXF ScaleY= 10

--- Greasy Creek.p01 (plan) ---

Plan Title=Floodway Run
Program Version=3.12
Short Identifier=Floodway
Geom File=g01
Flow File=f01
Subcritical Flow
K Sum by GR= 0
Std Step Tol= 0.01
Critical Tol= 0.01
Num of Std Step Trials= 20
Max Error Tol= 0.3
Flow Tol Ratio= 0.001
Split Flow NTrial= 30
Split Flow Tol= 0.02
Split Flow Ratio= 0.02
Log Output Level= 0
Friction Slope Method= 1
Unsteady Friction Slope Method= 2
Unsteady Bridges Friction Slope Method= 1
Parabolic Critical Depth
Global Vel Dist= 0 , 0 , 0
Global Log Level= 0
CheckData=True
Encroach Param=-1 ,0,0, 2
Encroach River=Greasy Creek
Encroach Reach=Reach-1
Encroach Node=16855
       1  4988.4  5003.1
Encroach Node=16436
       1  4992.3  5003.1
Encroach Node=16097
       1    4990  5003.5
Encroach Node=15500
       1    4987    5004
Encroach Node=15064
       1 4899.78 5008.33
Encroach Node=14972
       1    4981    5019
Encroach Node=14872
       1    4981    5019
Encroach Node=14466
       1  4987.5    5015
Encroach Node=14373
       1  4987.5    5015
Encroach Node=14193
       1    4995  5004.5
Encroach Node=13265
       1    4991    5004
Encroach Node=12281
       1    4992  5005.1
Encroach Node=11659
       1    4992    5008
Encroach Node=11130
       1    4992    5008
Encroach Node=10293
       1  4988.7    5008
Encroach Node=9673
       1    4991    5009
Encroach Node=9194
       1    4992    5007
Encroach Node=8509
       1  4992.5    5008
Encroach Node=8019
       1    4993    5007
Encroach Node=7637
       1    4993    5007
Encroach Node=7401
       1  4978.5  5021.5
Encroach Node=7310
       1  4978.5  5021.5
Encroach Node=6952
       1    4988    5009
Encroach Node=6405
       1    4986    5010
Encroach Node=5605
       1 4923.38 5013.18
Encroach Node=4769
       1 4917.72 5010.71
Encroach Node=4084
       1 4926.89 5122.26
Encroach Node=3641
       1 4992.17  5010.8
Encroach Node=3120
       1    4990 5013.18
Encroach Node=2757
       1    4983    5013
Encroach Node=2643
       1    4983    5013
Encroach Node=2197
       1    4981 5132.25
Encroach Node=1389
       1    4910    5010
Encroach Node=500
       1    4967    5017
BEGIN DESCRIPTION:
Floodway Run
END DESCRIPTION:
Computation Interval=1HOUR
Output Interval=1HOUR
Run HTab= 0
Run UNet= 0
Run PostProcess= 0
UNET Theta= 1
UNET Theta Warmup= 1
UNET ZTol= 0.02
UNET ZSATol= 0.05
UNET MxIter= 20
UNET MaxInSteps= 0
UNET DtIC= 0
UNET DtMin= 0
UNET MaxCRTS= 20
UNET WFStab= 2
UNET SFStab= 1
UNET WFX= 1
UNET SFX= 1
UNET DSS MLevel= 4
UNET DZMax Abort= 100
UNET Convert EG Bridges=-1
UNET Use Existing IB Tables=-1
UNET Froude Reduction=False
UNET Froude Limit= 1
UNET Froude Power= 10
Instantaneous Interval=1HOUR
Write IC File= 0
Echo Input=False
Echo Output=False
Write Detailed= 0
Detailed Automatic Start=False, 10

--- Greasy Creek.f01 (steady flow) ---

Flow Title=Floodway
Program Version=3.12
Number of Profiles= 2
Profile Names=100-year,100-FW
River Rch & RM=Greasy Creek,Reach-1         ,16855
     483     483
River Rch & RM=Greasy Creek,Reach-1         ,12281
     664     664
River Rch & RM=Greasy Creek,Reach-1         ,10293
     849     849
River Rch & RM=Greasy Creek,Reach-1         ,5605
    1751    1751
River Rch & RM=Greasy Creek,Reach-1         ,3120
    1826    1826
Boundary for River Rch & Prof#=Greasy Creek,Reach-1         , 1
Up Type= 0
Dn Type= 3
Dn Slope=0.005
Boundary for River Rch & Prof#=Greasy Creek,Reach-1         , 2
Up Type= 0
Dn Type= 3
Dn Slope=0.005
DSS Import GetInterval= 0
DSS Import GetPeak= 0
DSS Import FillOption= 0

--- Greasy Creek.g01 (geometry) ---

Geom Title=Existing Conditions

River Reach=Greasy Creek,Reach-1
Reach XY= 30
      1365301.63       806143.63      1364387.77       805490.21
      1363956.33       805050.64      1363462.83       804965.17
      1363059.00       804514.56      1362968.31       803973.07
      1363204.38       803780.76      1363346.83       803424.62
      1364030.61       803423.60      1364738.50       803132.06
      1364948.63       803196.50      1365726.84       803148.87
      1366017.38       802839.31      1366204.06       802841.58
      1366334.31       803051.19      1366614.13       802968.77
      1366915.32       802548.53      1367289.77       802451.86
      1367507.75       802567.56      1367645.00       802405.06
      1368124.00       802405.06      1368342.63       802029.69
      1369754.15       800989.71      1370194.22       801011.29
      1370907.27       801526.62      1372107.55       802128.27
      1372611.25       802254.63      1372904.39       802100.67
      1373172.34       801610.92      1374588.38       801066.25

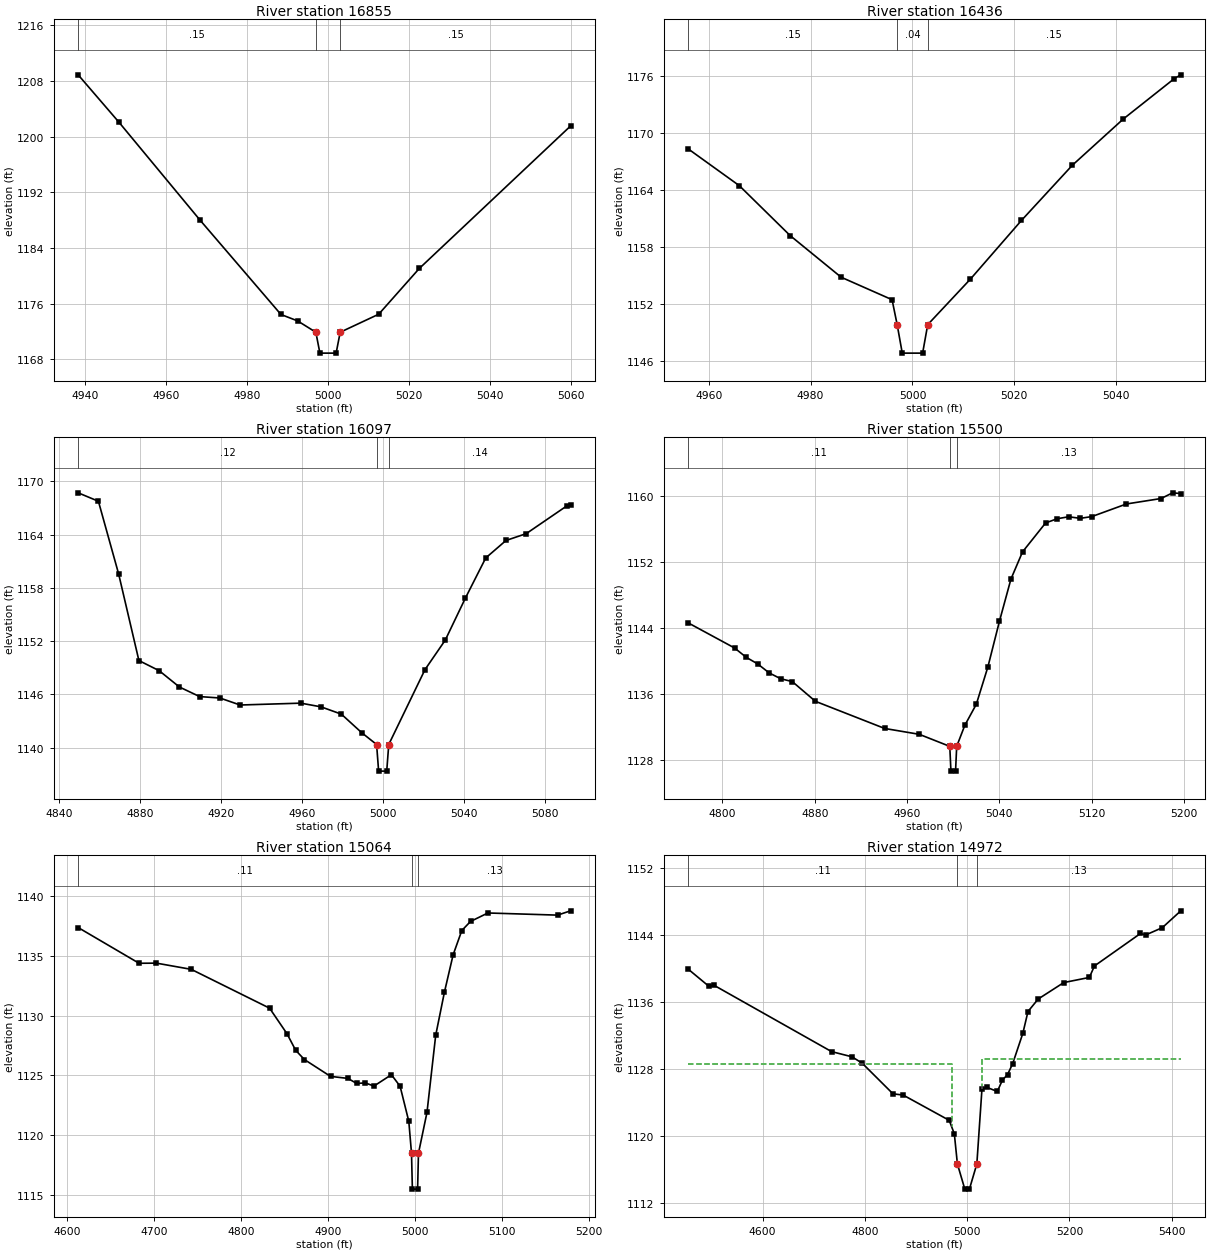
Type RM Length L Ch R = 1,16855,419,419,419
BEGIN DESCRIPTION:
Greasy Creek 34.0
END DESCRIPTION:
XS GIS Cut Line= 3
      1364390.41       805400.96      1364353.29       805440.27
      1364313.94       805494.91
#Sta/Elev= 12
  4938.4 1208.86  4948.4 1202.09  4968.4 1188.02  4988.4 1174.43  4992.5 1173.51
  4997.0 1171.88  4998.0 1168.88  5002.0 1168.88  5003.0 1171.88  5012.5 1174.47
  5022.5 1181.04  5059.8 1201.51
#Mann=3,-1,0
  4938.4    0.15       0  4997.0    0.04       0  5003.0    0.15       0
Bank Sta=4997,5003
XS Rating Curve= 0
Exp/Cntr=0.3,0.1

Type RM Length L Ch R = 1,16436,339,339,339
BEGIN DESCRIPTION:
Greasy Creek 33.0
END DESCRIPTION:
XS GIS Cut Line= 3
      1364128.17       805134.33      1364101.96       805171.45
      1364069.15       805210.83
#Sta/Elev= 15
  4956.0 1168.31  4966.0 1164.45  4976.0 1159.18  4986.0 1154.80  4996.0 1152.43
  4997.0 1149.80  4998.0 1146.80  5002.0 1146.80  5003.0 1149.80  5011.4 1154.61
  5021.4 1160.78  5031.4 1166.60  5041.4 1171.47  5051.4 1175.72  5052.7 1176.13
#Mann=3,-1,0
  4956.0    0.15       0  4997.0    0.04       0  5003.0    0.15       0
Bank Sta=4997,5003
XS Rating Curve= 0
Exp/Cntr=0.3,0.1

Type RM Length L Ch R = 1,16097,597,597,597
BEGIN DESCRIPTION:
Greasy Creek 32.0
END DESCRIPTION:
XS GIS Cut Line= 3
      1363833.14       804876.45      1363820.03       805027.21
      1363815.66       805118.98
#Sta/Elev= 25
  4849.6 1168.70  4859.6 1167.75  4869.6 1159.55  4879.6 1149.80  4889.6 1148.66
  4899.6 1146.82  4909.6 1145.74  4919.6 1145.58  4929.6 1144.79  4959.6 1145.00
  4969.6 1144.58  4979.6 1143.76  4989.6 1141.68  4997.0 1140.34  4998.0 1137.34
  5002.0 1137.34  5003.0 1140.34  5020.9 1148.78  5030.9 1152.10  5040.9 1156.86
  5050.9 1161.36  5060.9 1163.33  5070.9 1164.10  5090.9 1167.22  5092.8 1167.33
#Mann=3,-1,0
  4849.6    0.12       0  4997.0    0.04       0  5003.0    0.14       0
Bank Sta=4997,5003
XS Rating Curve= 0
Exp/Cntr=0.3,0.1

Type RM Length L Ch R = 1,15500,436,436,436
BEGIN DESCRIPTION:
Greasy Creek 31.0
END DESCRIPTION:
XS GIS Cut Line= 3
      1363475.00       804675.00      1363297.97       804820.91
      1363175.03       804974.96
#Sta/Elev= 29
  4770.6 1144.65  4810.6 1141.62  4820.6 1140.50  4830.6 1139.69  4840.6 1138.60
  4850.6 1137.89  4860.6 1137.55  4880.6 1135.16  4940.6 1131.87  4970.6 1131.16
  4997.0 1129.70  4998.0 1126.70  5002.0 1126.70  5003.0 1129.70  5010.0 1132.24
  5020.0 1134.81  5030.0 1139.32  5040.0 1144.85  5050.0 1149.98  5060.0 1153.26
  5080.0 1156.77  5090.0 1157.28  5100.0 1157.52  5110.0 1157.33  5120.0 1157.54
  5150.0 1159.07  5180.0 1159.73  5190.0 1160.42  5197.1 1160.33
#Mann=3,-1,0
  4770.6    0.11       0  4997.0    0.04       0  5003.0    0.13       0
Bank Sta=4997,5003
XS Rating Curve= 0
Exp/Cntr=0.3,0.1

Type RM Length L Ch R = 1,15064,92,92,92
BEGIN DESCRIPTION:
Greasy Creek 30.0
END DESCRIPTION:
XS GIS Cut Line= 3
      1363435.30       804464.35      1363044.83       804482.95
      1362874.97       804525.01
#Sta/Elev= 29
  4612.9 1137.38  4682.9 1134.39  4702.9 1134.40  4742.9 1133.88  4832.9 1130.63
  4852.9 1128.49  4862.9 1127.10  4872.9 1126.33  4902.9 1124.92  4922.9 1124.75
  4932.9 1124.33  4942.9 1124.37  4952.9 1124.11  4972.9 1125.06  4982.9 1124.09
  4992.9 1121.15  4996.0 1118.48  4997.0 1115.48  5003.0 1115.48  5004.0 1118.48
  5013.8 1121.91  5023.8 1128.36  5033.8 1131.96  5043.8 1135.09  5053.8 1137.13
  5063.8 1137.89  5083.8 1138.60  5163.8 1138.42  5178.8 1138.78
#Mann=3,-1,0
  4612.9    0.11       0  4996.0    0.04       0  5004.0    0.13       0
Bank Sta=4996,5004
XS Rating Curve= 0
Exp/Cntr=0.5,0.3

Type RM Length L Ch R = 1,14972,100,100,100
BEGIN DESCRIPTION:
Carson Chapel Rd [Greasy-1] US
END DESCRIPTION:
XS GIS Cut Line= 4
      1363546.96       804399.26      1363002.99       804403.91
      1362640.36       804408.56      1362589.24       804431.80
#Sta/Elev= 30
  4455.0 1139.90  4495.0 1137.88  4505.0 1138.00  4735.0 1130.09  4775.0 1129.47
  4795.0 1128.70  4855.0 1125.06  4875.0 1124.91  4965.0 1121.90  4975.0 1120.29
  4981.0 1116.70  4995.5 1113.70  5004.5 1113.70  5019.0 1116.70  5029.0 1125.62
  5039.0 1125.82  5059.0 1125.34  5069.0 1126.69  5079.0 1127.35  5089.0 1128.64
  5109.0 1132.28  5119.0 1134.87  5139.0 1136.36  5189.0 1138.32  5239.0 1138.93
  5249.0 1140.30  5339.0 1144.17  5349.0 1143.99  5381.6 1144.86  5417.8 1146.87
#Mann=3,-1,0
  4455.0    0.11       0  4981.0    0.04       0  5019.0    0.13       0
#XS Ineff=2,0
    0.00 4970.00 1128.60 5030.00    0.00 1129.20
Permanent Ineff=
       F       F
Bank Sta=4981,5019
XS Rating Curve= 0
Exp/Cntr=0.5,0.3

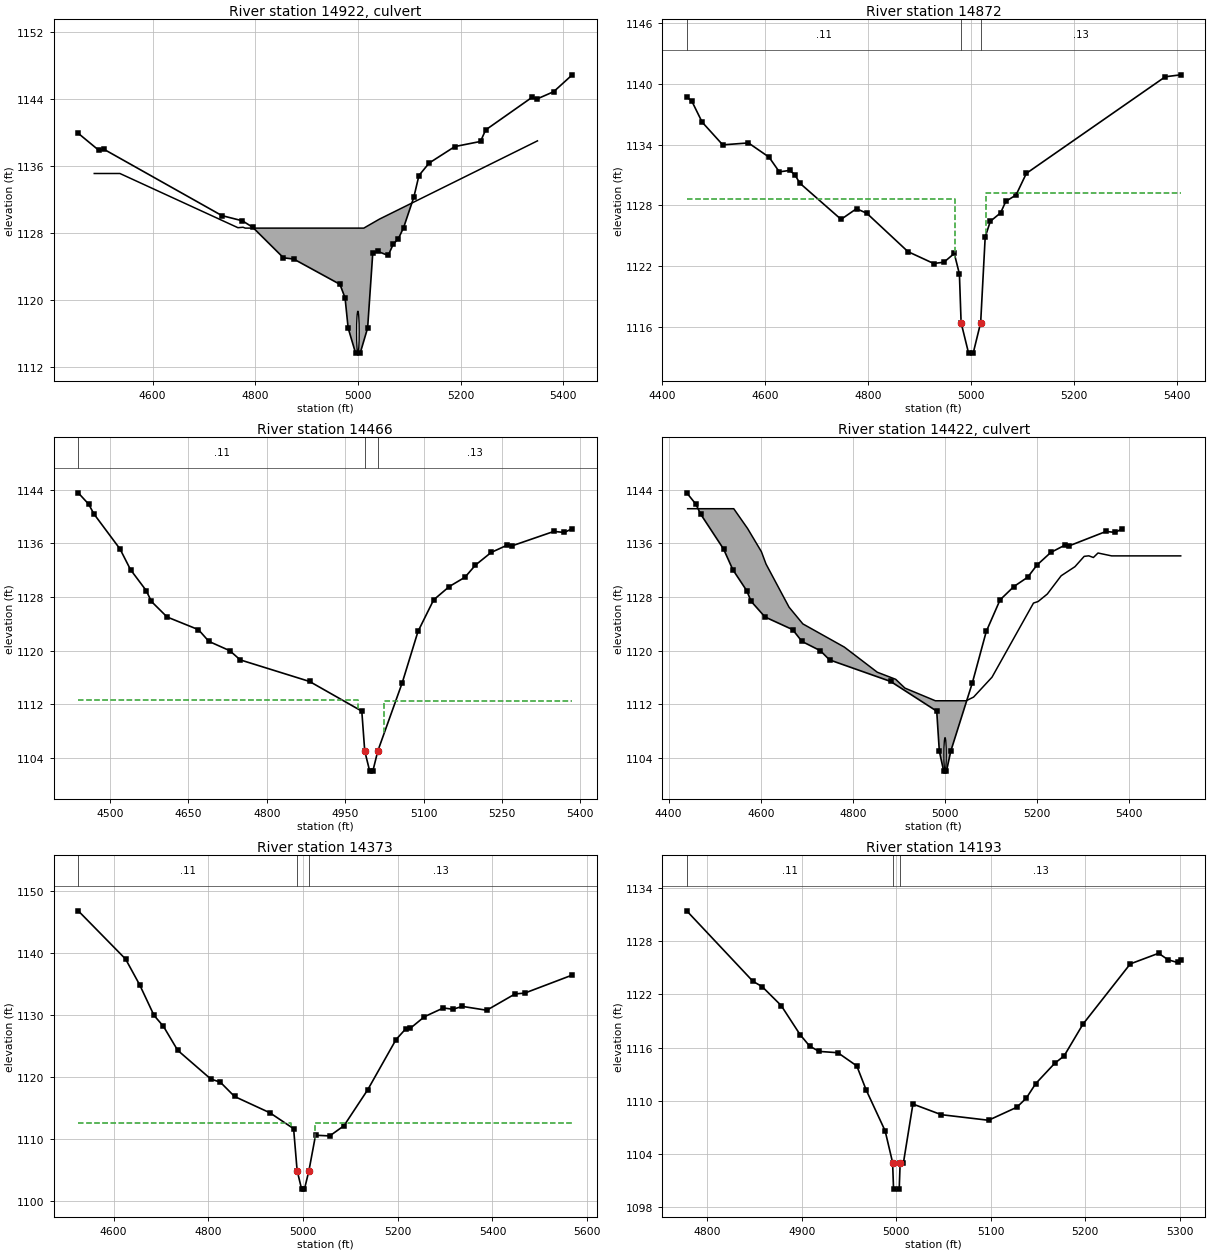
Type RM Length L Ch R =2,14922,,,
BEGIN DESCRIPTION:
Carson Chapel Rd [Greasy-1] TOR
Structure ID: LDS_GC_04
Approximate Survey Structure
END DESCRIPTION:
Bridge Culvert--1,0,-1,-1,0
Deck Dist Width WeirC Skew NumUp NumDn MinLoCord MaxHiCord MaxSubmerge Is_Ogee
25,50,3,,8,8,,,,0,1,1,,,
  4486.2  4536.2  4766.2  4776.2  4780.5  5011.5  5041.9  5350.0
 1135.11 1135.11 1128.65 1128.70 1128.60 1128.60 1129.67 1139.00
 1093.70 1093.70 1093.70 1093.70 1093.70 1093.70 1093.70 1093.70
  4486.2  4536.2  4766.2  4776.2  4780.5  5011.5  5041.9  5350.0
 1135.11 1135.11 1128.65 1128.70 1128.60 1128.60 1129.67 1139.00
 1093.45 1093.45 1093.45 1093.45 1093.45 1093.45 1093.45 1093.45
Culvert=1,5,,50,0.024,0.5,1,2,1,1113.7,5000,1113.45,5000,Culvert #1,0,25
Culvert Bottom n=0.024
Culvert Bottom Depth=0
Culvert Depth Blocked=0
BC Design=,,0,,0,,,,,,

Type RM Length L Ch R = 1,14872,406,406,406
BEGIN DESCRIPTION:
Carson Chapel Rd [Greasy-1] DS
END DESCRIPTION:
XS GIS Cut Line= 3
      1363557.90       804294.88      1363008.12       804312.48
      1362598.09       804315.11
#Sta/Elev= 30
  4447.7 1138.70  4457.7 1138.27  4477.7 1136.21  4517.7 1133.97  4567.7 1134.16
  4607.7 1132.76  4627.7 1131.31  4647.7 1131.45  4657.7 1131.04  4667.7 1130.19
  4747.7 1126.63  4777.7 1127.68  4797.7 1127.23  4877.7 1123.45  4927.7 1122.28
  4947.7 1122.41  4967.7 1123.27  4977.7 1121.25  4981.0 1116.45  4995.5 1113.45
  5004.5 1113.45  5019.0 1116.45  5027.8 1124.89  5037.8 1126.44  5057.8 1127.27
  5067.8 1128.40  5087.8 1129.03  5107.8 1131.16  5377.8 1140.68  5407.8 1140.87
#Mann=3,-1,0
  4447.7    0.11       0  4981.0    0.04       0  5019.0    0.13       0
#XS Ineff=2,0
    0.00 4970.00 1128.60 5030.00    0.00 1129.20
Permanent Ineff=
       F       F
Bank Sta=4981,5019
XS Rating Curve= 0
Exp/Cntr=0.5,0.3

Type RM Length L Ch R = 1,14466,93,93,93
BEGIN DESCRIPTION:
Unnnamed Rd [Greasy-1] US
END DESCRIPTION:
XS GIS Cut Line= 4
      1363481.86       804101.72      1363119.21       804101.72
      1362997.85       803945.94      1362660.66       803759.75
#Sta/Elev= 30
  4439.3 1143.53  4459.3 1141.83  4469.3 1140.38  4519.3 1135.14  4539.3 1132.07
  4569.3 1128.95  4579.3 1127.32  4609.3 1125.00  4669.3 1123.11  4689.3 1121.36
  4729.3 1119.97  4749.3 1118.60  4881.9 1115.38  4981.9 1110.95  4987.5 1105.00
  4997.0 1102.00  5003.0 1102.00  5012.5 1105.00  5059.4 1115.22  5089.4 1122.84
  5119.4 1127.56  5149.4 1129.55  5179.4 1130.94  5199.4 1132.75  5229.4 1134.63
  5259.4 1135.70  5269.4 1135.62  5349.4 1137.77  5369.4 1137.62  5384.6 1138.18
#Mann=3,-1,0
  4439.3    0.11       0  4987.5    0.04       0  5012.5    0.13       0
#XS Ineff=2,0
    0.00 4975.00 1112.60 5025.00    0.00 1112.50
Permanent Ineff=
       F       F
Bank Sta=4987.5,5012.5
XS Rating Curve= 0
Exp/Cntr=0.5,0.3

Type RM Length L Ch R =2,14422,,,
BEGIN DESCRIPTION:
Unnnamed Rd [Greasy-1] TOR
Structure ID: LDS_GC_03
Approximate Survey Structure
END DESCRIPTION:
Bridge Culvert--1,0,-1,-1,0
Deck Dist Width WeirC Skew NumUp NumDn MinLoCord MaxHiCord MaxSubmerge Is_Ogee
34,20,3,,29,29,,,,0,1,1,,,
  4441.4  4491.4  4541.4  4571.4  4601.4  4611.4  4661.4  4691.4  4781.4  4852.9
  4892.9  4912.9  4978.9  5045.7  5061.9  5101.9  5191.9  5201.9  5221.9  5251.9
  5281.9  5301.9  5311.9  5321.9  5331.9  5361.4  5411.4  5461.4  5511.4
 1141.16 1141.16 1141.16 1138.21 1134.75 1132.91 1126.47 1123.97 1120.51 1116.76
 1115.70 1114.39 1112.50 1112.50 1113.05 1116.02 1127.08 1127.31 1128.43 1131.15
 1132.51 1134.05 1134.13 1133.88 1134.55 1134.12 1134.12 1134.12 1134.12
 1082.00 1082.00 1082.00 1082.00 1082.00 1082.00 1082.00 1082.00 1082.00 1082.00
 1082.00 1082.00 1082.00 1082.00 1082.00 1082.00 1082.00 1082.00 1082.00 1082.00
 1082.00 1082.00 1082.00 1082.00 1082.00 1082.00 1082.00 1082.00 1082.00
  4441.4  4491.4  4541.4  4571.4  4601.4  4611.4  4661.4  4691.4  4781.4  4852.9
  4892.9  4912.9  4978.9  5045.7  5061.9  5101.9  5191.9  5201.9  5221.9  5251.9
  5281.9  5301.9  5311.9  5321.9  5331.9  5361.4  5411.4  5461.4  5511.4
 1141.16 1141.16 1141.16 1138.21 1134.75 1132.91 1126.47 1123.97 1120.51 1116.76
 1115.70 1114.39 1112.50 1112.50 1113.05 1116.02 1127.08 1127.31 1128.43 1131.15
 1132.51 1134.05 1134.13 1133.88 1134.55 1134.12 1134.12 1134.12 1134.12
 1081.90 1081.90 1081.90 1081.90 1081.90 1081.90 1081.90 1081.90 1081.90 1081.90
 1081.90 1081.90 1081.90 1081.90 1081.90 1081.90 1081.90 1081.90 1081.90 1081.90
 1081.90 1081.90 1081.90 1081.90 1081.90 1081.90 1081.90 1081.90 1081.90
Culvert=1,5,,20,0.024,0.9,1,2,3,1102,5000,1101.9,5000,Culvert #1,0,34
Culvert Bottom n=0.024
Culvert Bottom Depth=0
Culvert Depth Blocked=0
BC Design=,,0,,0,,,,,,

Type RM Length L Ch R = 1,14373,180,180,180
BEGIN DESCRIPTION:
Unnnamed Rd [Greasy-1] DS
END DESCRIPTION:
XS GIS Cut Line= 5
      1363513.91       803992.86      1363159.13       803991.39
      1363081.42       803904.89      1362775.00       803677.63
      1362584.54       803669.36
#Sta/Elev= 30
  4525.3 1146.83  4625.3 1139.04  4655.3 1134.84  4685.3 1129.95  4705.3 1128.17
  4735.3 1124.31  4805.3 1119.67  4825.3 1119.17  4855.3 1116.86  4930.1 1114.22
  4980.1 1111.66  4987.5 1104.90  4997.0 1101.90  5003.0 1101.90  5012.5 1104.90
  5026.4 1110.60  5056.4 1110.49  5086.4 1112.13  5136.4 1117.92  5196.4 1126.05
  5216.4 1127.74  5226.4 1127.86  5256.4 1129.74  5296.4 1131.15  5316.4 1130.94
  5336.4 1131.40  5387.9 1130.78  5447.9 1133.42  5467.9 1133.54  5568.5 1136.46
#Mann=3,-1,0
  4525.3    0.11       0  4987.5    0.04       0  5012.5    0.13       0
#XS Ineff=2,0
    0.00 4975.00 1112.60 5025.00    0.00 1112.50
Permanent Ineff=
       F       F
Bank Sta=4987.5,5012.5
XS Rating Curve= 0
Exp/Cntr=0.5,0.3

Type RM Length L Ch R = 1,14193,928,928,928
BEGIN DESCRIPTION:
Greasy Creek 28.0
END DESCRIPTION:
XS GIS Cut Line= 3
      1363412.28       803855.96      1363196.18       803779.12
      1362922.41       803673.46
#Sta/Elev= 30
  4778.1 1131.43  4848.1 1123.49  4858.1 1122.86  4878.1 1120.74  4898.1 1117.46
  4908.1 1116.18  4918.1 1115.57  4938.1 1115.42  4958.1 1113.93  4968.1 1111.20
  4988.1 1106.60  4996.0 1103.03  4997.0 1100.03  5003.0 1100.03  5004.0 1103.03
  5007.5 1103.03  5017.5 1109.63  5047.5 1108.43  5097.5 1107.80  5127.5 1109.27
  5137.5 1110.30  5147.5 1111.94  5167.5 1114.22  5177.5 1115.06  5197.5 1118.65
  5247.5 1125.44  5277.5 1126.64  5287.5 1125.91  5297.5 1125.60  5300.9 1125.83
#Mann=3,-1,0
  4778.1    0.11       0  4996.0    0.04       0  5004.0    0.13       0
Bank Sta=4996,5004
XS Rating Curve= 0
Exp/Cntr=0.3,0.1

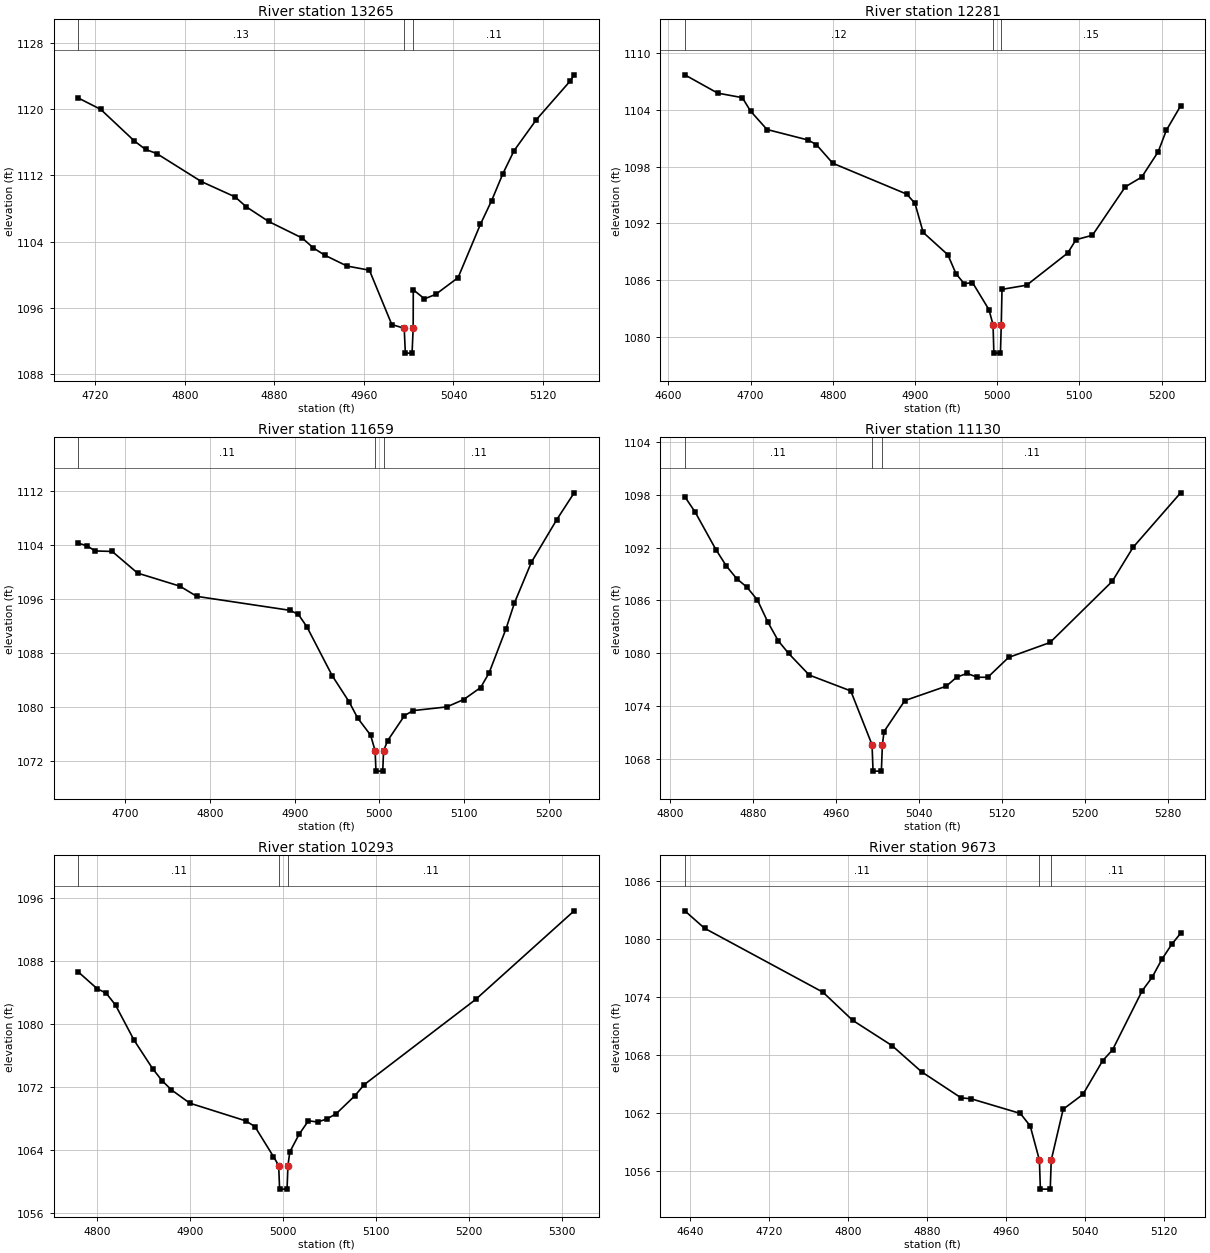
Type RM Length L Ch R = 1,13265,984,984,984
BEGIN DESCRIPTION:
Greasy Creek 27.0
END DESCRIPTION:
XS GIS Cut Line= 3
      1363863.78       803683.05      1363839.77       803394.89
      1363834.96       803241.22
#Sta/Elev= 30
  4704.9 1121.35  4724.9 1119.98  4754.9 1116.17  4764.9 1115.15  4774.9 1114.65
  4814.9 1111.26  4844.9 1109.42  4854.9 1108.22  4874.9 1106.45  4904.9 1104.45
  4914.9 1103.25  4924.9 1102.39  4944.9 1101.07  4964.9 1100.57  4984.9 1094.01
  4996.0 1093.56  4997.0 1090.56  5003.0 1090.56  5004.0 1093.56  5004.1 1098.21
  5014.1 1097.11  5024.1 1097.65  5044.1 1099.67  5064.1 1106.12  5074.1 1108.97
  5084.1 1112.21  5094.1 1114.99  5114.1 1118.75  5144.1 1123.38  5147.8 1124.15
#Mann=3,-1,0
  4704.9    0.13       0  4996.0    0.04       0  5004.0    0.11       0
Bank Sta=4996,5004
XS Rating Curve= 0
Exp/Cntr=0.3,0.1

Type RM Length L Ch R = 1,12281,622,622,622
BEGIN DESCRIPTION:
Greasy Creek 25.0
END DESCRIPTION:
XS GIS Cut Line= 3
      1364722.63       803521.39      1364718.26       803145.52
      1364718.26       802918.22
#Sta/Elev= 30
  4620.0 1107.68  4660.0 1105.75  4690.0 1105.27  4700.0 1103.85  4720.0 1101.91
  4770.0 1100.80  4780.0 1100.32  4800.0 1098.35  4890.0 1095.09  4900.0 1094.12
  4910.0 1091.05  4940.0 1088.69  4950.0 1086.68  4960.0 1085.63  4970.0 1085.76
  4990.0 1082.90  4995.0 1081.31  4996.0 1078.31  5004.0 1078.31  5005.0 1081.31
  5005.9 1085.04  5035.9 1085.48  5085.9 1088.88  5095.9 1090.28  5115.9 1090.75
  5155.9 1095.86  5175.9 1096.89  5195.9 1099.56  5205.9 1101.84  5223.2 1104.40
#Mann=3,-1,0
  4620.0    0.12       0  4995.0    0.04       0  5005.0    0.15       0
Bank Sta=4995,5005
XS Rating Curve= 0
Exp/Cntr=0.3,0.1

Type RM Length L Ch R = 1,11659,529,529,529
BEGIN DESCRIPTION:
Greasy Creek 23.0
END DESCRIPTION:
XS GIS Cut Line= 3
      1365299.60       803521.42      1365308.34       803176.12
      1365312.71       802935.67
#Sta/Elev= 30
  4644.3 1104.25  4654.3 1103.87  4664.3 1103.10  4684.3 1103.03  4714.3 1099.83
  4764.3 1097.90  4784.3 1096.39  4894.3 1094.33  4904.3 1093.73  4914.3 1091.91
  4944.3 1084.67  4964.3 1080.80  4974.3 1078.43  4989.7 1075.88  4995.0 1073.57
  4996.0 1070.57  5004.0 1070.57  5005.0 1073.57  5009.7 1075.05  5029.7 1078.77
  5039.7 1079.51  5079.7 1080.06  5099.7 1081.15  5119.7 1082.92  5129.7 1085.09
  5149.7 1091.61  5159.7 1095.44  5179.7 1101.44  5209.7 1107.74  5230.2 1111.69
#Mann=3,-1,0
  4644.3    0.11       0  4995.0    0.04       0  5005.0    0.11       0
Bank Sta=4995,5005
XS Rating Curve= 0
Exp/Cntr=0.3,0.1

Type RM Length L Ch R = 1,11130,837,837,837
BEGIN DESCRIPTION:
Greasy Creek 22.0
END DESCRIPTION:
XS GIS Cut Line= 3
      1365889.66       803241.67      1365797.88       803084.33
      1365631.76       802839.52
#Sta/Elev= 28
  4814.5 1097.77  4824.5 1096.02  4844.5 1091.76  4854.5 1089.91  4864.5 1088.47
  4874.5 1087.48  4884.5 1086.04  4894.5 1083.54  4904.5 1081.42  4914.5 1079.98
  4934.5 1077.51  4974.5 1075.71  4995.0 1069.60  4996.0 1066.60  5004.0 1066.60
  5005.0 1069.60  5006.6 1071.10  5026.6 1074.61  5066.6 1076.25  5076.6 1077.27
  5086.6 1077.70  5096.6 1077.26  5106.6 1077.26  5126.6 1079.51  5166.6 1081.21
  5226.6 1088.16  5246.6 1092.01  5292.5 1098.21
#Mann=3,-1,0
  4814.5    0.11       0  4995.0    0.04       0  5005.0    0.11       0
Bank Sta=4995,5005
XS Rating Curve= 0
Exp/Cntr=0.3,0.1

Type RM Length L Ch R = 1,10293,620,620,620
BEGIN DESCRIPTION:
Greasy Creek 21.0
END DESCRIPTION:
XS GIS Cut Line= 3
      1366296.17       803272.24      1366309.28       803044.99
      1366313.65       802739.05
#Sta/Elev= 26
  4779.4 1086.62  4799.4 1084.52  4809.4 1083.92  4819.4 1082.42  4839.4 1077.95
  4859.4 1074.33  4869.4 1072.83  4879.4 1071.66  4899.4 1069.95  4959.4 1067.71
  4969.4 1066.98  4989.4 1063.16  4995.0 1062.03  4996.0 1059.03  5004.0 1059.03
  5005.0 1062.03  5007.0 1063.76  5017.0 1066.00  5027.0 1067.71  5037.0 1067.56
  5047.0 1067.95  5057.0 1068.62  5077.0 1070.89  5087.0 1072.30  5207.0 1083.13
  5313.0 1094.39
#Mann=3,-1,0
  4779.4    0.11       0  4995.0   0.045       0  5005.0    0.11       0
Bank Sta=4995,5005
XS Rating Curve= 0
Exp/Cntr=0.3,0.1

Type RM Length L Ch R = 1,9673,479,479,479
BEGIN DESCRIPTION:
Greasy Creek 19.0
END DESCRIPTION:
XS GIS Cut Line= 3
      1366964.91       803010.01      1366734.24       802703.75
      1366662.13       802609.10
#Sta/Elev= 23
  4634.7 1082.93  4654.7 1081.13  4774.7 1074.52  4804.7 1071.62  4844.7 1069.00
  4874.7 1066.29  4914.7 1063.60  4924.7 1063.51  4974.7 1061.99  4984.7 1060.70
  4994.0 1057.17  4995.0 1054.17  5005.0 1054.17  5006.0 1057.17  5018.1 1062.43
  5038.1 1063.96  5058.1 1067.44  5068.1 1068.56  5098.1 1074.66  5108.1 1076.04
  5118.1 1077.92  5128.1 1079.47  5137.1 1080.61
#Mann=3,-1,0
  4634.7    0.11       0  4994.0   0.045       0  5006.0    0.11       0
Bank Sta=4994,5006
XS Rating Curve= 0
Exp/Cntr=0.3,0.1

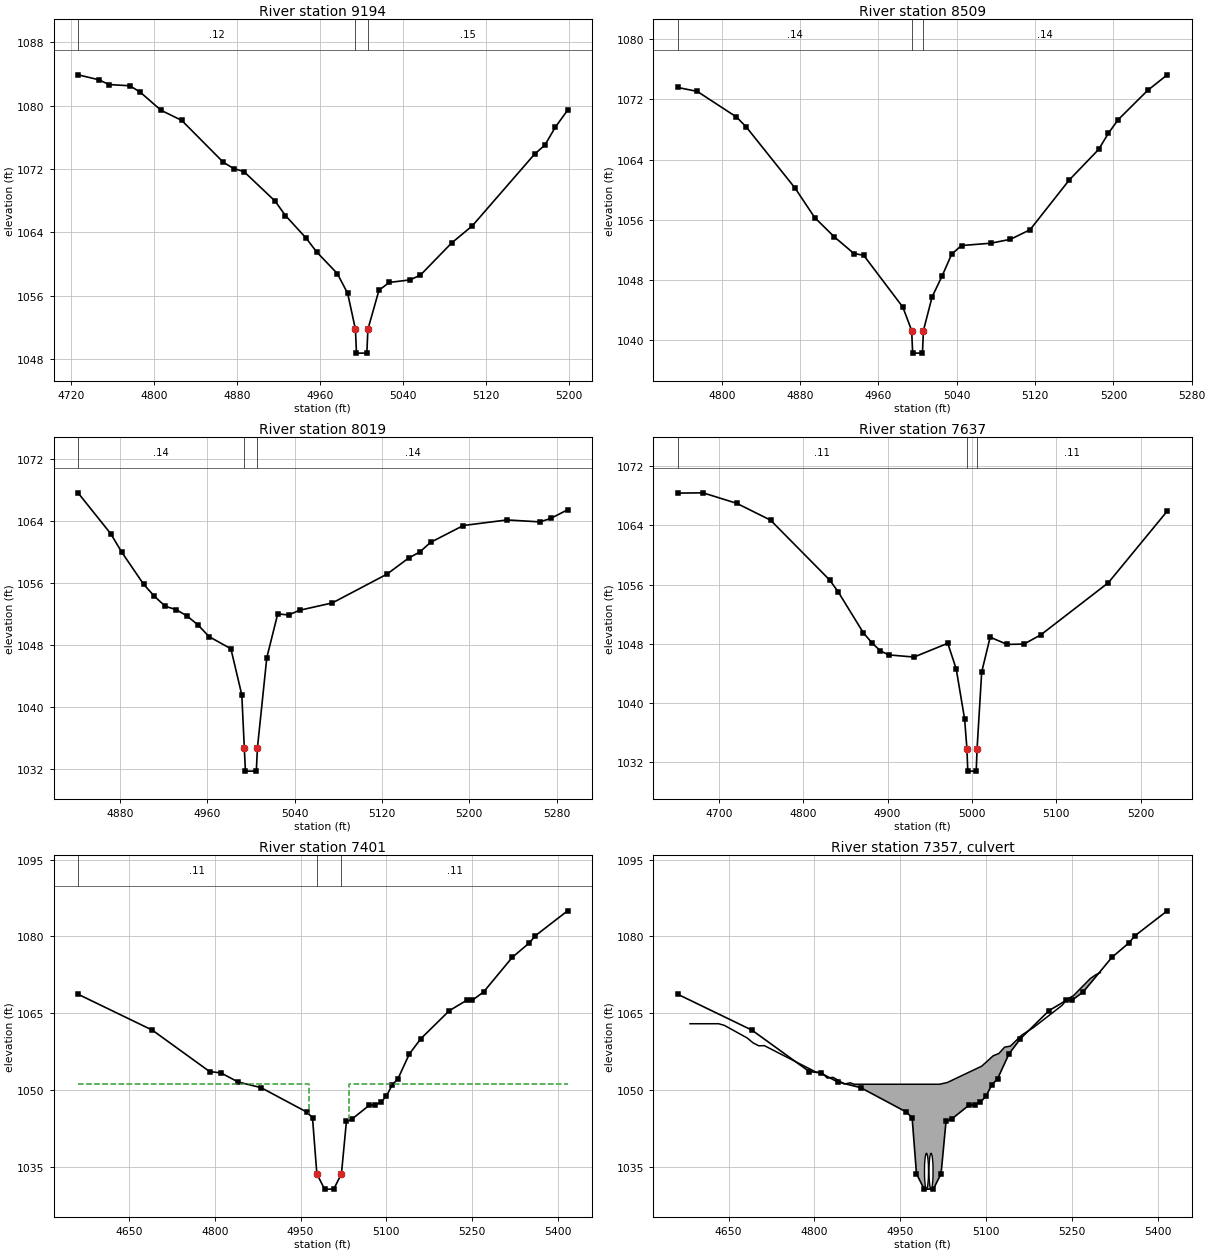
Type RM Length L Ch R = 1,9194,685,685,685
BEGIN DESCRIPTION:
Greasy Creek 18.0
END DESCRIPTION:
XS GIS Cut Line= 3
      1367257.15       802789.40      1367130.93       802550.49
      1367031.74       802374.64
#Sta/Elev= 30
  4726.5 1083.87  4746.5 1083.25  4756.5 1082.64  4776.5 1082.49  4786.5 1081.68
  4806.5 1079.40  4826.5 1078.12  4866.5 1072.85  4876.5 1072.05  4886.5 1071.66
  4916.5 1067.94  4926.5 1066.12  4946.5 1063.26  4956.5 1061.54  4976.5 1058.80
  4986.5 1056.30  4994.0 1051.76  4995.0 1048.76  5005.0 1048.76  5006.0 1051.76
  5016.7 1056.70  5026.7 1057.68  5046.7 1058.00  5056.7 1058.61  5086.7 1062.65
  5106.7 1064.82  5166.7 1073.86  5176.7 1075.01  5186.7 1077.26  5198.6 1079.41
#Mann=3,-1,0
  4726.5    0.12       0  4994.0   0.045       0  5006.0    0.15       0
Bank Sta=4994,5006
XS Rating Curve= 0
Exp/Cntr=0.3,0.1

Type RM Length L Ch R = 1,8509,490,490,490
BEGIN DESCRIPTION:
Greasy Creek 17.0
END DESCRIPTION:
XS GIS Cut Line= 3
      1367742.94       802634.10      1367622.29       802415.25
      1367505.06       802194.33
#Sta/Elev= 27
  4755.0 1073.58  4775.0 1073.06  4815.0 1069.66  4825.0 1068.34  4875.0 1060.19
  4895.0 1056.28  4915.0 1053.72  4935.0 1051.51  4945.0 1051.27  4985.0 1044.38
  4994.0 1041.27  4995.0 1038.27  5005.0 1038.27  5006.0 1041.27  5014.9 1045.76
  5024.9 1048.47  5034.9 1051.44  5044.9 1052.57  5074.9 1052.88  5094.9 1053.40
  5114.9 1054.67  5154.9 1061.28  5184.9 1065.34  5194.9 1067.49  5204.9 1069.30
  5234.9 1073.18  5255.0 1075.26
#Mann=3,-1,0
  4755.0    0.14       0  4994.0   0.045       0  5006.0    0.14       0
Bank Sta=4994,5006
XS Rating Curve= 0
Exp/Cntr=0.3,0.1

Type RM Length L Ch R = 1,8019,382,382,382
BEGIN DESCRIPTION:
Greasy Creek 16.0
END DESCRIPTION:
XS GIS Cut Line= 3
      1368131.68       802564.00      1368091.11       802406.24
      1368014.46       802131.22
#Sta/Elev= 30
  4841.7 1067.68  4871.7 1062.38  4881.7 1060.01  4901.7 1055.86  4911.7 1054.28
  4921.7 1052.99  4931.7 1052.56  4941.7 1051.72  4951.7 1050.57  4961.7 1049.07
  4981.7 1047.50  4991.7 1041.52  4994.0 1034.66  4995.0 1031.66  5005.0 1031.66
  5006.0 1034.66  5014.6 1046.35  5024.6 1052.01  5034.6 1051.87  5044.6 1052.48
  5074.6 1053.43  5124.6 1057.15  5144.6 1059.25  5154.6 1060.01  5164.6 1061.27
  5194.6 1063.45  5234.6 1064.17  5264.6 1063.92  5274.6 1064.36  5290.1 1065.49
#Mann=3,-1,0
  4841.7    0.14       0  4994.0   0.045       0  5006.0    0.14       0
Bank Sta=4994,5006
XS Rating Curve= 0
Exp/Cntr=0.3,0.1

Type RM Length L Ch R = 1,7637,236,236,236
BEGIN DESCRIPTION:
Greasy Creek 15.0
END DESCRIPTION:
XS GIS Cut Line= 3
      1368512.21       802367.47      1368271.42       802113.23
      1368118.18       801941.95
#Sta/Elev= 25
  4651.3 1068.37  4681.3 1068.41  4721.3 1066.99  4761.3 1064.72  4831.3 1056.63
  4841.3 1055.05  4871.3 1049.48  4881.3 1048.14  4891.3 1047.05  4901.3 1046.49
  4931.3 1046.20  4971.3 1048.06  4981.3 1044.59  4991.3 1037.78  4994.0 1033.77
  4995.0 1030.77  5005.0 1030.77  5006.0 1033.77  5011.5 1044.18  5021.5 1048.89
  5041.5 1047.91  5061.5 1047.95  5081.5 1049.20  5161.5 1056.25  5231.3 1065.94
#Mann=3,-1,0
  4651.3    0.11       0  4994.0   0.045       0  5006.0    0.11       0
Bank Sta=4994,5006
XS Rating Curve= 0
Exp/Cntr=0.5,0.3

Type RM Length L Ch R = 1,7401,91,91,91
BEGIN DESCRIPTION:
Rocky Springs Rd [Greasy-1] US
END DESCRIPTION:
XS GIS Cut Line= 3
      1368771.55       802286.34      1368455.45       801981.31
      1368156.78       801690.55
#Sta/Elev= 30
  4560.9 1068.70  4690.9 1061.67  4790.9 1053.59  4810.9 1053.31  4840.9 1051.54
  4880.9 1050.44  4960.9 1045.66  4970.9 1044.56  4978.5 1033.60  4992.0 1030.60
  5008.0 1030.60  5021.5 1033.60  5030.2 1043.85  5040.2 1044.32  5070.2 1046.99
  5080.2 1047.04  5090.2 1047.60  5100.2 1048.77  5110.2 1050.99  5120.2 1052.15
  5140.2 1057.01  5160.2 1059.99  5210.2 1065.49  5240.2 1067.49  5250.2 1067.50
  5270.2 1069.16  5320.2 1075.90  5350.2 1078.75  5360.2 1080.10  5417.0 1085.00
#Mann=3,-1,0
  4560.9    0.11       0  4978.5   0.045       0  5021.5    0.11       0
#XS Ineff=2,0
    0.00 4965.00 1051.10 5035.00    0.00 1051.16
Permanent Ineff=
       F       F
Bank Sta=4978.5,5021.5
XS Rating Curve= 0
Exp/Cntr=0.5,0.3

Type RM Length L Ch R =2,7357,,,
BEGIN DESCRIPTION:
Rocky Springs Rd [Greasy-1] TOR
Structure ID: LDS_GC_02
Approximate Survey Structure
END DESCRIPTION:
Bridge Culvert--1,0,-1,-1,0
Deck Dist Width WeirC Skew NumUp NumDn MinLoCord MaxHiCord MaxSubmerge Is_Ogee
14,60,3,,29,29,,,0.95,0,1,1,,,
  4582.6  4632.6  4642.6  4682.6  4692.6  4702.6  4712.6  4802.6  4812.6  4822.6
  4832.6  4852.6  4862.6  4869.8  5019.1  5032.6  5092.6  5112.6  5122.6  5132.6
  5142.6  5162.6  5182.6  5232.6  5242.6  5252.6  5282.6  5292.6  5300.1
 1062.93 1062.93 1062.61 1060.14 1059.20 1058.62 1058.64 1053.49 1053.39 1052.30
 1052.45 1051.15 1051.38 1051.10 1051.10 1051.45 1054.64 1056.66 1057.12 1058.35
 1058.55 1060.71 1062.15 1066.48 1067.78 1068.38 1071.78 1072.54 1072.93
 1010.60 1010.60 1010.60 1010.60 1010.60 1010.60 1010.60 1010.60 1010.60 1010.60
 1010.60 1010.60 1010.60 1010.60 1010.60 1010.60 1010.60 1010.60 1010.60 1010.60
 1010.60 1010.60 1010.60 1010.60 1010.60 1010.60 1010.60 1010.60 1010.60
  4582.6  4632.6  4642.6  4682.6  4692.6  4702.6  4712.6  4802.6  4812.6  4822.6
  4832.6  4852.6  4862.6  4869.8  5019.1  5032.6  5092.6  5112.6  5122.6  5132.6
  5142.6  5162.6  5182.6  5232.6  5242.6  5252.6  5282.6  5292.6  5300.1
 1062.93 1062.93 1062.61 1060.14 1059.20 1058.62 1058.64 1053.49 1053.39 1052.30
 1052.45 1051.15 1051.38 1051.10 1051.10 1051.45 1054.64 1056.66 1057.12 1058.35
 1058.55 1060.71 1062.15 1066.48 1067.78 1068.38 1071.78 1072.54 1072.93
 1010.30 1010.30 1010.30 1010.30 1010.30 1010.30 1010.30 1010.30 1010.30 1010.30
 1010.30 1010.30 1010.30 1010.30 1010.30 1010.30 1010.30 1010.30 1010.30 1010.30
 1010.30 1010.30 1010.30 1010.30 1010.30 1010.30 1010.30 1010.30 1010.30
Culvert=1,7,,60,0.024,0.5,1,2,1,1030.6,4996,1030.3,4996,Culvert #1,0,14
Culvert Bottom n=0.024
Culvert Bottom Depth=0
Culvert Depth Blocked=0
Culvert=1,7,,60,0.024,0.5,1,2,1,1030.6,5004,1030.3,5004,Culvert #2,0,14
Culvert Bottom n=0.024
Culvert Bottom Depth=0
Culvert Depth Blocked=0
BC Design=,,0,,0,,,,,,

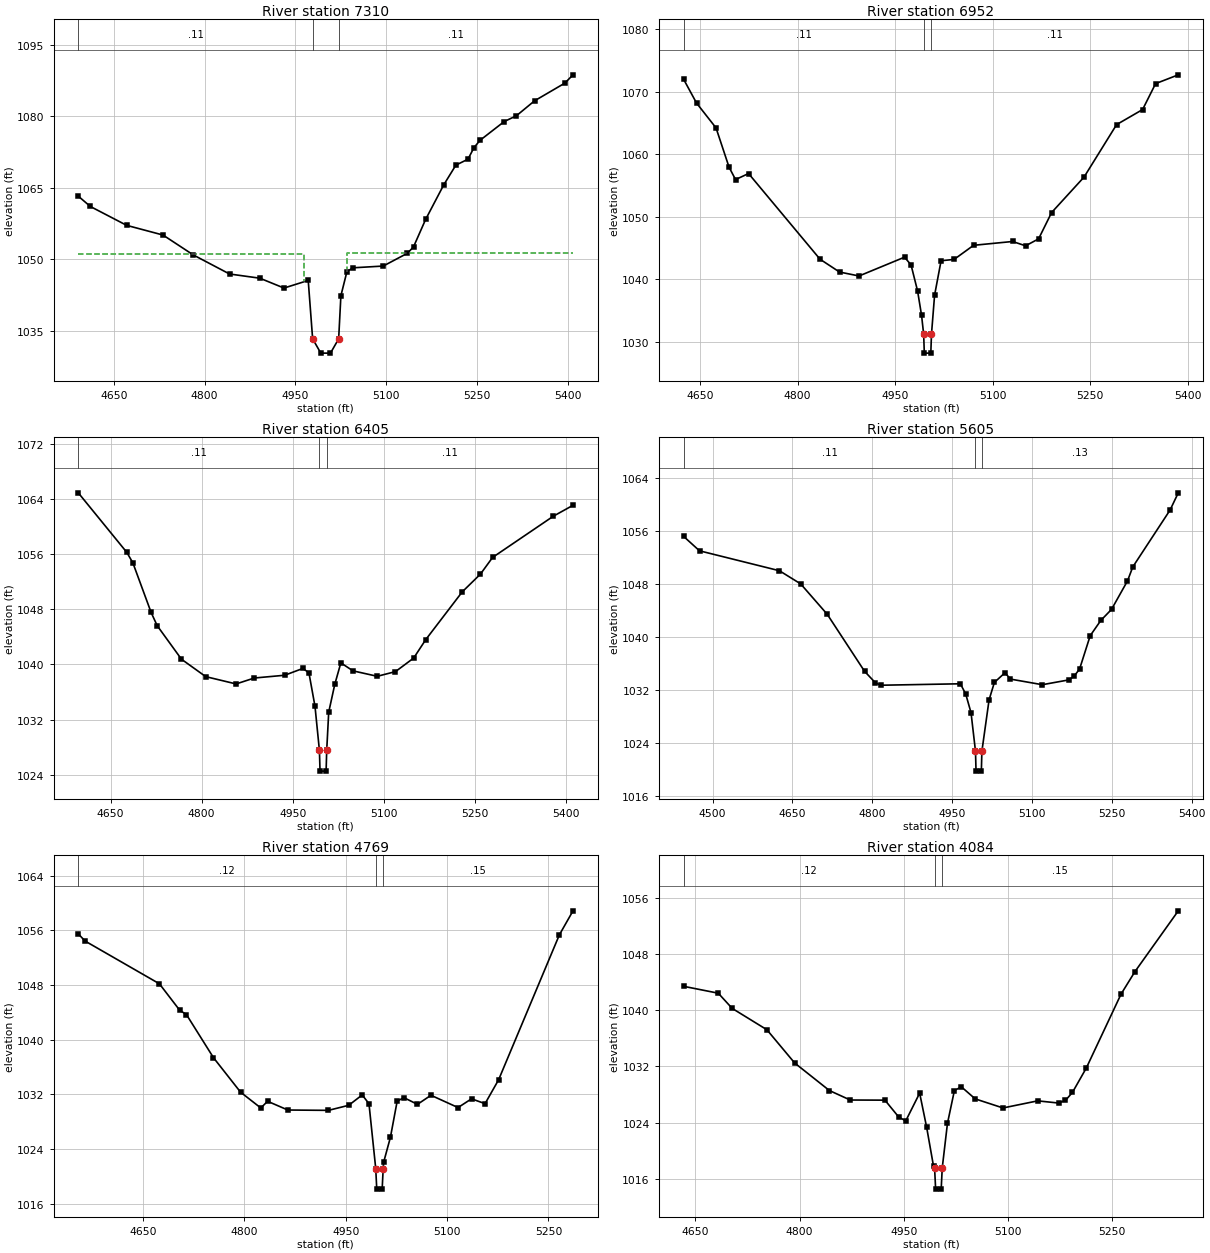
Type RM Length L Ch R = 1,7310,358,358,358
BEGIN DESCRIPTION:
Rocky Springs Rd [Greasy-1] DS
END DESCRIPTION:
XS GIS Cut Line= 3
      1368826.84       802196.25      1368520.24       801918.10
      1368226.27       801641.51
#Sta/Elev= 30
  4591.2 1063.25  4611.2 1061.08  4671.2 1057.12  4731.2 1055.09  4781.2 1050.92
  4841.2 1046.91  4891.2 1046.03  4931.2 1043.96  4971.2 1045.56  4978.5 1033.30
  4992.0 1030.30  5008.0 1030.30  5021.5 1033.30  5025.2 1042.35  5035.2 1047.43
  5045.2 1048.21  5095.2 1048.58  5135.2 1051.27  5145.2 1052.60  5165.2 1058.36
  5195.2 1065.63  5215.2 1069.76  5235.2 1071.01  5245.2 1073.45  5255.2 1074.98
  5295.2 1078.92  5315.2 1080.12  5345.2 1083.26  5395.2 1086.97  5408.8 1088.72
#Mann=3,-1,0
  4591.2    0.11       0  4978.5   0.045       0  5021.5    0.11       0
#XS Ineff=2,0
    0.00 4965.00 1051.10 5035.00    0.00 1051.24
Permanent Ineff=
       F       F
Bank Sta=4978.5,5021.5
XS Rating Curve= 0
Exp/Cntr=0.5,0.3

Type RM Length L Ch R = 1,6952,547,547,547
BEGIN DESCRIPTION:
Greasy Creek 14.0
END DESCRIPTION:
XS GIS Cut Line= 3
      1369042.29       802009.58      1368816.87       801721.04
      1368573.46       801410.02
#Sta/Elev= 30
  4624.6 1072.02  4644.6 1068.19  4674.6 1064.21  4694.6 1057.93  4704.6 1055.94
  4724.6 1056.91  4834.6 1043.19  4864.6 1041.14  4894.6 1040.51  4964.6 1043.52
  4974.6 1042.28  4984.6 1038.13  4990.8 1034.19  4994.0 1031.16  4995.0 1028.16
  5005.0 1028.16  5006.0 1031.16  5010.8 1037.43  5020.8 1042.95  5040.8 1043.16
  5070.8 1045.42  5130.8 1046.03  5150.8 1045.34  5170.8 1046.45  5190.8 1050.66
  5240.8 1056.35  5290.8 1064.74  5330.8 1067.15  5350.8 1071.30  5385.7 1072.71
#Mann=3,-1,0
  4624.6    0.11       0  4994.0   0.045       0  5006.0    0.11       0
Bank Sta=4994,5006
XS Rating Curve= 0
Exp/Cntr=0.3,0.1

Type RM Length L Ch R = 1,6405,800,800,800
BEGIN DESCRIPTION:
Greasy Creek 13.0
END DESCRIPTION:
XS GIS Cut Line= 3
      1369465.99       801716.51      1369240.61       801382.95
      1369010.73       801040.39
#Sta/Elev= 30
  4596.7 1064.92  4676.7 1056.27  4686.7 1054.74  4716.7 1047.55  4726.7 1045.63
  4766.7 1040.76  4806.7 1038.23  4856.7 1037.17  4886.7 1038.03  4936.7 1038.43
  4966.7 1039.42  4976.7 1038.79  4986.7 1033.92  4994.0 1027.51  4995.0 1024.51
  5005.0 1024.51  5006.0 1027.51  5009.3 1033.07  5019.3 1037.11  5029.3 1040.23
  5049.3 1039.07  5089.3 1038.28  5119.3 1038.96  5149.3 1040.93  5169.3 1043.62
  5229.3 1050.54  5259.3 1053.12  5279.3 1055.54  5379.3 1061.52  5411.8 1063.11
#Mann=3,-1,0
  4596.7    0.11       0  4994.0   0.045       0  5006.0    0.11       0
Bank Sta=4994,5006
XS Rating Curve= 0
Exp/Cntr=0.3,0.1

Type RM Length L Ch R = 1,5605,836,836,836
BEGIN DESCRIPTION:
Greasy Creek 12.0
END DESCRIPTION:
XS GIS Cut Line= 3
      1369903.27       801563.25      1369880.73       800999.78
      1369867.20       800634.65
#Sta/Elev= 30
  4445.6 1055.22  4475.6 1053.03  4625.6 1050.02  4665.6 1048.03  4715.6 1043.42
  4785.6 1034.81  4805.6 1033.10  4815.6 1032.70  4965.6 1032.92  4975.6 1031.38
  4985.6 1028.55  4994.0 1022.71  4995.0 1019.71  5005.0 1019.71  5006.0 1022.71
  5019.5 1030.49  5029.5 1033.13  5049.5 1034.60  5059.5 1033.63  5119.5 1032.78
  5169.5 1033.51  5179.5 1034.10  5189.5 1035.15  5209.5 1040.20  5229.5 1042.51
  5249.5 1044.17  5279.5 1048.48  5289.5 1050.60  5359.5 1059.20  5374.9 1061.80
#Mann=3,-1,0
  4445.6    0.11       0  4994.0   0.045       0  5006.0    0.13       0
Bank Sta=4994,5006
XS Rating Curve= 0
Exp/Cntr=0.3,0.1

Type RM Length L Ch R = 1,4769,685,685,685
BEGIN DESCRIPTION:
Greasy Creek 10.0
END DESCRIPTION:
XS GIS Cut Line= 3
      1370381.12       801684.94      1370592.97       801297.30
      1370750.73       801053.90
#Sta/Elev= 30
  4554.5 1055.48  4564.5 1054.43  4674.5 1048.17  4704.5 1044.30  4714.5 1043.66
  4754.5 1037.35  4794.5 1032.31  4824.5 1029.99  4834.5 1030.97  4864.5 1029.69
  4924.5 1029.64  4954.5 1030.38  4974.5 1031.90  4984.5 1030.61  4994.5 1021.11
  4996.0 1018.11  5004.0 1018.11  5005.5 1021.11  5006.2 1022.05  5016.2 1025.69
  5026.2 1030.99  5036.2 1031.50  5056.2 1030.52  5076.2 1031.85  5116.2 1030.05
  5136.2 1031.33  5156.2 1030.62  5176.2 1034.11  5266.2 1055.35  5286.3 1058.85
#Mann=3,-1,0
  4554.5    0.12       0  4994.5    0.05       0  5005.5    0.15       0
Bank Sta=4994.5,5005.5
XS Rating Curve= 0
Exp/Cntr=0.3,0.1

Type RM Length L Ch R = 1,4084,443,443,443
BEGIN DESCRIPTION:
Greasy Creek 8.0
END DESCRIPTION:
XS GIS Cut Line= 3
      1371034.73       801969.00      1371169.97       801635.39
      1371296.18       801306.34
#Sta/Elev= 30
  4633.0 1043.39  4683.0 1042.41  4703.0 1040.25  4753.0 1037.21  4793.0 1032.48
  4843.0 1028.56  4873.0 1027.21  4923.0 1027.19  4943.0 1024.77  4953.0 1024.25
  4973.0 1028.19  4983.0 1023.36  4993.0 1017.77  4994.5 1017.53  4996.0 1014.53
  5004.0 1014.53  5005.5 1017.53  5013.0 1023.87  5023.0 1028.55  5033.0 1029.09
  5053.0 1027.37  5093.0 1026.08  5143.0 1027.09  5173.0 1026.78  5183.0 1027.16
  5193.0 1028.29  5213.0 1031.77  5263.0 1042.28  5283.0 1045.48  5345.4 1054.13
#Mann=3,-1,0
  4633.0    0.12       0  4994.5    0.05       0  5005.5    0.15       0
Bank Sta=4994.5,5005.5
XS Rating Curve= 0
Exp/Cntr=0.3,0.1