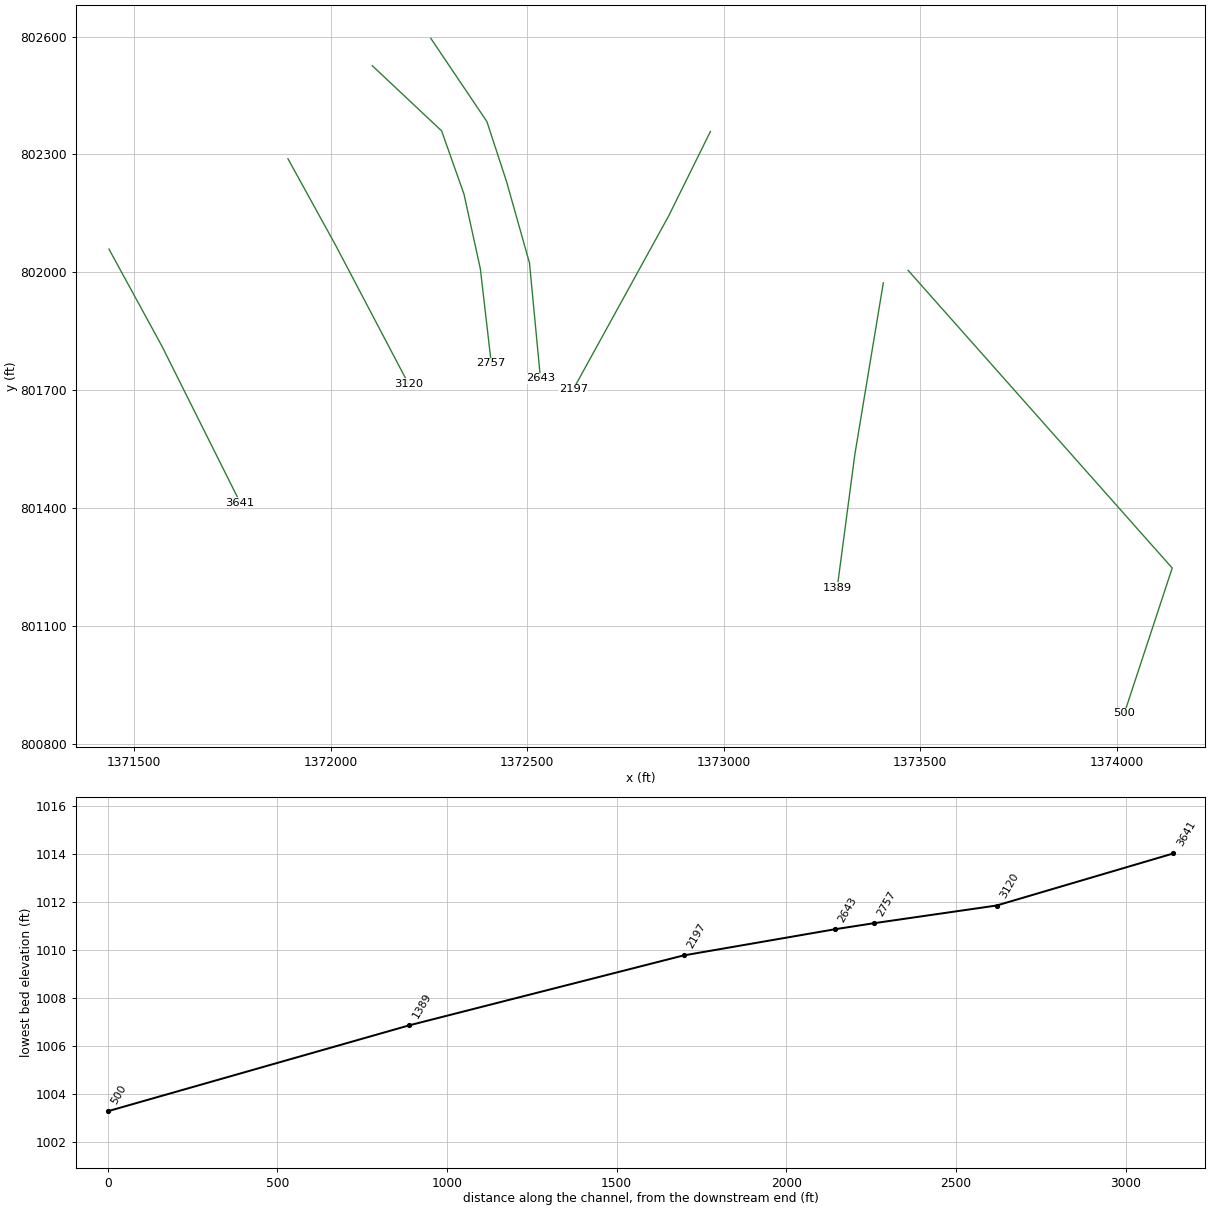
HEC-RAS study Greasy Creek.prj: Greasy Creek Limited Detail Study

--- Greasy Creek.g01 (geometry) --- (continued)

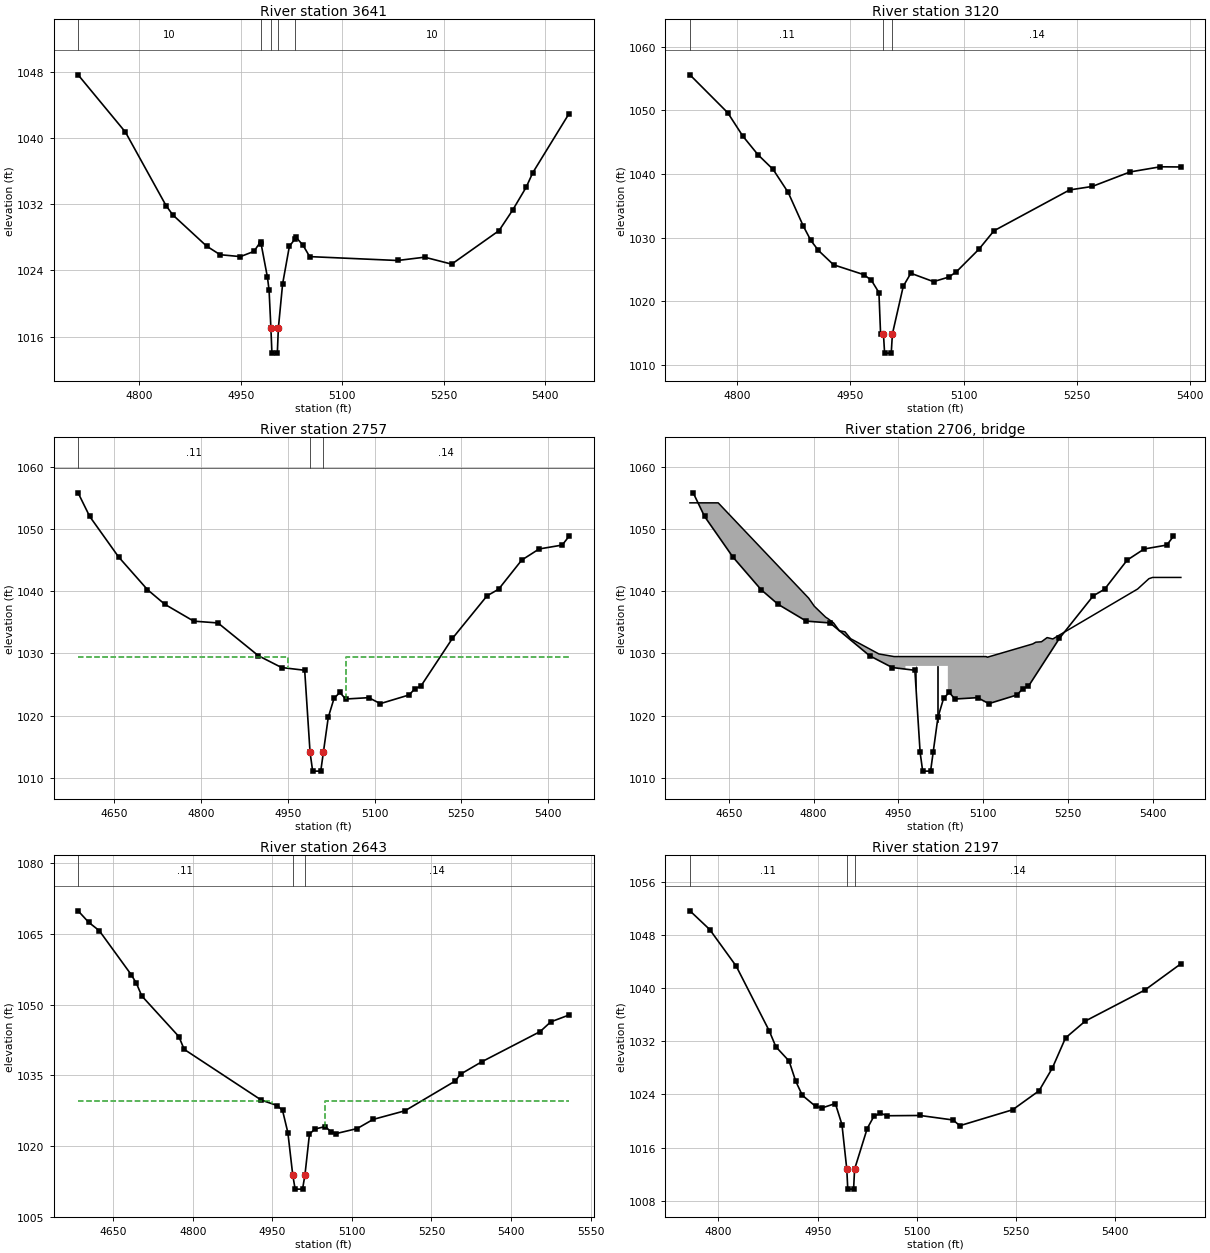
Type RM Length L Ch R = 1,3641,521,521,521
BEGIN DESCRIPTION:
Greasy Creek 7.0
END DESCRIPTION:
XS GIS Cut Line= 3
      1371435.94       802059.13      1371571.17       801811.20
      1371769.51       801414.53
#Sta/Elev= 30
  4709.4 1047.63  4779.4 1040.71  4839.4 1031.84  4849.4 1030.71  4899.4 1026.94
  4919.4 1025.90  4949.4 1025.67  4969.4 1026.30  4979.4 1027.48  4980.0 1027.22
  4989.4 1023.16  4991.8 1021.60  4994.5 1017.01  4996.0 1014.01  5004.0 1014.01
  5005.5 1017.01  5011.8 1022.37  5021.8 1026.91  5030.0 1027.79  5031.8 1027.98
  5041.8 1027.07  5051.8 1025.67  5181.8 1025.20  5221.8 1025.60  5261.8 1024.76
  5331.8 1028.81  5351.8 1031.27  5371.8 1034.03  5381.8 1035.82  5435.3 1042.94
#Mann=5,-1,0
  4709.4      10       0  4980.0    0.14       0  4994.5    0.05       0
  5005.5    0.15       0  5030.0      10       0
Bank Sta=4994.5,5005.5
XS Rating Curve= 0
Exp/Cntr=0.3,0.1

Type RM Length L Ch R = 1,3120,363,363,363
BEGIN DESCRIPTION:
Greasy Creek 6.0
END DESCRIPTION:
XS GIS Cut Line= 3
      1371891.22       802289.05      1372012.94       802068.15
      1372197.74       801716.58
#Sta/Elev= 30
  4738.1 1055.60  4788.1 1049.64  4808.1 1045.96  4828.1 1043.04  4848.1 1040.73
  4868.1 1037.10  4888.1 1031.81  4898.1 1029.55  4908.1 1027.98  4928.1 1025.73
  4968.1 1024.18  4978.1 1023.30  4988.1 1021.36  4990.3 1014.84  4994.1 1014.84
  4995.6 1011.84  5004.4 1011.84  5005.9 1014.84  5020.3 1022.36  5030.3 1024.40
  5060.3 1023.08  5080.3 1023.79  5090.3 1024.60  5120.3 1028.17  5140.3 1031.08
  5240.3 1037.50  5270.3 1038.05  5320.3 1040.33  5360.3 1041.14  5387.5 1041.11
#Mann=3,-1,0
  4738.1    0.11       0  4994.1    0.05       0  5005.9    0.14       0
Bank Sta=4994.1,5005.9
XS Rating Curve= 0
Exp/Cntr=0.5,0.3

Type RM Length L Ch R = 1,2757,114,114,114
BEGIN DESCRIPTION:
White Plains Rd [Greasy--1] US
END DESCRIPTION:
XS GIS Cut Line= 5
      1372105.87       802525.68      1372282.17       802359.90
      1372339.09       802198.86      1372380.74       802008.66
      1372408.50       801768.48
#Sta/Elev= 30
  4587.2 1055.80  4607.2 1052.02  4657.2 1045.51  4707.2 1040.25  4737.2 1037.90
  4787.2 1035.19  4829.2 1034.90  4899.2 1029.63  4939.2 1027.74  4979.2 1027.30
  4988.5 1014.10  4993.0 1011.10  5007.0 1011.10  5011.5 1014.10  5020.0 1019.74
  5030.0 1022.79  5040.0 1023.74  5050.0 1022.68  5090.0 1022.90  5110.0 1021.94
  5160.0 1023.34  5170.0 1024.36  5180.0 1024.72  5234.7 1032.41  5294.7 1039.26
  5314.7 1040.32  5354.7 1045.00  5384.7 1046.78  5424.7 1047.41  5436.5 1048.82
#Mann=3,-1,0
  4587.2    0.11       0  4988.5    0.05       0  5011.5    0.14       0
#XS Ineff=2,0
    0.00 4950.00 1029.50 5050.00    0.00 1029.50
Permanent Ineff=
       F       F
Bank Sta=4988.5,5011.5
XS Rating Curve= 0
Exp/Cntr=0.5,0.3

Type RM Length L Ch R =3,2706,,,
BEGIN DESCRIPTION:
White Plains Rd [Greasy--1] TOR
Structure ID: LDS_GC_01
Approximate Survey Structure
END DESCRIPTION:
Bridge Culvert--1,0,-1,-1,0
Deck Dist Width WeirC Skew NumUp NumDn MinLoCord MaxHiCord MaxSubmerge Is_Ogee
38.5,25,3,,27,27,,,0.95,0,1,1,,,
  4581.4  4631.4  4791.4  4801.4  4821.4  4825.6  4835.6  4845.6  4855.6  4865.6
  4915.6  4942.5  4962.5  4962.5  5037.5  5037.5  5105.0  5107.6  5187.6  5193.1
  5203.1  5213.1  5223.1  5373.1  5393.1  5399.6  5449.6
 1054.19 1054.19 1038.88 1037.58 1035.83 1035.58 1034.89 1033.64 1033.48 1032.37
 1029.92 1029.50 1029.50 1029.50 1029.50 1029.50 1029.50 1029.40 1031.53 1031.81
 1031.88 1032.55 1032.33 1040.35 1042.01 1042.21 1042.21
  991.10  991.10  991.10  991.10  991.10  991.10  991.10  991.10  991.10  991.10
  991.10  991.10  991.10 1028.00 1028.00  991.10  991.10  991.10  991.10  991.10
  991.10  991.10  991.10  991.10  991.10  991.10  991.10
  4581.4  4631.4  4791.4  4801.4  4821.4  4825.6  4835.6  4845.6  4855.6  4865.6
  4915.6  4942.5  4962.5  4962.5  5037.5  5037.5  5105.0  5107.6  5187.6  5193.1
  5203.1  5213.1  5223.1  5373.1  5393.1  5399.6  5449.6
 1054.19 1054.19 1038.88 1037.58 1035.83 1035.58 1034.89 1033.64 1033.48 1032.37
 1029.92 1029.50 1029.50 1029.50 1029.50 1029.50 1029.50 1029.40 1031.53 1031.81
 1031.88 1032.55 1032.33 1040.35 1042.01 1042.21 1042.21
  991.10  991.10  991.10  991.10  991.10  991.10  991.10  991.10  991.10  991.10
  991.10  991.10  991.10 1028.00 1028.00  991.10  991.10  991.10  991.10  991.10
  991.10  991.10  991.10  991.10  991.10  991.10  991.10
Pier Skew, UpSta & Num, DnSta & Num=,4981.3,2,4981.3,2,0,0,0,0,0
       1       1
 1024.32 1028.00
       1       1
 1020.89 1028.00
Pier Skew, UpSta & Num, DnSta & Num=,5018.8,2,5018.8,2,0,0,0,0,0
       1       1
 1018.94 1028.00
       1       1
 1021.29 1028.00
Abutment Skew #Up #Dn=,2,2
  4962.5  4965.0
 1028.00 1027.59
  4962.5  4965.0
 1028.00 1028.00
Abutment Skew #Up #Dn=,2,2
  5035.0  5037.5
 1023.27 1028.00
  5035.0  5037.5
 1023.82 1028.00
BR Coef=1,1,0,1.25,0,,,0.8,0,2,0,
WSPro=,,,, 1 ,,,, 0 ,,,, 0 ,,,,-1 ,-1 ,-1 , 0 , 0 , 0 , 0 , 0
BC Design=,,0,,0,,,,,,

Type RM Length L Ch R = 1,2643,446,446,446
BEGIN DESCRIPTION:
White Plains Rd [Greasy--1] DS
END DESCRIPTION:
XS GIS Cut Line= 5
      1372254.65       802595.39      1372397.40       802383.51
      1372447.37       802230.79      1372505.68       802023.94
      1372533.57       801730.74
#Sta/Elev= 30
  4583.8 1069.94  4603.8 1067.50  4623.8 1065.72  4683.8 1056.41  4693.8 1054.54
  4703.8 1051.88  4773.8 1043.24  4783.8 1040.53  4929.3 1029.75  4959.3 1028.60
  4969.3 1027.55  4979.3 1022.85  4988.5 1013.85  4993.0 1010.85  5007.0 1010.85
  5011.5 1013.85  5020.0 1022.51  5030.0 1023.60  5050.0 1024.14  5060.0 1023.06
  5070.0 1022.64  5110.0 1023.71  5140.0 1025.65  5200.0 1027.48  5294.9 1033.81
  5304.9 1035.26  5344.9 1037.89  5454.9 1044.30  5474.9 1046.36  5509.4 1047.82
#Mann=3,-1,0
  4583.8    0.11       0  4988.5    0.05       0  5011.5    0.14       0
#XS Ineff=2,0
    0.00 4950.00 1029.50 5050.00    0.00 1029.50
Permanent Ineff=
       F       F
Bank Sta=4988.5,5011.5
XS Rating Curve= 0
Exp/Cntr=0.5,0.3

Type RM Length L Ch R = 1,2197,808,808,808
BEGIN DESCRIPTION:
Greasy Creek 4.0
END DESCRIPTION:
XS GIS Cut Line= 3
      1372965.95       802358.36      1372860.42       802144.78
      1372617.25       801702.78
#Sta/Elev= 30
  4756.8 1051.63  4786.8 1048.81  4826.8 1043.31  4876.8 1033.57  4886.8 1031.18
  4906.8 1029.03  4916.8 1026.01  4926.8 1023.88  4946.8 1022.22  4956.8 1021.98
  4976.8 1022.64  4986.8 1019.47  4994.1 1012.76  4995.6 1009.76  5004.4 1009.76
  5005.9 1012.76  5025.0 1018.88  5035.0 1020.70  5045.0 1021.19  5055.0 1020.80
  5105.0 1020.84  5155.0 1020.16  5165.0 1019.30  5245.0 1021.70  5285.0 1024.56
  5305.0 1027.96  5325.0 1032.51  5355.0 1035.05  5445.0 1039.71  5499.5 1043.66
#Mann=3,-1,0
  4756.8    0.11       0  4994.1    0.05       0  5005.9    0.14       0
Bank Sta=4994.1,5005.9
XS Rating Curve= 0
Exp/Cntr=0.3,0.1

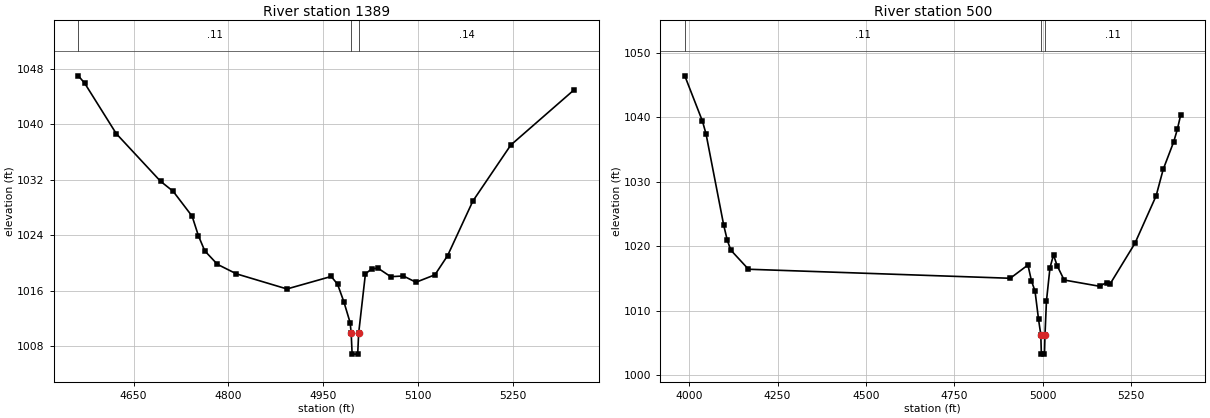
Type RM Length L Ch R = 1,1389,889,889,889
BEGIN DESCRIPTION:
Greasy Creek 3.0
END DESCRIPTION:
XS GIS Cut Line= 3
      1373405.88       801973.52      1373333.21       801535.44
      1373288.67       801198.14
#Sta/Elev= 30
  4562.5 1046.95  4572.5 1045.89  4622.5 1038.62  4692.5 1031.76  4712.5 1030.31
  4742.5 1026.72  4752.5 1023.89  4762.5 1021.73  4782.5 1019.79  4812.5 1018.42
  4892.5 1016.24  4962.5 1018.04  4972.5 1016.93  4982.5 1014.40  4992.5 1011.36
  4994.1 1009.85  4995.6 1006.85  5004.4 1006.85  5005.9 1009.85  5016.6 1018.41
  5026.6 1019.14  5036.6 1019.23  5056.6 1018.01  5076.6 1018.11  5096.6 1017.21
  5126.6 1018.28  5146.6 1021.04  5186.6 1028.91  5246.6 1036.98  5346.8 1044.94
#Mann=3,-1,0
  4562.5    0.11       0  4994.1    0.05       0  5005.9    0.14       0
Bank Sta=4994.1,5005.9
XS Rating Curve= 0
Exp/Cntr=0.3,0.1

Type RM Length L Ch R = 1,500,0,0,0
BEGIN DESCRIPTION:
Greasy Creek 1.0
END DESCRIPTION:
XS GIS Cut Line= 3
      1373469.00       802005.02      1374140.82       801247.79
      1374018.94       800878.06
#Sta/Elev= 30
  3987.7 1046.45  4037.7 1039.40  4047.7 1037.44  4097.7 1023.28  4107.7 1020.96
  4117.7 1019.41  4167.7 1016.44  4907.7 1015.04  4957.7 1017.10  4967.7 1014.62
  4977.7 1013.05  4987.7 1008.65  4994.1 1006.27  4995.6 1003.27  5004.4 1003.27
  5005.9 1006.27  5010.0 1011.49  5020.0 1016.68  5030.0 1018.66  5040.0 1017.02
  5060.0 1014.77  5160.0 1013.80  5180.0 1014.38  5190.0 1014.16  5260.0 1020.45
  5320.0 1027.82  5340.0 1031.93  5370.0 1036.25  5380.0 1038.15  5389.3 1040.34
#Mann=3,-1,0
  3987.7    0.11       0  4994.1    0.05       0  5005.9    0.11       0
Bank Sta=4994.1,5005.9
XS Rating Curve= 0
Exp/Cntr=0.3,0.1

Chan Stop Cuts=-1