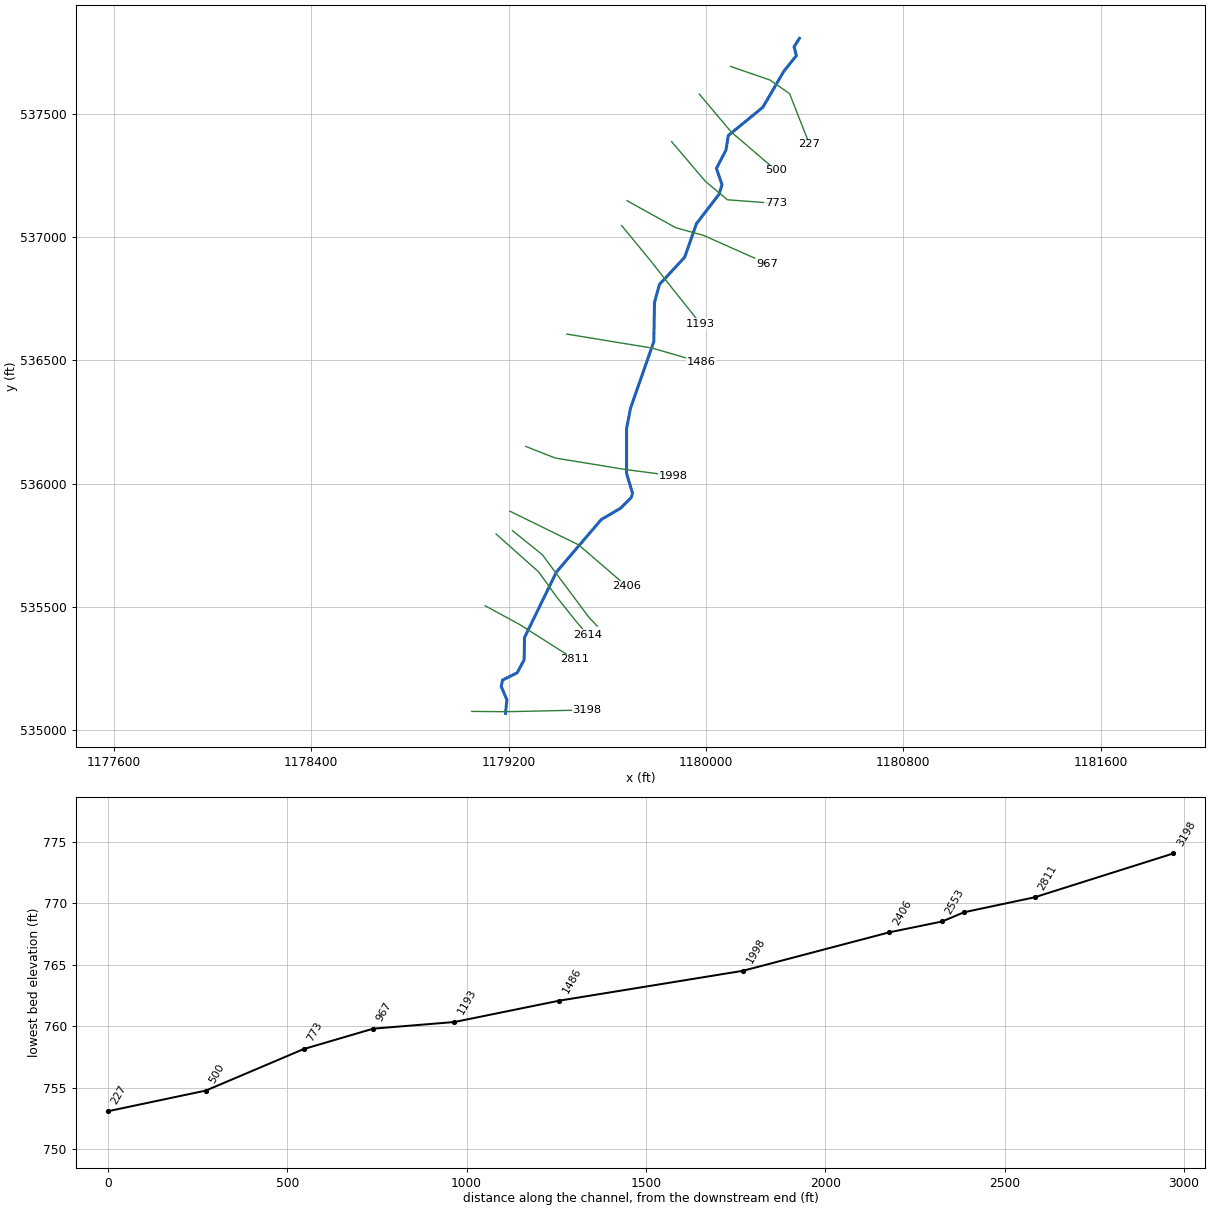
--- lds_ashworth_crk_trib5.prj (project) ---

Proj Title=Ashworth Creek Trib 5 Limited Detail Study
Current Plan=p02
Default Exp/Contr=0.3,0.1
English Units
Geom File=g01
Flow File=f02
Plan File=p02
Y Axis Title=Elevation
X Axis Title(PF)=Main Channel Distance
X Axis Title(XS)=Station
BEGIN DESCRIPTION:
Ashworth Creek Trib 5
END DESCRIPTION:
DSS Export Rating Curves= 0
DSS Export Rating Curve Sorted= 0
DSS Export Volume Flow Curves= 0
DXF OffsetX= 0
DXF OffsetY= 0
DXF ScaleX= 1
DXF ScaleY= 10

--- lds_ashworth_crk_trib5.p02 (plan) ---

Plan Title=Floodway Run
Program Version=3.13
Short Identifier=Floodway
Geom File=g01
Flow File=f02
Subcritical Flow
K Sum by GR= 0
Std Step Tol= 0.01
Critical Tol= 0.01
Num of Std Step Trials= 20
Max Error Tol= 0.3
Flow Tol Ratio= 0.001
Split Flow NTrial= 30
Split Flow Tol= 0.02
Split Flow Ratio= 0.02
Log Output Level= 0
Friction Slope Method= 1
Unsteady Friction Slope Method= 2
Unsteady Bridges Friction Slope Method= 1
Parabolic Critical Depth
Global Vel Dist= 0 , 0 , 0
Global Log Level= 0
CheckData=True
Encroach Param=-1 ,5,5, 2
Encroach River=Ashworth Creek T
Encroach Reach=Reach-1
Encroach Node=3198
       1  4974.3  5056.6
Encroach Node=2811
       1    4920    5070
Encroach Node=2614
       1    4955    5045
Encroach Node=2553
       1    4955    5045
Encroach Node=2406
       1    4960    5035
Encroach Node=1998
       4      .7
Encroach Node=1486
       1    4948  5027.3
Encroach Node=1193
       4      .7
Encroach Node=967
       1    4950    5024
Encroach Node=773
       1    4950    5030
Encroach Node=500
       1    4975  5018.5
Encroach Node=227
       1    4962    5033
BEGIN DESCRIPTION:
Floodway Run
END DESCRIPTION:
Computation Interval=1HOUR
Output Interval=1HOUR
Run HTab= 0
Run UNet= 0
Run PostProcess= 0
UNET Theta= 1
UNET Theta Warmup= 1
UNET ZTol= 0.02
UNET ZSATol= 0.05
UNET MxIter= 20
UNET MaxInSteps= 0
UNET DtIC= 0
UNET DtMin= 0
UNET MaxCRTS= 20
UNET WFStab= 2
UNET SFStab= 1
UNET WFX= 1
UNET SFX= 1
UNET DSS MLevel= 4
UNET DZMax Abort= 100
UNET Convert EG Bridges=-1
UNET Use Existing IB Tables=-1
UNET Froude Reduction=False
UNET Froude Limit= 1
UNET Froude Power= 10
Instantaneous Interval=1HOUR
Write IC File= 0
Echo Input=False
Echo Output=False
Write Detailed= 0
Detailed Automatic Start=False, 10

--- lds_ashworth_crk_trib5.f02 (steady flow) ---

Flow Title=Floodway
Program Version=3.13
Number of Profiles= 2
Profile Names=100-year,100-FW
River Rch & RM=Ashworth Creek T,Reach-1         ,3198
     980     980
River Rch & RM=Ashworth Creek T,Reach-1         ,1193
    1010    1010
Boundary for River Rch & Prof#=Ashworth Creek T,Reach-1         , 1
Up Type= 0
Dn Type= 3
Dn Slope=0.006
Boundary for River Rch & Prof#=Ashworth Creek T,Reach-1         , 2
Up Type= 0
Dn Type= 3
Dn Slope=0.006
DSS Import GetInterval= 0
DSS Import GetPeak= 0
DSS Import FillOption= 0

--- lds_ashworth_crk_trib5.g01 (geometry) ---

Geom Title=Existing Conditions
Program Version=3.13

River Reach=Ashworth Creek T,Reach-1
Reach XY= 30
      1179187.25       535068.56      1179192.63       535123.81
      1179169.75       535177.75      1179175.13       535203.38
      1179234.38         535233.      1179262.75       535285.56
      1179264.13       535375.88       1179393.5       535641.44
      1179575.38       535854.38      1179653.63       535900.19
      1179696.75       535943.31      1179702.13       535960.88
      1179677.88       536041.75      1179677.88       536222.38
        1179694.       536305.94      1179788.38        536575.5
      1179791.13       536734.56      1179811.25       536807.31
      1179913.38       536917.63       1179961.5       537054.25
       1180052.5       537172.63        1180065.       537211.31
      1180042.13         537278.      1180080.88       537351.88
      1180090.25       537411.19       1180230.5       537525.81
      1180315.59       537671.85       1180366.3       537734.99
      1180356.97       537771.28      1180378.75       537805.16

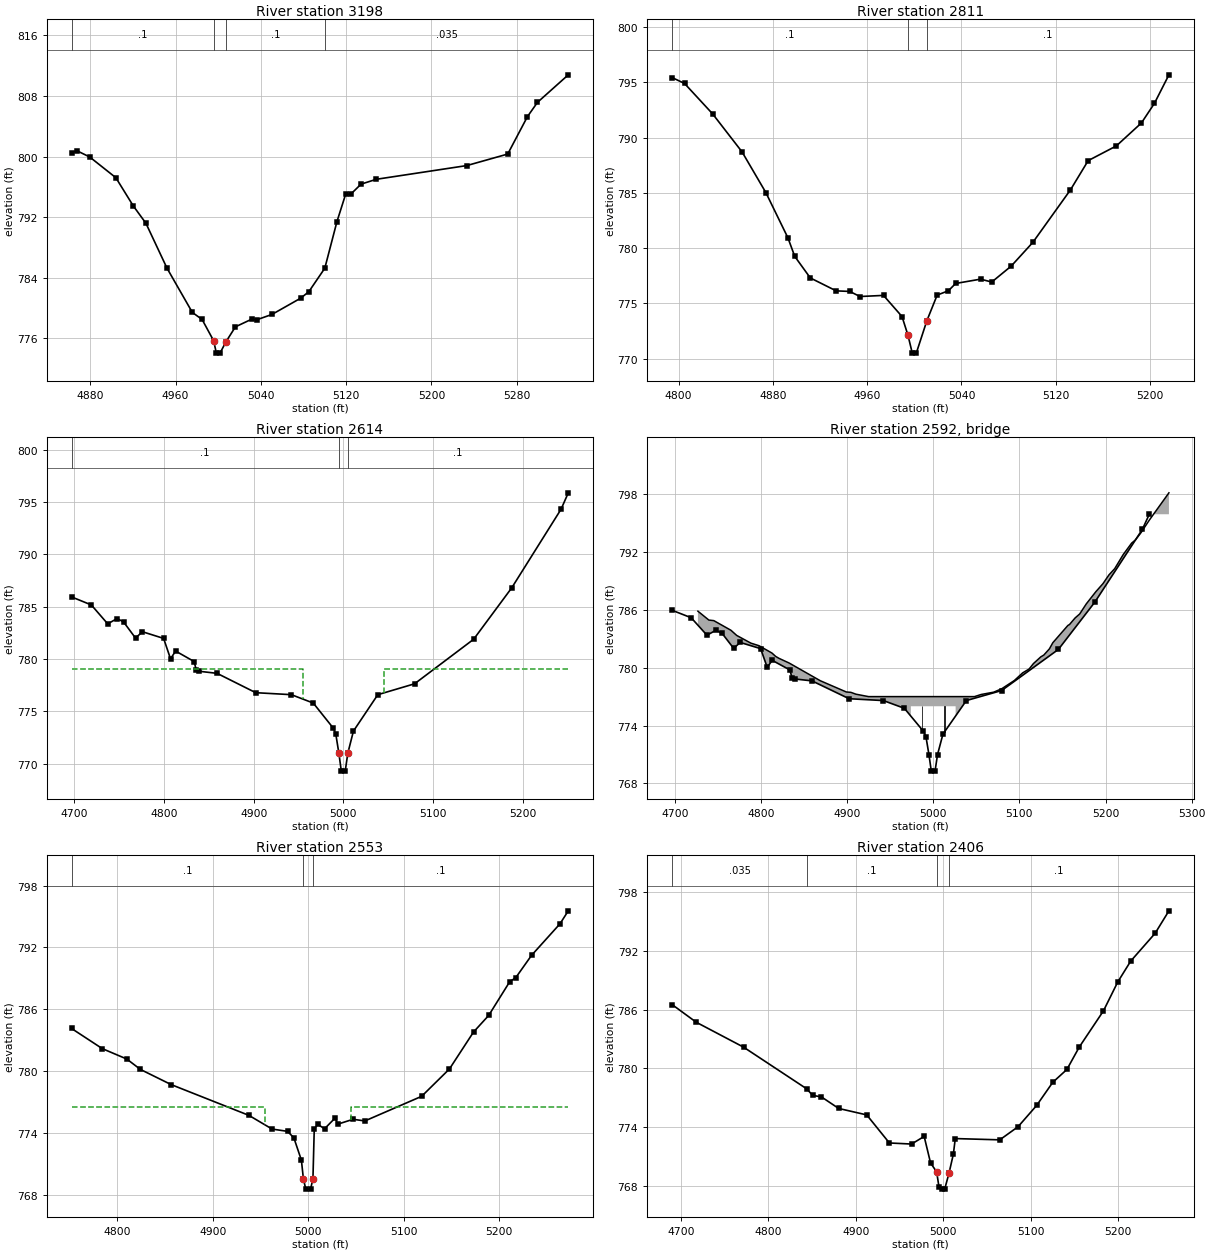
Type RM Length L Ch R = 1 ,3198    ,387,387,387
BEGIN DESCRIPTION:
Ashworth Creek Trib 5 6.0
END DESCRIPTION:
XS GIS Cut Line= 3
      1179050.49       535076.51      1179191.68       535075.33
      1179516.42       535082.39
#Sta/Elev= 30
  4862.4  800.53  4867.6  800.76  4879.5  799.94    4904  797.21  4920.3   793.5
  4932.2   791.2    4952  785.27 4975.74  779.44  4984.9  778.51  4995.7  775.71
  4998.3  774.07  5001.7  774.07  5007.3  775.57 5016.17  777.54 5031.77  778.57
 5035.97  778.46 5050.39  779.17  5077.4  781.32    5085  782.17    5100  785.27
  5111.4  791.42  5119.5  795.01  5124.3  795.03    5134  796.36  5148.3     797
  5233.2  798.81  5271.6  800.33  5290.1  805.27  5299.5  807.15  5328.4  810.78
#Mann= 4 ,-1 , 0
  4862.4      .1       0  4995.7     .05       0  5007.3      .1       0
    5100    .035       0
Bank Sta=4995.7,5007.3
Exp/Cntr=0.3,0.1

Type RM Length L Ch R = 1 ,2811    ,197,197,197
BEGIN DESCRIPTION:
Ashworth Creek Trib 5 5.5
END DESCRIPTION:
XS GIS Cut Line= 3
      1179104.61       535504.79      1179243.45       535429.48
      1179465.82       535288.29
#Sta/Elev= 30
  4794.6  795.42  4805.1  794.89    4829  792.13  4853.9   788.7  4874.1  785.02
  4892.8  780.93  4898.6  779.25  4911.8   777.3 4933.77  776.13 4945.28  776.08
  4953.9  775.62 4973.89  775.72 4989.59  773.81  4994.6  772.13  4998.3   770.5
  5001.7   770.5  5010.7  773.44 5019.41  775.75 5028.94  776.14 5035.07   776.8
 5056.19  777.19 5065.72  776.93  5082.2  778.37  5100.6  780.52  5132.5  785.27
  5147.5  787.91  5171.4  789.24  5192.7  791.32  5203.7  793.09    5216  795.67
#Mann= 3 ,-1 , 0
  4794.6      .1       0  4994.6    .053       0  5010.7      .1       0
Bank Sta=4994.6,5010.7
Exp/Cntr=0.5,0.3

Type RM Length L Ch R = 1 ,2614    ,61,61,61
BEGIN DESCRIPTION:
SR 1207 - US
END DESCRIPTION:
XS GIS Cut Line= 5
      1179149.32        535795.4      1179322.28       535641.27
      1179392.87       535542.44      1179471.71        535443.6
      1179519.95       535387.13
#Sta/Elev= 30
  4696.9  785.94    4719  785.17  4737.3  783.36  4747.7  783.87  4754.9  783.55
  4768.3     782  4775.9  782.61  4799.6  781.97  4807.3  780.02    4813  780.76
  4833.6  779.76    4836  778.95    4839  778.83  4859.2  778.63 4902.33  776.78
 4942.05  776.59 4966.44  775.79  4988.6  773.41 4991.51  772.86    4995     771
 4997.74  769.28 5002.08  769.28    5005     771 5011.25  773.11 5038.43  776.59
  5079.4  777.63  5145.3  781.89  5187.7   786.8  5242.8  794.33  5250.8  795.89
#Mann= 3 ,-1 , 0
  4696.9      .1       0    4995     .05       0    5005      .1       0
#XS Ineff= 2 , 0
       0    4955     779    5045       0     779
Permanent Ineff=
       F       F
Bank Sta=4995,5005
Exp/Cntr=0.5,0.3

Type RM Length L Ch R = 3 ,2592    ,,,
BEGIN DESCRIPTION:
SR 1207
Structure ID: Wood Road
Approximate Survey Structure
END DESCRIPTION:
Bridge Culvert--1,0,-1,-1, 0
Deck Dist Width WeirC Skew NumUp NumDn MinLoCord MaxHiCord MaxSubmerge Is_Ogee
9.5,25,3,0, 47, 47, , , , 0, 1,1,,
  4726.8  4739.5  4745.3  4765.2  4771.8  4788.3  4797.8  4812.8    4817  4820.8
  4832.7    4869  4899.1  4904.4  4910.3  4924.9    4974    4974    5026    5026
  5047.9  5055.6  5070.2  5079.6  5094.2  5103.8  5111.3  5116.3  5124.9  5128.3
  5134.8  5138.8  5156.3  5158.2  5164.7    5170  5177.7  5188.6  5197.1  5203.9
  5210.7  5220.5  5230.3  5234.6    5241  5250.9  5273.6
  785.85  784.93  784.87  783.87  783.34  782.54  782.27  781.51  781.17  780.97
  780.48  778.64  777.48  777.44  777.25     777     777     777     777     777
     777  777.22  777.46  777.82  778.67  779.46  779.86  780.42  781.12   781.3
  781.94  782.58  784.37  784.47  785.15  785.56  786.61  787.85  788.71   789.6
  790.26  791.71   792.9  793.22  793.96  795.29  798.11
  748.78  748.78  748.78  748.78  748.78  748.78  748.78  748.78  748.78  748.78
  748.78  748.78  748.78  748.78  748.78  748.78  748.78     776     776  748.78
  748.78  748.78  748.78  748.78  748.78  748.78  748.78  748.78  748.78  748.78
  748.78  748.78  748.78  748.78  748.78  748.78  748.78  748.78  748.78  748.78
  748.78  748.78  748.78  748.78  748.78  748.78  748.78
  4726.8  4739.5  4745.3  4765.2  4771.8  4788.3  4797.8  4812.8    4817  4820.8
  4832.7    4869  4899.1  4904.4  4910.3  4924.9    4974    4974    5026    5026
  5047.9  5055.6  5070.2  5079.6  5094.2  5103.8  5111.3  5116.3  5124.9  5128.3
  5134.8  5138.8  5156.3  5158.2  5164.7    5170  5177.7  5188.6  5197.1  5203.9
  5210.7  5220.5  5230.3  5234.6    5241  5250.9  5273.6
  785.85  784.93  784.87  783.87  783.34  782.54  782.27  781.51  781.17  780.97
  780.48  778.64  777.48  777.44  777.25     777     777     777     777     777
     777  777.22  777.46  777.82  778.67  779.46  779.86  780.42  781.12   781.3
  781.94  782.58  784.37  784.47  785.15  785.56  786.61  787.85  788.71   789.6
  790.26  791.71   792.9  793.22  793.96  795.29  798.11
  748.78  748.78  748.78  748.78  748.78  748.78  748.78  748.78  748.78  748.78
  748.78  748.78  748.78  748.78  748.78  748.78  748.78     776     776  748.78
  748.78  748.78  748.78  748.78  748.78  748.78  748.78  748.78  748.78  748.78
  748.78  748.78  748.78  748.78  748.78  748.78  748.78  748.78  748.78  748.78
  748.78  748.78  748.78  748.78  748.78  748.78  748.78
Pier Skew, UpSta & Num, DnSta & Num=  ,4987, 2 ,4987, 2 , 0 , 0 , 0 ,0,0
       1       1
  775.99     776
       1       1
  772.96     776
Pier Skew, UpSta & Num, DnSta & Num=  ,5013, 2 ,5013, 2 , 0 , 0 , 0 ,0,0
       1       1
  774.08     776
       1       1
  774.64     776
Abutment Skew #Up #Dn= , 2 , 2
    4974    4982
     776     774
    4974    4982
     776  772.82
Abutment Skew #Up #Dn= , 2 , 2
    5020    5026
  774.18     776
    5020    5026
     774     776
BR Coef= 1 , 1 , 1 ,1.25, 0 ,,,0.8,0,2,0,
WSPro=,,,, 1 ,,,, 0 ,,,, 0 ,,,,-1 ,-1 ,-1 , 0 , 0 , 0 , 0 , 0
BC Design=,, 0 ,, 0 ,,,,,,
BC HTab HWMax=795.89

Type RM Length L Ch R = 1 ,2553    ,147,147,147
BEGIN DESCRIPTION:
SR 1207 - DS
END DESCRIPTION:
XS GIS Cut Line= 5
      1179215.21       535809.52       1179336.4       535711.87
      1179414.05       535607.15      1179524.65        535458.9
      1179558.77       535422.42
#Sta/Elev= 30
  4751.8  784.13  4784.1  782.17  4809.8  781.16  4824.1  780.15  4856.3  778.68
  4937.9  775.69  4962.2  774.36  4978.4  774.14    4985  773.51  4992.9  771.34
    4995  769.53  4997.5  768.53  5002.5  768.53    5005  769.53  5006.4  774.41
  5010.2  774.81  5017.2  774.39  5028.2  775.43 5031.12  774.84 5047.11  775.31
 5059.46  775.15    5119  777.54  5148.2   780.2  5173.4  783.78  5189.3  785.39
  5211.4  788.67  5217.7  789.06  5234.3  791.23  5264.1  794.29  5272.8  795.55
#Mann= 3 ,-1 , 0
  4751.8      .1       0    4995     .05       0    5005      .1       0
#XS Ineff= 2 , 0
       0    4955   776.5    5045       0   776.5
Permanent Ineff=
       F       F
Bank Sta=4995,5005
Exp/Cntr=0.5,0.3

Type RM Length L Ch R = 1 ,2406    ,408,408,408
BEGIN DESCRIPTION:
Ashworth Creek Trib 5 5.0
END DESCRIPTION:
XS GIS Cut Line= 3
      1179204.62       535888.35      1179483.47       535751.87
      1179678.79       535583.62
#Sta/Elev= 30
  4689.9  786.52  4717.4  784.72  4771.6  782.17  4844.1  777.89  4850.5  777.24
  4860.7  777.08  4880.4   775.9  4912.5  775.24  4938.4  772.37  4963.8  772.26
  4978.2  773.04  4985.5  770.33  4992.5  769.41  4995.2  767.84  4998.3  767.65
  5001.7  767.65  5006.7  769.31  5011.6  771.23  5013.8  772.82  5064.7  772.69
  5085.6  774.03  5106.9  776.21  5125.3  778.57  5141.5  779.89  5155.7  782.19
  5183.3  785.88  5199.7  788.84  5214.5  790.97  5242.4  793.81  5258.2  796.11
#Mann= 4 ,-1 , 0
  4689.9    .035       0  4844.1      .1       0  4992.5     .05       0
  5006.7      .1       0
Bank Sta=4992.5,5006.7
Exp/Cntr=0.3,0.1

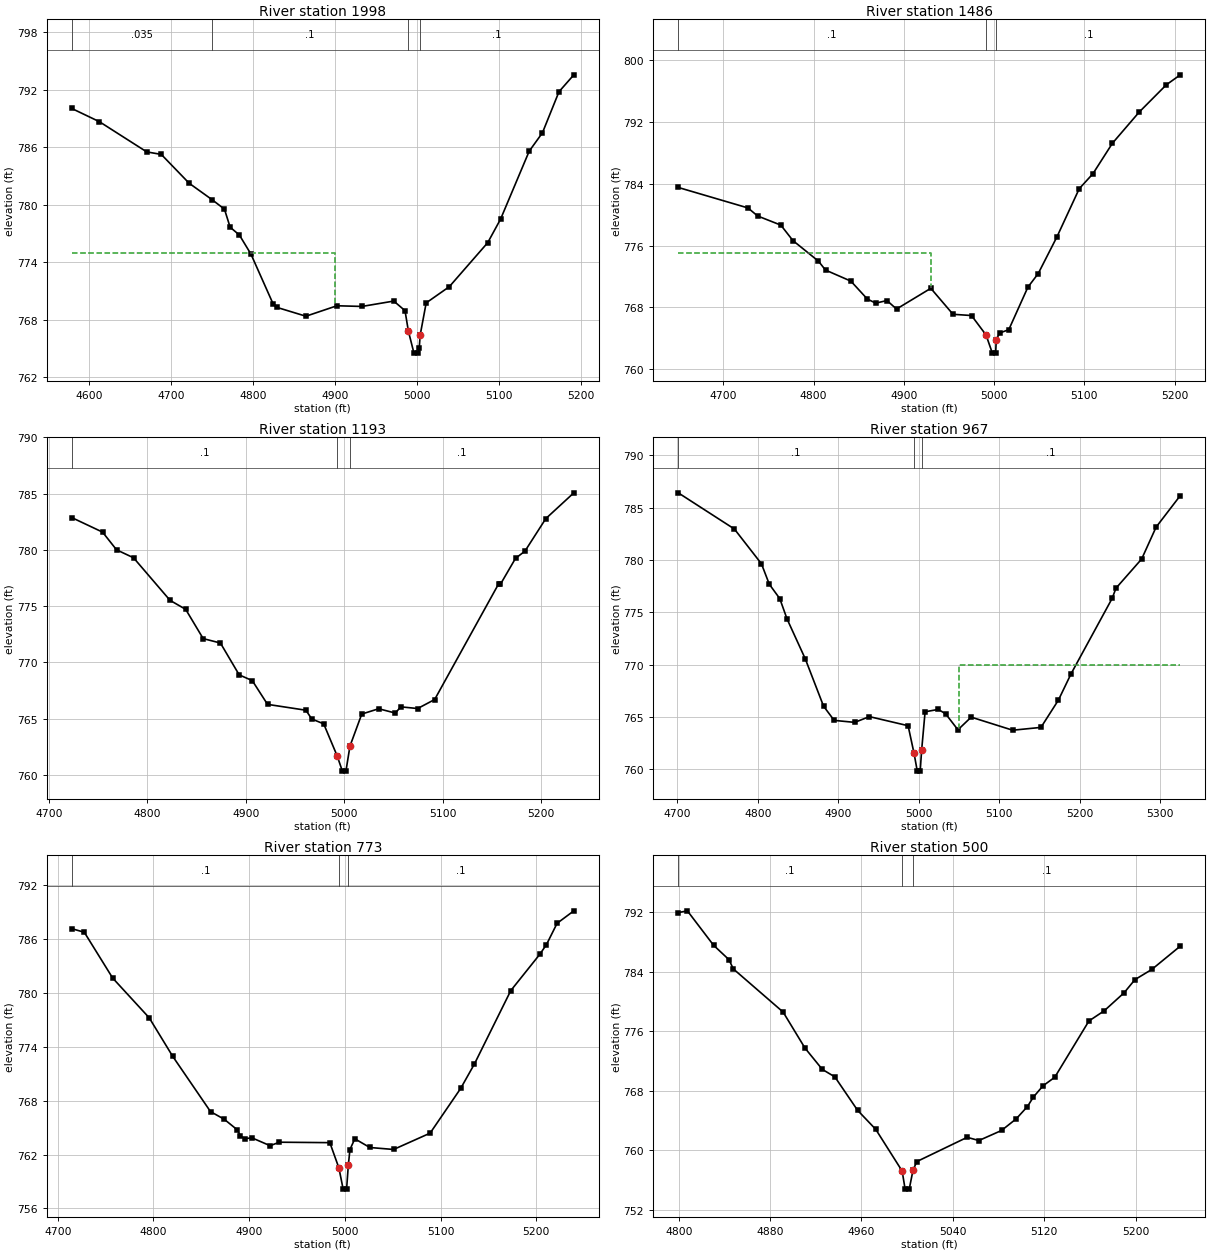
Type RM Length L Ch R = 1 ,1998    ,512,512,512
BEGIN DESCRIPTION:
Ashworth Creek Trib 5 4.0
END DESCRIPTION:
XS GIS Cut Line= 4
      1179269.33       536150.73      1179388.39       536103.84
      1179675.14       536056.83      1179867.04        536031.9
#Sta/Elev= 30
  4579.2  790.04  4612.9  788.66  4670.6  785.51  4688.3  785.25  4722.3  782.24
    4750  780.54  4765.3  779.54  4772.2  777.66  4783.5  776.84  4797.6  774.85
  4824.7  769.64  4829.7  769.28  4864.6  768.37  4902.4  769.46  4932.9  769.39
  4971.7  769.95  4985.4  768.95  4989.5  766.82  4996.3  764.52  5001.7  764.52
  5002.7  765.02  5003.9  766.41  5011.2  769.76  5039.4  771.45  5086.2  776.04
  5101.9   778.5  5136.8  785.59  5152.9   787.5  5173.1  791.79  5191.2  793.55
#Mann= 4 ,-1 , 0
  4579.2    .035       0    4750      .1       0  4989.5     .05       0
  5003.9      .1       0
#XS Ineff= 2 , 0
       0    4900     775               0
Permanent Ineff=
       F       F
Bank Sta=4989.5,5003.9
Exp/Cntr=0.3,0.1

Type RM Length L Ch R = 1 ,1486    ,293,293,293
BEGIN DESCRIPTION:
Ashworth Creek Trib 5 3.0
END DESCRIPTION:
XS GIS Cut Line= 3
      1179436.41       536606.07      1179781.15        536549.6
      1179979.99       536491.95
#Sta/Elev= 30
  4649.9  783.51  4727.2  780.86  4737.9  779.82  4763.6  778.64    4777  776.64
  4805.3  773.98  4813.1  772.83  4841.2   771.4  4859.4  769.09  4868.7  768.55
  4881.2  768.89  4891.8  767.79  4929.8  770.47  4954.4  767.11  4974.9  766.95
    4991  764.44    4998  762.09  5001.7  762.09  5002.3  763.81    5006  764.69
  5016.2  765.12  5037.4  770.62  5048.8  772.37  5069.7  777.15  5094.3  783.35
  5109.5  785.29  5131.1  789.23  5160.7  793.25  5190.8  796.78  5206.3  798.07
#Mann= 3 ,-1 , 0
  4649.9      .1       0    4991     .05       0  5002.3      .1       0
#XS Ineff= 2 , 0
       0  4929.8     775               0
Permanent Ineff=
       F       F
Bank Sta=4991,5002.3
Exp/Cntr=0.3,0.1

Type RM Length L Ch R = 1 ,1193    ,226,226,226
BEGIN DESCRIPTION:
Ashworth Creek Trib 5 2.0
END DESCRIPTION:
XS GIS Cut Line= 4
      1179657.92       537046.17      1179772.43       536907.19
      1179869.39       536783.74      1179977.64       536648.43
#Sta/Elev= 30
  4723.1  782.87  4754.4  781.58  4768.6  780.01  4785.9   779.3    4823  775.52
  4838.9  774.72  4856.7  772.12  4874.2  771.73  4893.3   768.9  4906.6  768.39
  4922.1  766.28  4961.1  765.76  4967.1  764.98  4979.2  764.55  4992.9   761.7
  4998.2  760.35  5001.8  760.35  5005.9  762.57  5017.9  765.42  5035.1  765.89
    5052  765.51  5057.6  766.06  5074.7  765.91    5092  766.71    5157  776.98
  5158.9  776.95  5174.2  779.25  5183.8  779.89    5205  782.78  5233.5  785.07
#Mann= 3 ,-1 , 0
  4723.1      .1       0  4992.9     .05       0  5005.9      .1       0
Bank Sta=4992.9,5005.9
Exp/Cntr=0.3,0.1

Type RM Length L Ch R = 1 ,967     ,194,194,194
BEGIN DESCRIPTION:
Ashworth Creek Trib 5 1.75
END DESCRIPTION:
XS GIS Cut Line= 4
      1179679.72        537147.1      1179876.96        537037.6
      1179989.95       537006.26      1180246.89       536892.06
#Sta/Elev= 30
  4701.1  786.41  4770.9  782.95  4804.5  779.63  4814.3  777.67  4827.3   776.3
  4836.3  774.36    4859  770.54  4881.7  766.02  4894.9  764.66  4920.4  764.47
  4938.7  765.02  4986.8  764.15  4994.2   761.5  4998.2  759.81  5001.8  759.81
  5003.6   761.8  5007.9  765.48  5024.3  765.71  5033.5  765.28  5048.7  763.76
  5065.2  764.97  5116.8  763.72  5151.9  763.99  5173.6   766.6  5189.3  769.11
  5240.3  776.31  5245.2   777.3  5277.1  780.09    5295  783.13  5325.1  786.15
#Mann= 3 ,-1 , 0
  4701.1      .1       0  4994.2     .05       0  5003.6      .1       0
#XS Ineff= 2 , 0
       0                    5050       0     770
Permanent Ineff=
       F       F
Bank Sta=4994.2,5003.6
Exp/Cntr=0.3,0.1

Type RM Length L Ch R = 1 ,773     ,273,273,273
BEGIN DESCRIPTION:
Ashworth Creek Trib 5 1.5
END DESCRIPTION:
XS GIS Cut Line= 4
      1179860.83       537385.97      1179996.87       537226.03
      1180086.95       537150.65      1180283.66       537135.94
#Sta/Elev= 30
  4714.6  787.18  4727.7  786.78  4757.4  781.67  4795.5  777.25  4820.1  772.95
  4859.6  766.79  4873.9  765.94  4887.7  764.75  4890.9  764.06  4895.3  763.77
  4902.8  763.87  4921.9  762.99  4931.5  763.38  4984.3  763.33  4993.8   760.5
  4998.2  758.15  5001.8  758.15  5003.6   760.8  5005.3  762.56  5010.4  763.76
  5026.1  762.79  5050.9  762.57  5089.1  764.39    5121  769.37  5135.4   772.1
  5173.4  780.28  5203.7  784.32  5210.7  785.41  5221.8  787.78  5239.3  789.17
#Mann= 3 ,-1 , 0
  4714.6      .1       0  4993.8     .05       0  5003.6      .1       0
Bank Sta=4993.8,5003.6
Exp/Cntr=0.3,0.1

Type RM Length L Ch R = 1 ,500     ,273,273,273
BEGIN DESCRIPTION:
Ashworth Creek Trib 5 1.0
END DESCRIPTION:
XS GIS Cut Line= 3
      1179972.97         537579.      1180102.02       537425.63
      1180283.66       537270.15
#Sta/Elev= 30
  4799.6  791.92  4807.6  792.16  4830.5  787.54    4844   785.6  4847.8  784.36
  4891.4  778.56  4910.6  773.71  4925.7  770.86  4936.7  769.85  4956.6  765.36
  4972.5   762.8  4995.6   757.2  4998.2  754.77  5001.8  754.77  5005.1   757.3
  5008.4  758.47  5052.5  761.73  5062.8   761.3  5082.6  762.65  5095.5  764.22
  5105.3  765.87  5110.4  767.12  5118.9  768.65  5129.2   769.8  5159.1  777.36
  5172.5  778.73  5189.9  781.15  5199.4  782.92  5214.2  784.29  5239.1  787.42
#Mann= 3 ,-1 , 0
  4799.6      .1       0  4995.6     .05       0  5005.1      .1       0
Bank Sta=4995.6,5005.1
Exp/Cntr=0.3,0.1

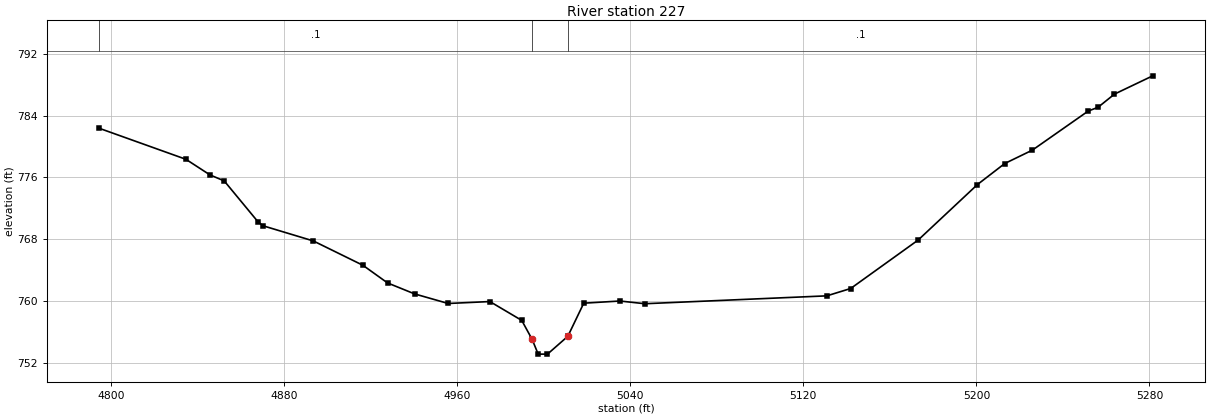
Type RM Length L Ch R = 1 ,227     ,0,0,0
BEGIN DESCRIPTION:
Ashworth Creek Trib 5 0.5
END DESCRIPTION:
XS GIS Cut Line= 4
      1180099.82       537691.15      1180259.76         537636.
      1180338.82       537580.84      1180419.71       537374.94
#Sta/Elev= 30
  4794.7  782.34  4834.7  778.33  4845.8  776.31  4852.4  775.53  4867.9  770.27
  4870.3  769.72  4893.6  767.75  4916.5   764.6  4927.9  762.31  4940.4  760.89
  4955.9  759.65 4975.18   759.9  4989.9  757.46  4994.7     755  4997.5  753.09
  5001.8  753.09  5011.2   755.4 5018.56  759.69 5035.29  759.97 5046.76  759.62
  5130.9  760.64  5141.9  761.59  5173.1  767.87  5200.5  775.06  5213.1  777.78
  5225.9  779.52  5251.7  784.58  5256.2  785.06  5263.8  786.77  5281.5  789.14
#Mann= 3 ,-1 , 0
  4794.7      .1       0  4994.7     .05       0  5011.2      .1       0
Bank Sta=4994.7,5011.2
Exp/Cntr=0.3,0.1

Chan Stop Cuts=-1
Use User Specified Reach Order=0
User Specified Reach Order=Ashworth Creek T,Reach-1