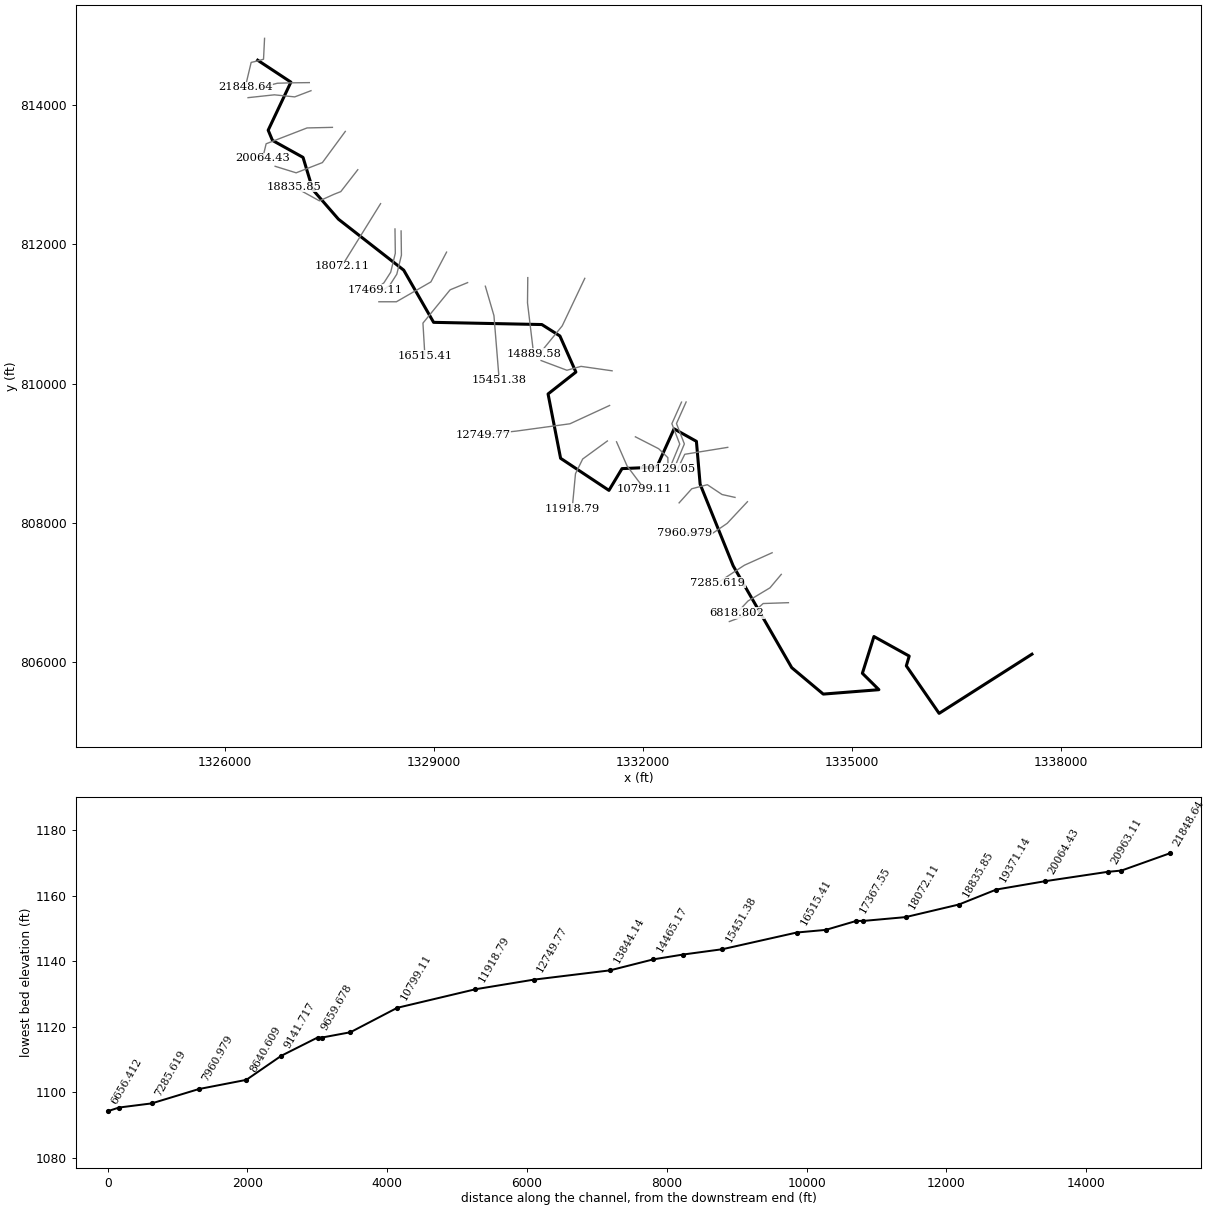
--- LambertCreek.prj (project) ---

Proj Title=LambertCreek
Current Plan=p01
Default Exp/Contr=0.3,0.1
English Units
Geom File=g01
Flow File=f01
Plan File=p01
Y Axis Title=Elevation
X Axis Title(PF)=Main Channel Distance
X Axis Title(XS)=Station
BEGIN DESCRIPTION:
END DESCRIPTION:
DSS File=dss
DSS Export Rating Curves= 0
DSS Export Rating Curve Sorted= 0
DSS Export Volume Flow Curves= 0
DXF OffsetX= 0
DXF OffsetY= 0
DXF ScaleX= 1
DXF ScaleY= 10

--- LambertCreek.p01 (plan) ---

Plan Title=Approximate Study - 100 YR
Program Version=3.12
Short Identifier=Approximate
Geom File=g01
Flow File=f01
Subcritical Flow
K Sum by GR= 0
Std Step Tol= 0.01
Critical Tol= 0.01
Num of Std Step Trials= 20
Max Error Tol= 0.3
Flow Tol Ratio= 0.001
Split Flow NTrial= 30
Split Flow Tol= 0.02
Split Flow Ratio= 0.02
Log Output Level= 0
Friction Slope Method= 1
Unsteady Friction Slope Method= 2
Unsteady Bridges Friction Slope Method= 1
Calc Critical at every XS
Parabolic Critical Depth
Global Vel Dist= 0 , 0 , 0
Global Log Level= 0
CheckData=True
Encroach Param=-1 ,0,0, 2
Encroach River=LambertCreek
Encroach Reach=Main
Encroach Node=21848.64
       1     350     435
Encroach Node=21160.65
       1  223.33     340
Encroach Node=20963.11
       1     315  395.68
Encroach Node=20064.43
       1  682.57  922.58
Encroach Node=19371.14
       1  712.48     789
Encroach Node=18835.85
       1  632.73  704.52
Encroach Node=18072.11
       1     530   674.4
Encroach Node=17469.11
       1     256     700
Encroach Node=17367.55
       1     327     640
Encroach Node=16930.38
       1     457     981
Encroach Node=16515.41
       1  585.62  843.16
Encroach Node=15451.38
       1     524  768.97
Encroach Node=14889.58
       1     650     730
Encroach Node=14465.17
       1   722.3     915
Encroach Node=13844.14
       1     501  661.47
Encroach Node=12749.77
       1  754.84 1037.45
Encroach Node=11918.79
       1  354.89  622.32
Encroach Node=10799.11
       1  361.26  416.38
Encroach Node=10129.05
       1     468     513
Encroach Node=9722.757
       1   347.6   458.4
Encroach Node=9659.678
       1  342.88     430
Encroach Node=9141.717
       1     420     509
Encroach Node=8640.609
       1     488     593
Encroach Node=7960.979
       1   577.1   645.9
Encroach Node=7285.619
       1   546.2     604
Encroach Node=6818.802
       1  524.44  593.38
Encroach Node=6656.412
       1     440   491.5
Encroach Node=6581.629
       1     408   458.1
Encroach Node=6340.874
       1     405  469.52
Encroach Node=5493.068
       1     497     556
Encroach Node=4750.177
       1  578.33     634
Encroach Node=3834.714
       1     396  472.74
Encroach Node=3313.427
       1  727.85  831.34
Encroach Node=2161.257
       1  1768.8    1870
Encroach Node=848.636
       1  728.02     850
Computation Interval=1HOUR
Output Interval=1HOUR
Run HTab= 0
Run UNet= 0
Run PostProcess= 0
UNET Theta= 1
UNET Theta Warmup= 1
UNET ZTol= 0.02
UNET ZSATol= 0.05
UNET MxIter= 20
UNET MaxInSteps= 0
UNET DtIC= 0
UNET DtMin= 0
UNET MaxCRTS= 20
UNET WFStab= 2
UNET SFStab= 1
UNET WFX= 1
UNET SFX= 1
UNET DSS MLevel= 4
UNET DZMax Abort= 100
UNET Convert EG Bridges=-1
UNET Use Existing IB Tables=-1
UNET Froude Reduction=False
UNET Froude Limit= 1
UNET Froude Power= 10
Instantaneous Interval=1HOUR
DSS File=dss
Write IC File= 0
Echo Input=False
Echo Output=False
Write Detailed= 0
Detailed Automatic Start=False, 10

--- LambertCreek.f01 (steady flow) ---

Flow Title=LambertCreek
Program Version=3.12
Number of Profiles= 2
Profile Names=P100yr,PFW
River Rch & RM=LambertCreek,Main            ,21848.64
    3040    3040
River Rch & RM=LambertCreek,Main            ,16930.38
    3510    3510
River Rch & RM=LambertCreek,Main            ,7285.619
    4150    4150
River Rch & RM=LambertCreek,Main            ,848.636
    4800    4800
Boundary for River Rch & Prof#=LambertCreek,Main            , 1
Up Type= 0
Dn Type= 3
Dn Slope=0.003914
DSS Import GetInterval= 0
DSS Import GetPeak= 0
DSS Import FillOption= 0

--- LambertCreek.g01 (geometry) ---

Geom Title=USGS 10m DEM
Program Version=3.12

River Reach=LambertCreek    ,Main
Reach XY= 30
  1326469.764483   814644.152139  1326946.751538   814329.687905
  1326620.501044   813639.561066  1326681.879626   813493.251965
  1327120.929582   813249.258489  1327261.250604   812785.381243
   1327629.00181   812362.190686  1328566.248529   811630.554985
  1328995.382321   810881.130372  1330549.630013   810849.501028
  1330808.628307   810685.378427  1331038.000205   810167.308126
  1330638.631995   809852.878723  1330818.499674   808929.439606
  1331512.628453   808468.750184  1331700.380756   808781.131655
  1332198.745157   808802.938759  1332447.530102   809351.938423
  1332768.248912   809172.684672  1332821.627991   808557.690745
  1333296.129114     807385.1288  1334136.501335   805923.880791
  1334589.379662   805544.189797  1335388.251217   805607.440244
  1335150.998607   805842.751326  1335317.001268   806370.750318
  1335823.250525   806089.940868  1335781.745716   805949.562756
   1336252.38022    805267.37805  1337585.378358   806117.060469

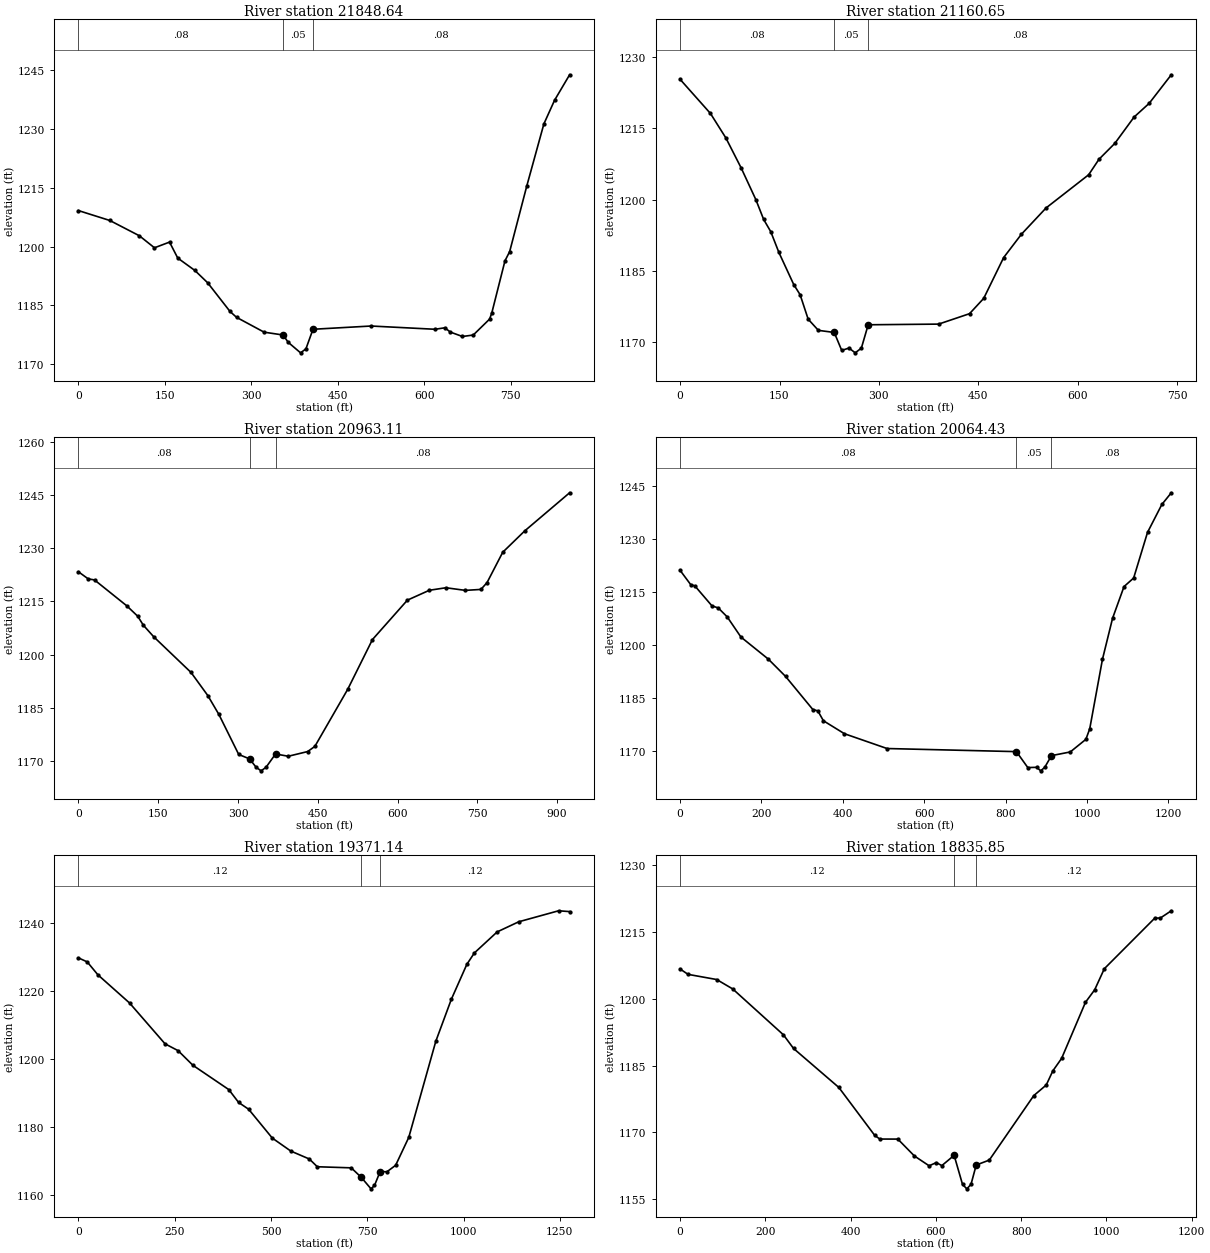
Type RM Length L Ch R = 1 ,21848.64,694.76,687.98,681.45
XS GIS Cut Line= 5
  1326568.487703   814958.410458   1326553.67525   814658.458092
  1326472.185316   814634.449574  1326376.168939   814612.934998
  1326290.753993   814254.818464
#Sta/Elev= 30
       0 1209.19   54.52 1206.66  105.63 1202.77  131.88  1199.7  158.03 1201.15
  172.26 1197.08  201.95 1193.92  224.12 1190.78  262.91 1183.46  274.29 1181.96
  322.04 1178.18  354.95 1177.46  363.76  1175.6  385.27 1172.91  394.54 1173.92
  406.79 1178.92  507.58 1179.75  618.55 1178.92  635.42  1179.3  645.02  1178.2
  665.98 1177.08  684.71 1177.45  712.99  1181.5  716.79 1183.02  739.75 1196.38
  747.88 1198.73  777.78 1215.58  807.21 1231.29  825.73 1237.32  851.83 1243.82
#Mann= 3 , 0 , 0
       0     .08       0  354.95     .05       0  406.79     .08       0
#XS Ineff= 2 , 0
       0                  507.58       0 1179.75
Permanent Ineff=
       F       F
Bank Sta=354.95,406.79
Exp/Cntr=0.3,0.1

Type RM Length L Ch R = 1 ,21160.65,200.92,197.54,193.58
XS GIS Cut Line= 4
  1327210.997183   814322.757375  1326946.751538   814319.501192
  1326751.856643   814313.719169  1326478.903039   814243.221216
#Sta/Elev= 30
       0 1225.36   45.81 1218.16    69.1 1212.99   92.18 1206.66  114.23 1200.01
  126.11  1195.8   136.8 1193.23  149.09 1188.84  171.48 1182.07   181.1 1179.93
  193.24 1174.77  208.67 1172.41  232.58 1171.97  243.88 1168.18  254.85 1168.68
  264.27 1167.67  273.53 1168.67  283.81 1173.59   390.1 1173.73  436.76 1175.93
  458.13 1179.16  488.23 1187.77  515.05 1192.69   552.2 1198.23  616.46 1205.23
  632.07  1208.5  656.09 1211.87     685  1217.4  707.77 1220.29  741.16 1226.32
#Mann= 3 , 0 , 0
       0     .08       0  232.58     .05       0  283.81     .08       0
Bank Sta=232.58,283.81
Exp/Cntr=0.3,0.1

Type RM Length L Ch R = 1 ,20963.11,873.54,898.69,897.74
XS GIS Cut Line= 4
  1327235.048542   814206.677934  1327001.752236   814117.803171
   1326709.20612   814147.428077  1326331.488273   814106.693797
#Sta/Elev= 30
       0 1223.35   18.42 1221.35   30.27 1221.05    91.1 1213.74  111.57 1210.82
  122.02 1208.31  141.61 1205.04  211.77 1194.99  243.22  1188.5  264.04 1183.19
  301.43 1171.89  321.86 1170.65  334.14 1168.28  343.57 1167.28   352.8 1168.28
  370.67 1172.03  394.69 1171.39  430.99 1172.71  444.58 1174.16  506.28 1190.22
   552.9 1204.26   618.6 1215.36  659.91 1218.14  691.08 1218.85  727.62 1218.11
  756.83 1218.38  768.31 1220.29  797.88 1228.85  839.28 1234.87   923.6  1245.6
#Mann= 3 , 0 , 0
       0     .08       0  321.86     .05       0  370.67     .08       0
Bank Sta=321.86,370.67
Exp/Cntr=0.3,0.1

Type RM Length L Ch R = 1 ,20064.43,690.41,693.29,693.15
XS GIS Cut Line= 4
  1327542.659359   813680.371109  1327178.571744   813672.096401
  1326591.066734   813444.541653   1326541.41844   813237.673674
#Sta/Elev= 30
       0  1221.1   25.88 1217.09   36.44 1216.68   78.26 1211.06   93.74 1210.47
  115.69 1207.95  149.49 1202.24  216.67 1196.01  259.08 1191.12  326.13 1181.75
  338.46 1181.36  352.14 1178.57  403.89  1174.9  508.49 1170.72  826.37 1169.84
  854.33 1165.34   876.1  1165.4  886.12 1164.41  896.03 1165.41  912.58 1168.71
  958.75 1169.75  997.03 1173.31 1006.53 1176.28 1037.86 1195.96 1062.65 1207.54
 1090.82 1216.51 1114.49 1218.93 1148.59 1231.84 1183.75 1239.72 1206.96 1243.03
#Mann= 3 , 0 , 0
       0     .08       0  826.37     .05       0  912.58     .08       0
Bank Sta=826.37,912.58
Exp/Cntr=0.3,0.1

Type RM Length L Ch R = 1 ,19371.14,532.53,535.28,535.8
XS GIS Cut Line= 4
  1327727.562979   813621.955949  1327398.726296    813174.61955
  1327022.027362   813027.680224  1326720.315448   813121.294674
#Sta/Elev= 30
       0 1229.65   22.88 1228.47   50.67 1224.67  132.71 1216.42  224.95 1204.43
  258.91 1202.42  297.43 1198.12  390.49    1191  415.98 1187.23  442.07 1185.23
  503.46 1176.77  551.55 1172.96  599.69 1170.63  620.33 1168.36  708.48 1168.04
  734.32 1165.27  759.78 1161.88  768.81 1162.86  783.49 1166.96  801.13 1166.89
  823.71 1168.79  857.83 1176.98  928.06  1205.2  968.36  1217.5  1008.6 1227.75
 1028.16  1231.1 1087.32 1237.27 1143.29 1240.24 1246.84 1243.47 1275.44 1243.23
#Mann= 3 , 0 , 0
       0     .12       0  734.32     .05       0  783.49     .12       0
Bank Sta=734.32,783.49
Exp/Cntr=0.3,0.1

Type RM Length L Ch R = 1 ,18835.85,745.49,763.75,781.96
XS GIS Cut Line= 5
  1327906.746975   813072.179329  1327662.642764   812757.740008
   1327567.48353   812720.503775  1327356.478198   812625.344494
  1326988.253228   812828.075118
#Sta/Elev= 30
       0 1206.72   18.65 1205.51    85.8 1204.35   123.5 1202.23  242.38 1191.92
  266.03 1188.86  372.28  1180.1  456.56 1169.31  468.58  1168.5  510.67 1168.49
  549.49  1164.7  584.07 1162.49  601.01 1163.21  613.92 1162.53  642.73 1164.84
  662.43  1158.3  672.58 1157.31  682.29 1158.31  694.52 1162.66  725.17 1163.77
   829.6 1178.27  858.78 1180.64   874.2 1183.81  894.86 1186.63  950.83 1199.24
  972.39 1202.04  995.04 1206.78 1113.16 1218.13 1126.56 1218.18 1152.07  1219.8
#Mann= 3 , 0 , 0
       0     .12       0  642.73     .05       0  694.52     .12       0
Bank Sta=642.73,694.52
Exp/Cntr=0.3,0.1

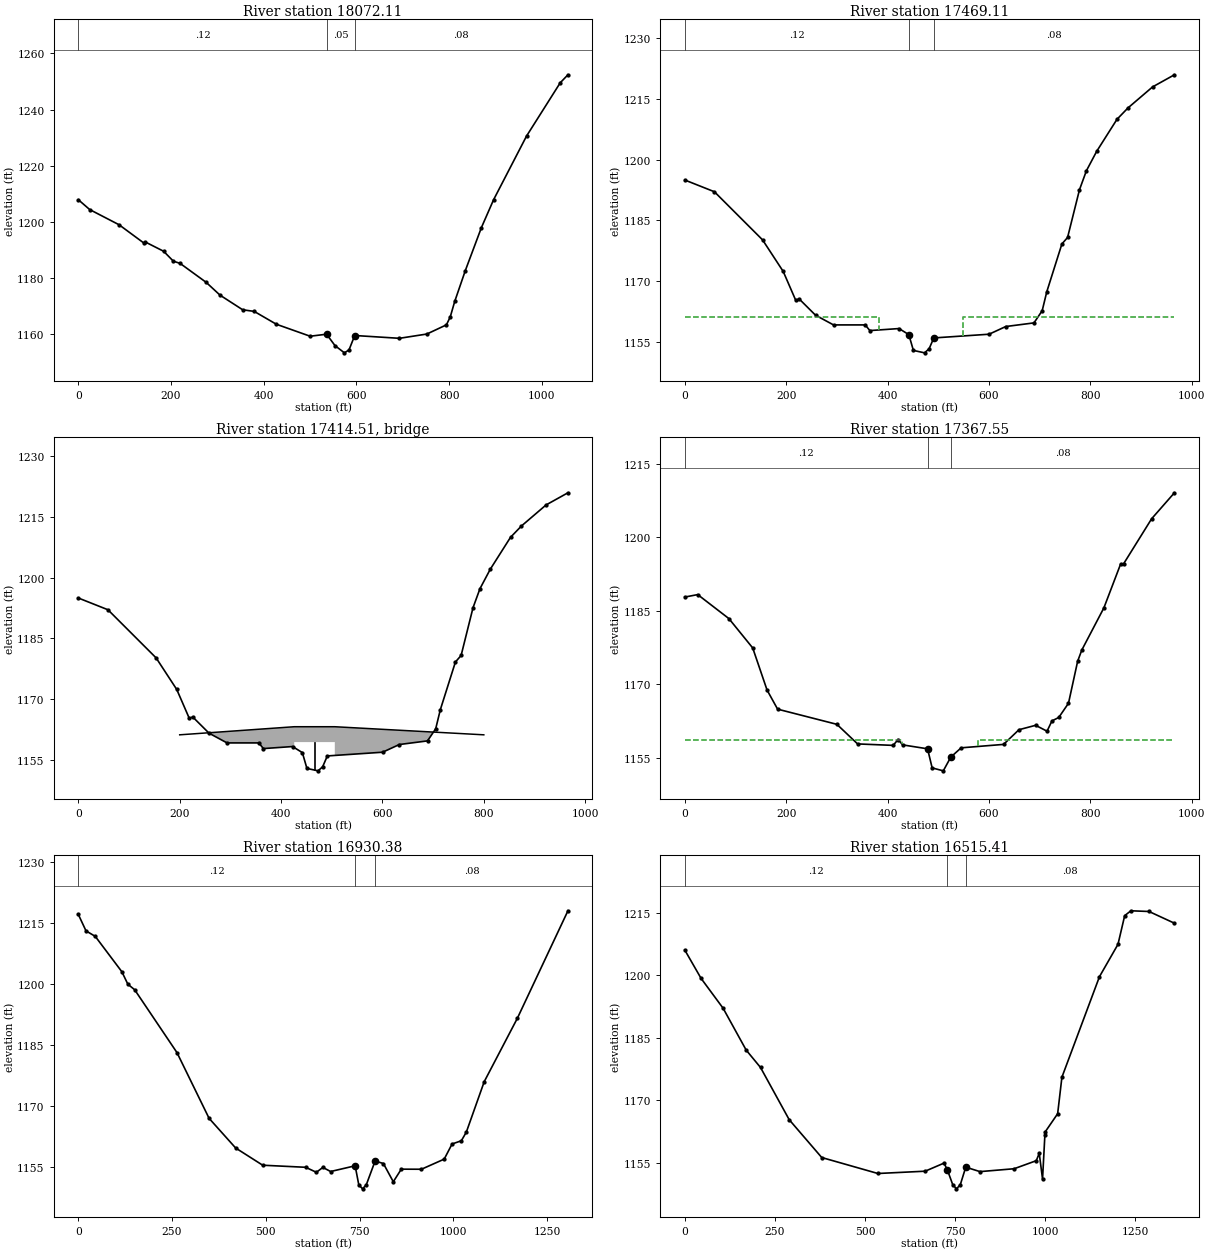
Type RM Length L Ch R = 1 ,18072.11,592.3,603,613.26
XS GIS Cut Line= 2
  1328234.149236   812585.083466  1327677.200594   811687.448178
#Sta/Elev= 30
       0 1207.95   24.48 1204.45   88.08 1199.02  141.31 1192.54   144.8 1192.88
     184 1189.61  205.08 1186.07  219.48  1185.3  275.71 1178.56  305.76 1173.98
  354.64 1168.78  379.43 1168.21  427.32 1163.63  500.16 1159.37  535.63 1160.09
  553.65 1156.05  574.05 1153.46     584  1154.5  596.35 1159.63  692.79 1158.63
  751.95 1160.15  794.17 1163.42  802.51 1166.28  812.09 1171.75  834.94 1182.72
  869.69 1198.04  895.91 1207.93  966.97 1230.58 1039.81 1249.58 1056.38 1252.41
#Mann= 3 , 0 , 0
       0     .12       0  535.63     .05       0  596.35     .08       0
Bank Sta=535.63,596.35
Exp/Cntr=0.5,0.3

Type RM Length L Ch R = 1 ,17469.11,101.56,101.56,101.56
BEGIN DESCRIPTION:
Upstream xs of Bridge 37003-0010
END DESCRIPTION:
XS GIS Cut Line= 5
  1328440.931253    812221.58561  1328445.671219   811873.196461
  1328379.311366   811600.647144  1328282.141638   811448.967526
  1328158.901911   811351.797752
#Sta/Elev= 30
       0    1195    58.4  1192.1   153.5  1180.2   194.2  1172.4   218.8  1165.3
   225.8  1165.6   257.9  1161.6   293.4  1159.2     356  1159.2   365.1  1157.8
   422.7  1158.3     442  1156.8     451  1152.9     473  1152.3     482  1153.3
  491.281155.983   600.3  1156.9   633.3  1158.8   688.9  1159.7   705.1  1162.7
   714.2  1167.4     744  1179.2   755.2  1180.8   778.7  1192.6   792.4  1197.3
   812.7  1202.1   852.7    1210   874.3  1212.8   922.9    1218     966    1221
#Mann= 3 , 0 , 0
       0     .12       0     442     .05       0  491.28     .08       0
#XS Ineff= 2 , 0
       0   383.4  1161.1   548.6       0  1161.1
Permanent Ineff=
       F       F
Bank Sta=442,491.28
Exp/Cntr=0.5,0.3

Type RM Length L Ch R = 3 ,17414.51,,,
BEGIN DESCRIPTION:
All Healing Springs Road, SR 1307; Bridge : 37003-0010
END DESCRIPTION:
Bridge Culvert--1,0,-1,-1, 0
Deck Dist Width WeirC Skew NumUp NumDn MinLoCord MaxHiCord MaxSubmerge Is_Ogee
42.6,24,2.6,0, 6, 6, , , 0.95, 0, 0,0,,
     200     426     426     506     506     800
  1161.2  1163.2  1163.2  1163.2  1163.2  1161.2
                  1159.4  1159.4
     200     463     463     543     543     800
  1161.2  1163.2  1163.2  1163.2  1163.2  1161.2
                  1159.4  1159.4
Pier Skew, UpSta & Num, DnSta & Num=  ,466, 2 ,503, 2 , 0 , 0 , 0 ,,
       1       1
    1154  1159.9
       1       1
    1154  1159.9
Abutment Skew #Up #Dn= , 2 , 3
     426     442
  1158.8  1156.8
     463  467.81     479
  1158.8  1158.4  1156.8
Abutment Skew #Up #Dn= , 2 , 2
  491.28     506
 1155.98  1159.2
   524.8     543
  1155.1  1159.2
BR Coef=-1 , 1 , 0 ,, 0 ,,,0.8,0,2,0,
WSPro=,,,, 1 ,,,, 0 ,,,, 0 ,,,,-1 ,-1 ,-1 , 0 , 0 , 0 , 0 , 0
BC Design=,, 0 ,, 0 ,,,,,,

Type RM Length L Ch R = 1 ,17367.55,462.36,437.17,411.84
BEGIN DESCRIPTION:
Down stream xs of Bridge 37003-0010
END DESCRIPTION:
XS GIS Cut Line= 5
  1328528.621001   812193.145673  1328533.361014   811844.756524
   1328467.00116   811572.207207  1328369.831387   811420.527588
  1328246.591705   811323.357815
#Sta/Elev= 30
       0  1187.8    25.5  1188.3      87  1183.4     134  1177.4   162.3  1168.8
   183.1  1164.9   300.1  1161.8   340.9  1157.8   411.1  1157.5   420.8  1158.7
   429.9  1157.6     479  1156.8     488  1152.9     510  1152.3   524.81155.102
   545.2    1157   628.9  1157.7   659.3  1160.7   692.1  1161.6   714.7  1160.4
   724.4  1162.5   737.8  1163.2     757  1166.1   775.1  1174.7   783.4    1177
   826.9  1185.6   859.7  1194.5   865.8  1194.6   921.1  1203.8     966  1209.1
#Mann= 3 , 0 , 0
       0     .12       0     479     .05       0   524.8     .08       0
#XS Ineff= 2 , 0
       0     428  1158.5     578       0  1158.5
Permanent Ineff=
       F       F
Bank Sta=479,524.8
Exp/Cntr=0.5,0.3

Type RM Length L Ch R = 1 ,16930.38,403.48,414.97,425.91
XS GIS Cut Line= 4
  1329181.400967   811889.234627  1328956.322279   811461.585084
  1328461.149148   811176.485404  1328209.811262   811176.485404
#Sta/Elev= 30
       0 1217.04   20.49    1213   45.12 1211.66  116.14 1202.95  132.09 1199.89
  150.33 1198.52  263.15 1183.06  348.77  1166.9  419.67  1159.6  491.77 1155.37
  606.29 1154.86  634.99 1153.63  652.27 1154.83  672.95 1153.82  738.35 1155.23
  748.06 1150.56  758.18 1149.56  768.11 1150.56   791.6  1156.4  813.72 1155.79
  840.14  1151.3  861.48  1154.4  915.21 1154.38  975.92 1156.87  996.91 1160.59
  1021.7 1161.39 1035.06 1163.54 1082.67 1175.92 1171.04 1191.51 1305.99 1217.95
#Mann= 3 , 0 , 0
       0     .12       0  738.35     .05       0   791.6     .08       0
Bank Sta=738.35,791.6
Exp/Cntr=0.3,0.1

Type RM Length L Ch R = 1 ,16515.41,1037.23,1064.03,1085.96
XS GIS Cut Line= 4
  1329483.373185   811451.503424  1329232.532997   811347.982077
   1328842.33715   810870.191244  1328870.208282   810400.363591
#Sta/Elev= 30
       0 1206.02   45.23 1199.22  106.37 1192.06  170.38 1182.03  210.16 1177.86
  289.77 1165.34  380.06 1156.27  535.86 1152.44  667.13 1152.99   719.4 1154.93
  728.79  1153.3  743.57 1149.77  754.08 1148.76  764.65 1149.75  779.76 1153.96
  819.23 1152.89  914.01 1153.58  975.49 1155.51  983.74 1157.28  992.89 1151.11
  999.39 1161.67 1000.73 1162.48 1034.81 1166.77 1046.65 1175.53 1150.93 1199.65
 1202.26 1207.39 1220.88 1214.27 1238.17 1215.44 1288.42 1215.27 1358.89 1212.46
#Mann= 3 , 0 , 0
       0     .12       0  728.79     .05       0  779.76     .08       0
#XS Ineff= 2 , 0
       0                  983.74       0 1157.28
Permanent Ineff=
       F       F
Bank Sta=728.79,779.76
Exp/Cntr=0.3,0.1

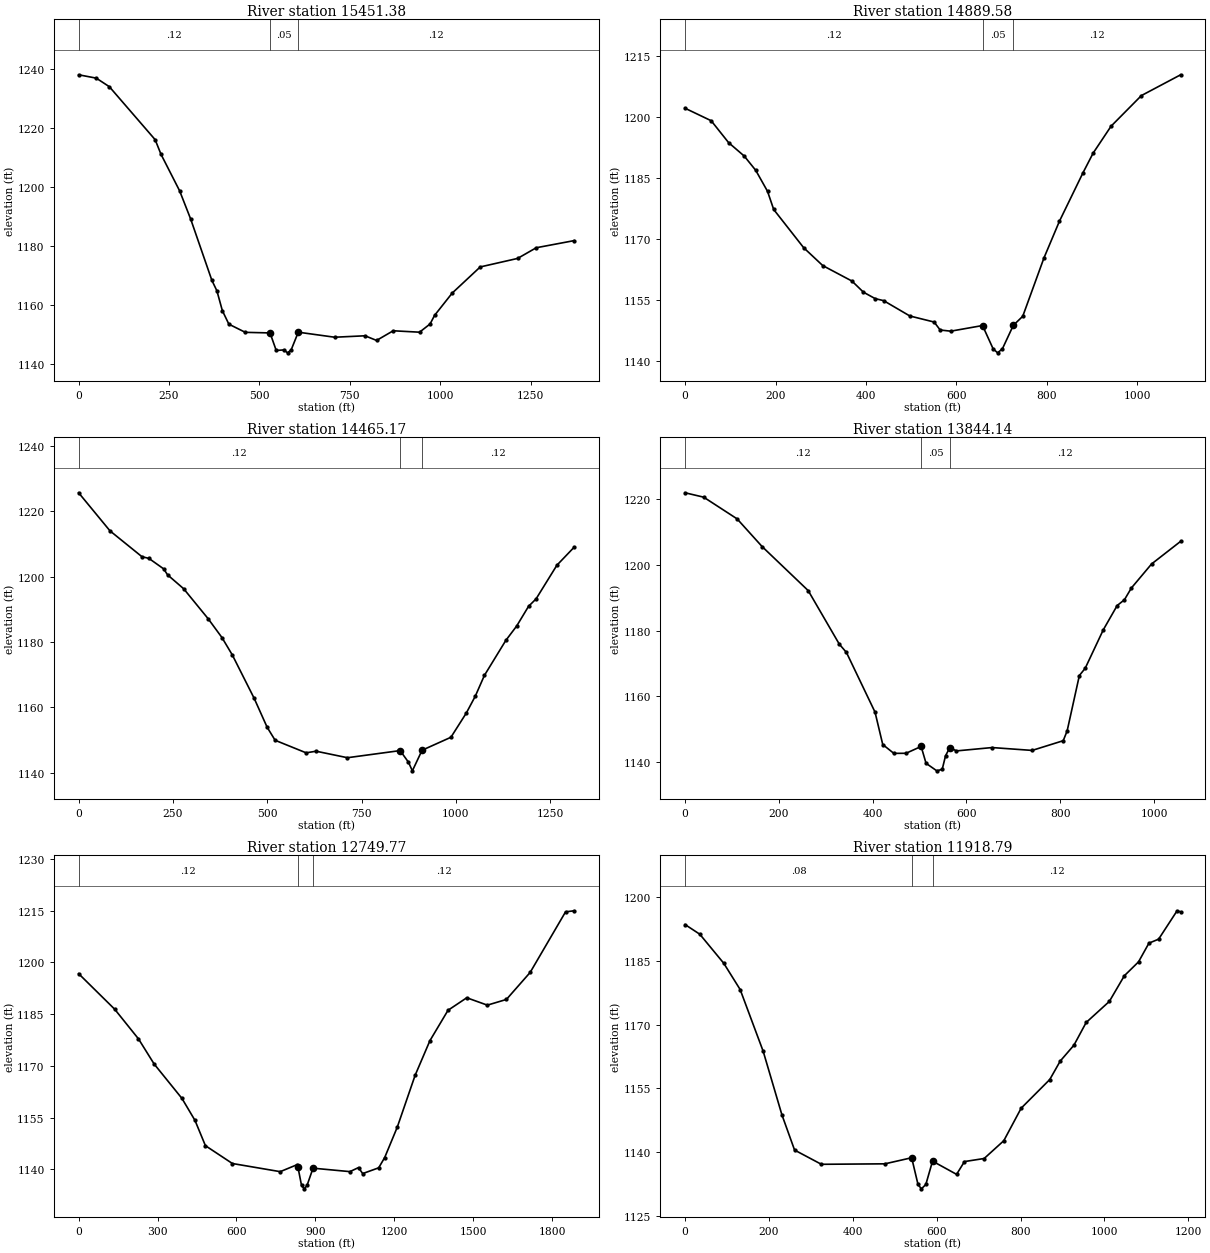
Type RM Length L Ch R = 1 ,15451.38,549.45,561.8,559.24
XS GIS Cut Line= 3
  1329738.194963    811399.74275  1329861.624261   810977.694181
  1329937.274476   810049.983647
#Sta/Elev= 30
       0 1238.06    48.7 1236.92   84.97 1234.01  211.58 1216.03  227.87 1211.05
  279.36 1198.65  309.75 1189.12  368.42  1168.3  382.45  1164.7  397.49 1157.99
   415.5 1153.39  461.01 1150.62  529.42 1150.42   546.5 1144.46  567.85 1144.66
  577.75 1143.66  587.77 1144.65  607.45 1150.67  708.15 1148.96  792.03 1149.45
  824.02 1147.87     870 1151.15   942.9 1150.67  972.01 1153.46  984.45 1156.38
 1033.23 1163.95 1110.69 1172.82 1214.03 1175.71 1265.65 1179.34 1370.52 1181.76
#Mann= 3 , 0 , 0
       0     .12       0  529.42     .05       0  607.45     .12       0
Bank Sta=529.42,607.45
Exp/Cntr=0.3,0.1

Type RM Length L Ch R = 1 ,14889.58,448.66,424.4,399.61
XS GIS Cut Line= 3
  1330347.378275   811523.172049  1330343.396685   811160.847334
  1330430.991671   810432.216313
#Sta/Elev= 30
       0 1202.23   57.73 1199.16   96.26 1193.77   130.8 1190.47  156.29 1186.95
   182.3  1181.8  195.99 1177.32  262.31 1167.91  304.54 1163.51  369.17  1159.7
  394.46 1156.97  420.54 1155.38  439.11 1154.89  497.17 1151.11  550.89 1149.62
  564.29 1147.66  587.68 1147.37  657.97 1148.76  681.31 1143.05  691.26 1142.04
  701.94 1143.03  726.15 1148.82  746.95 1151.04  793.95 1165.42  828.04 1174.42
  880.01 1186.31  902.58 1191.18  942.28 1197.81  1009.4 1205.35 1096.22 1210.47
#Mann= 3 , 0 , 0
       0     .12       0  657.97     .05       0  726.15     .12       0
Bank Sta=657.97,726.15
Exp/Cntr=0.3,0.1

Type RM Length L Ch R = 1 ,14465.17,638.35,621.03,599
XS GIS Cut Line= 3
   1331165.59503   811512.720374  1330842.090867    810830.87304
   1330488.72473   810397.875097
#Sta/Elev= 30
       0 1225.73   83.17 1214.06  167.88 1206.15  186.18 1205.64  225.35 1202.43
  235.82 1200.59  278.41 1196.34  343.38 1187.15  379.98 1181.38  407.46 1176.05
   465.4 1162.76  499.64 1153.93  520.87 1149.93  602.97 1146.09  629.51 1146.58
   712.6 1144.59  852.22 1146.77  874.25 1143.23  884.69 1140.57  910.39 1146.88
  986.87 1150.85 1027.61 1158.26 1051.41 1163.42 1075.69 1169.81 1132.32  1180.5
 1161.17 1184.92 1192.76 1190.97 1212.52 1193.22  1267.8 1203.54 1313.59 1209.07
#Mann= 3 , 0 , 0
       0     .12       0  852.22     .05       0  910.39     .12       0
Bank Sta=852.22,910.39
Exp/Cntr=0.3,0.1

Type RM Length L Ch R = 1 ,13844.14,1096.23,1094.37,1082.36
XS GIS Cut Line= 4
  1331557.781672   810185.357716  1331111.843561    810249.06316
  1330908.782504   810193.320897  1330538.494608   810332.676556
#Sta/Elev= 30
       0 1222.01   39.64 1220.67  110.93 1214.05  164.12 1205.62  262.48 1192.18
   328.8 1175.85  344.06 1173.31  405.02 1155.11  421.47 1145.23  445.11 1142.54
  471.09 1142.56  503.32 1144.65   513.8 1139.51  536.74 1137.21  548.28 1137.68
   555.4 1141.81  564.47 1144.31  578.68 1143.29  654.65 1144.31  740.01 1143.44
  806.28  1146.4  814.65 1149.38  840.72 1166.28  853.16 1168.49  891.68  1180.2
  921.38 1187.63  936.77 1189.37  951.65 1192.97  994.73  1200.3 1056.68  1207.2
#Mann= 3 , 0 , 0
       0     .12       0  503.32     .05       0  564.47     .12       0
Bank Sta=503.32,564.47
Exp/Cntr=0.3,0.1

Type RM Length L Ch R = 1 ,12749.77,793.08,830.98,856.57
XS GIS Cut Line= 4
   1331521.94736   809687.658931  1330952.579997   809424.873973
  1330183.353557   809319.979437  1329705.239741   809267.347325
#Sta/Elev= 30
       0 1196.72  137.22 1186.41  227.63 1177.82  287.04 1170.55  392.96 1160.56
   442.5 1154.19  482.15 1146.87  584.75  1141.7  766.57 1139.34  829.82 1141.33
  833.92  1140.7  847.59 1135.36  858.05 1134.36  868.68 1135.37  891.35 1140.35
 1031.63 1139.35 1064.28 1140.52 1080.15 1138.78 1141.01 1140.45 1163.86 1143.43
 1211.69 1152.23 1279.58 1167.26 1335.91 1177.31 1404.69 1186.11 1475.97 1189.74
 1554.22  1187.6 1626.69 1189.25 1717.04 1197.08 1851.66 1214.64 1884.43 1214.95
#Mann= 3 , 0 , 0
       0     .12       0  833.92     .05       0  891.35     .12       0
Bank Sta=833.92,891.35
Exp/Cntr=0.3,0.1

Type RM Length L Ch R = 1 ,11918.79,1086.42,1119.68,1148.6
XS GIS Cut Line= 4
  1331490.094638   809178.015376  1331135.733103   808919.212008
  1331032.211756   808708.187723  1330984.432719   808202.525758
#Sta/Elev= 30
       0 1193.46   35.03  1191.2   92.21 1184.38  131.28 1178.22  186.27 1163.71
  230.86 1148.82  261.08 1140.54  324.98  1137.2  476.53 1137.31  540.33 1138.74
  555.46 1132.46   563.6 1131.44   574.1 1132.46   590.1 1137.94  647.43 1134.84
  666.23 1137.84  713.22 1138.56  760.07 1142.74  801.47 1150.37  869.71  1157.1
  894.65 1161.43  927.34 1165.16  956.45 1170.48 1011.78 1175.43 1047.59 1181.46
 1081.34 1184.71 1106.15  1189.1 1129.26 1190.04 1173.31  1196.7 1181.77 1196.44
#Mann= 3 , 0 , 0
       0     .08       0  540.33     .05       0   590.1     .12       0
Bank Sta=540.33,590.1
Exp/Cntr=0.3,0.1

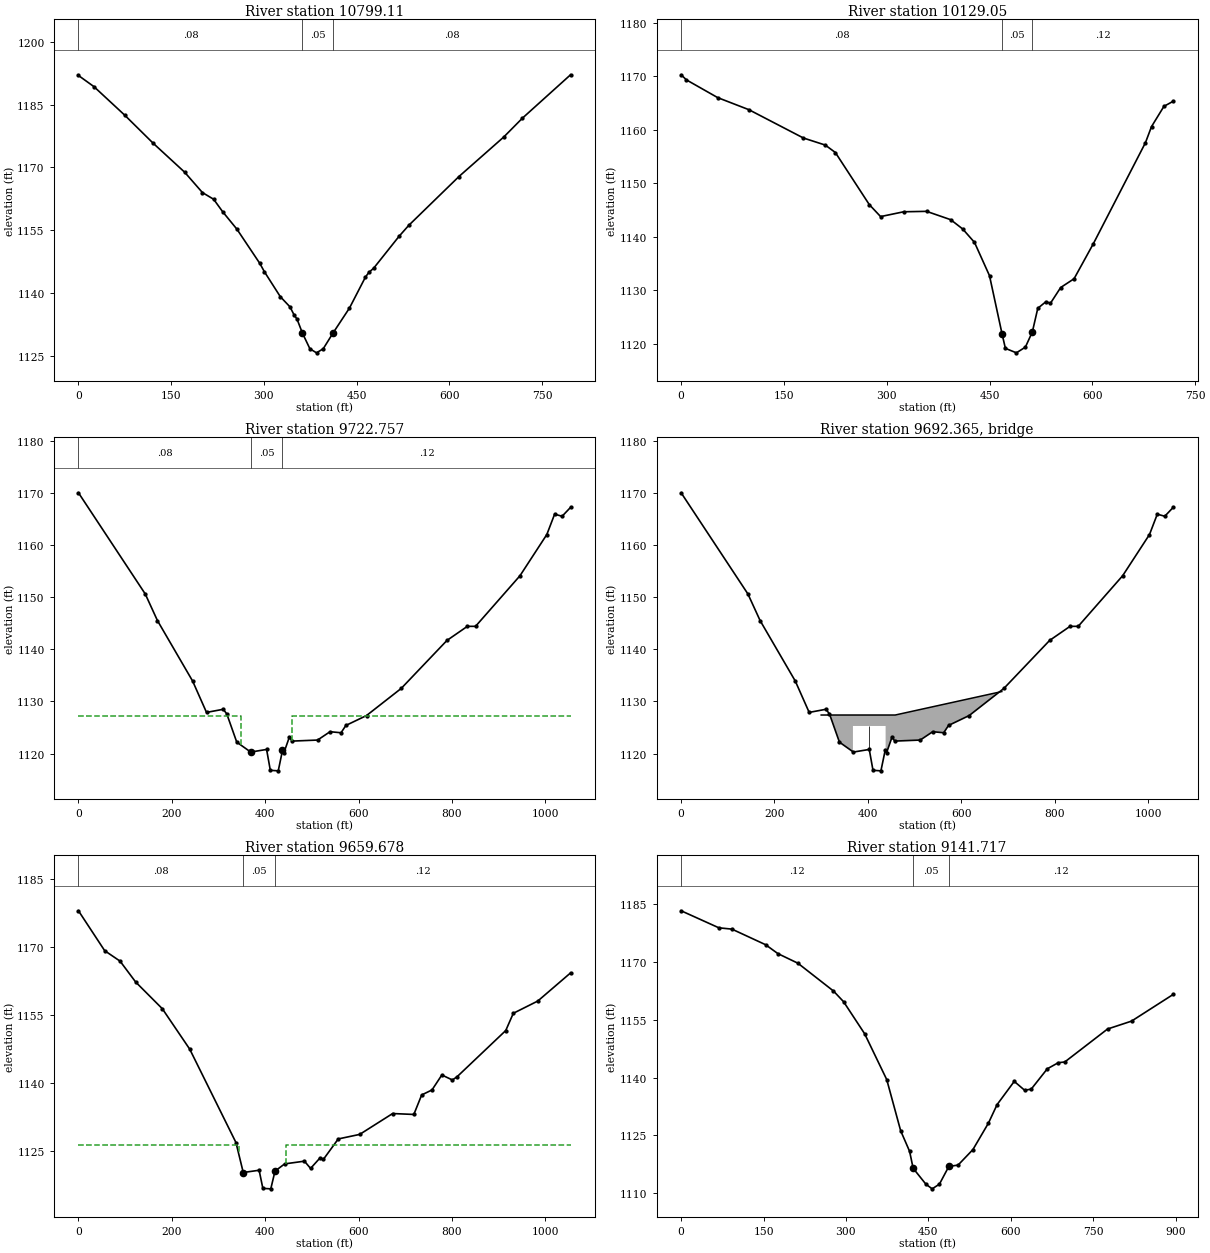
Type RM Length L Ch R = 1 ,10799.11,662.4,670.06,671.34
XS GIS Cut Line= 3
  1331621.487117   809166.070605  1331772.787547   808819.672251
  1332023.627735   808485.218668
#Sta/Elev= 30
       0 1191.94   25.07 1189.28   74.94 1182.46  120.77 1175.79   171.7 1168.88
  200.54 1164.01   218.7 1162.41  233.43 1159.41  256.36 1155.27  293.37 1147.11
  300.75 1145.13  326.55 1139.17  342.25 1136.73  348.88 1134.79  353.56 1133.83
  362.23 1130.51  374.38 1126.75  385.11 1125.77  395.95 1126.74   412.1 1130.56
  438.41 1136.45  464.32 1143.86  469.77 1144.95  477.67 1145.98  518.69 1153.58
  534.37 1156.19  615.58 1167.84  688.08 1177.27  718.22 1181.76  796.07 1192.11
#Mann= 3 , 0 , 0
       0     .08       0  362.23     .05       0   412.1     .08       0
Bank Sta=362.23,412.1
Exp/Cntr=0.3,0.1

Type RM Length L Ch R = 1 ,10129.05,414.97,406.29,394.91
XS GIS Cut Line= 4
  1331892.235256    809237.73923  1332226.688839   809066.530848
  1332358.081318   808939.119959  1332362.062908   808779.856348
#Sta/Elev= 30
       0 1170.29    7.69 1169.34   53.35 1166.02   98.95 1163.76  178.44 1158.47
  210.33 1157.15  225.06 1155.76  274.58 1146.02  291.08 1143.78  324.81 1144.68
  358.14 1144.76  393.36  1143.2  410.91 1141.46  428.08 1138.96  449.99 1132.73
  468.27 1121.87  473.16 1119.15  489.23 1118.31  502.36 1119.38  512.55 1122.24
  520.43 1126.63  532.39 1127.88   538.9 1127.57  553.84 1130.52  573.38 1132.16
  601.64 1138.74  677.53 1157.59   686.4  1160.6  704.52 1164.39  718.06 1165.34
#Mann= 3 , 0 , 0
       0     .08       0  468.27     .05       0  512.55     .12       0
Bank Sta=468.27,512.55
Exp/Cntr=0.5,0.3

Type RM Length L Ch R = 1 ,9722.757,62.86,63.08,167.49
BEGIN DESCRIPTION:
Upstream xs of Bridge 37033-0013
END DESCRIPTION:
XS GIS Cut Line= 4
  1332554.294966   809735.836667  1332415.889721   809426.244927
  1332528.951816   809133.449775  1332374.943519   808763.050074
#Sta/Elev= 30
       0    1170   143.1  1150.6   169.2  1145.5   244.6  1133.9   274.3  1127.9
   310.2  1128.5   317.8  1127.6   339.1  1122.2     369  1120.3     403  1120.8
     411  1116.8     428  1116.7     437  1120.6   440.2  1120.2   451.9  1123.2
   457.4  1122.4   512.2  1122.6   538.9  1124.2   562.5    1124   572.8  1125.4
   617.1  1127.3   691.4  1132.5   789.4  1141.7   833.1  1144.4   850.6  1144.4
   945.8  1154.1  1003.3    1162    1020  1165.9    1036  1165.5  1054.1  1167.2
#Mann= 3 , 0 , 0
       0     .08       0     369     .05       0     437     .12       0
#XS Ineff= 2 , 0
       0   347.6  1127.2   458.4       0  1127.2
Permanent Ineff=
       F       F
Bank Sta=369,437
Exp/Cntr=0.5,0.3

Type RM Length L Ch R = 3 ,9692.365,,,
BEGIN DESCRIPTION:
Chapman Mill Road, SR 1315; Bridge : 37033-0013
END DESCRIPTION:
Bridge Culvert--1,0,-1,-1, 0
Deck Dist Width WeirC Skew NumUp NumDn MinLoCord MaxHiCord MaxSubmerge Is_Ogee
20.4,20,2.6,0, 9, 9, , , 0.95, 0, 0,0,,
     300   363.4     368     368     438     438   446.6   458.5     687
  1127.4  1127.4  1127.4  1127.4  1127.4  1127.4  1127.4  1127.4  1131.9
                          1125.3  1125.3
     300     346     352     352     422     422   429.1   441.1   678.2
  1127.4  1127.4  1127.4  1127.4  1127.4  1127.4  1127.4  1127.4  1132.7
                          1125.3  1125.3
Pier Skew, UpSta & Num, DnSta & Num=  ,403, 2 ,387, 2 , 0 , 0 , 0 ,,
       1       1
  1119.8  1125.8
       1       1
  1119.8  1125.8
BR Coef=-1 , 1 , 0 ,, 0 ,,,0.8,0,2,0,
WSPro=,,,, 1 ,,,, 0 ,,,, 0 ,,,,-1 ,-1 ,-1 , 0 , 0 , 0 , 0 , 0
BC Design=,, 0 ,, 0 ,,,,,,

Type RM Length L Ch R = 1 ,9659.678,569.47,517.96,356.95
BEGIN DESCRIPTION:
Down stream xs of Bridge 37033-0013
END DESCRIPTION:
XS GIS Cut Line= 4
  1332620.577007   809737.786112  1332482.171809   809428.194418
  1332595.233904   809135.399219  1332441.225607   808764.999518
#Sta/Elev= 30
       0    1178    56.2  1169.2    89.1  1166.9   122.5  1162.3   179.7  1156.4
   238.3  1147.5   337.4  1126.9     353  1120.3     387  1120.8     395  1116.8
     412  1116.7     421  1120.6   441.7  1122.2   484.1  1122.8   497.2  1121.2
   517.3  1123.5   524.7  1123.2   556.5  1127.7   602.4  1128.7     673  1133.3
   718.4  1133.1   735.2  1137.4   757.3  1138.5   778.4  1141.8     801  1140.7
   810.9  1141.4   915.3  1151.6   931.5  1155.4   983.9  1158.1  1054.1  1164.3
#Mann= 3 , 0 , 0
       0     .08       0     353     .05       0     421     .12       0
#XS Ineff= 2 , 0
       0  342.87  1126.4   444.7       0  1126.4
Permanent Ineff=
       F       F
Bank Sta=353,421
Exp/Cntr=0.5,0.3

Type RM Length L Ch R = 1 ,9141.717,498.89,501.11,503.2
XS GIS Cut Line= 3
  1333218.104818     809086.4388  1332600.958325   808986.899043
  1332481.510617   808744.022036
#Sta/Elev= 30
       0 1183.28   68.72 1178.86   92.46 1178.52  153.72 1174.48  176.22 1172.16
  212.53 1169.68  277.28 1162.47  295.73 1159.69  334.05 1151.38   374.3 1139.48
  399.66  1126.2  415.94 1120.86  422.32 1116.48  445.55 1112.35  456.99 1111.14
  470.19 1112.36  487.31 1116.95  504.14  1117.3  531.19 1121.33  559.46  1128.2
  575.16 1132.99  606.41 1139.02  625.12 1136.74  637.19 1136.99  666.55 1142.28
  686.62 1143.87  698.34 1144.05  776.21  1152.6  819.86 1154.65  895.78 1161.58
#Mann= 3 , 0 , 0
       0     .12       0  422.32     .05       0  487.31     .12       0
Bank Sta=422.32,487.31
Exp/Cntr=0.3,0.1

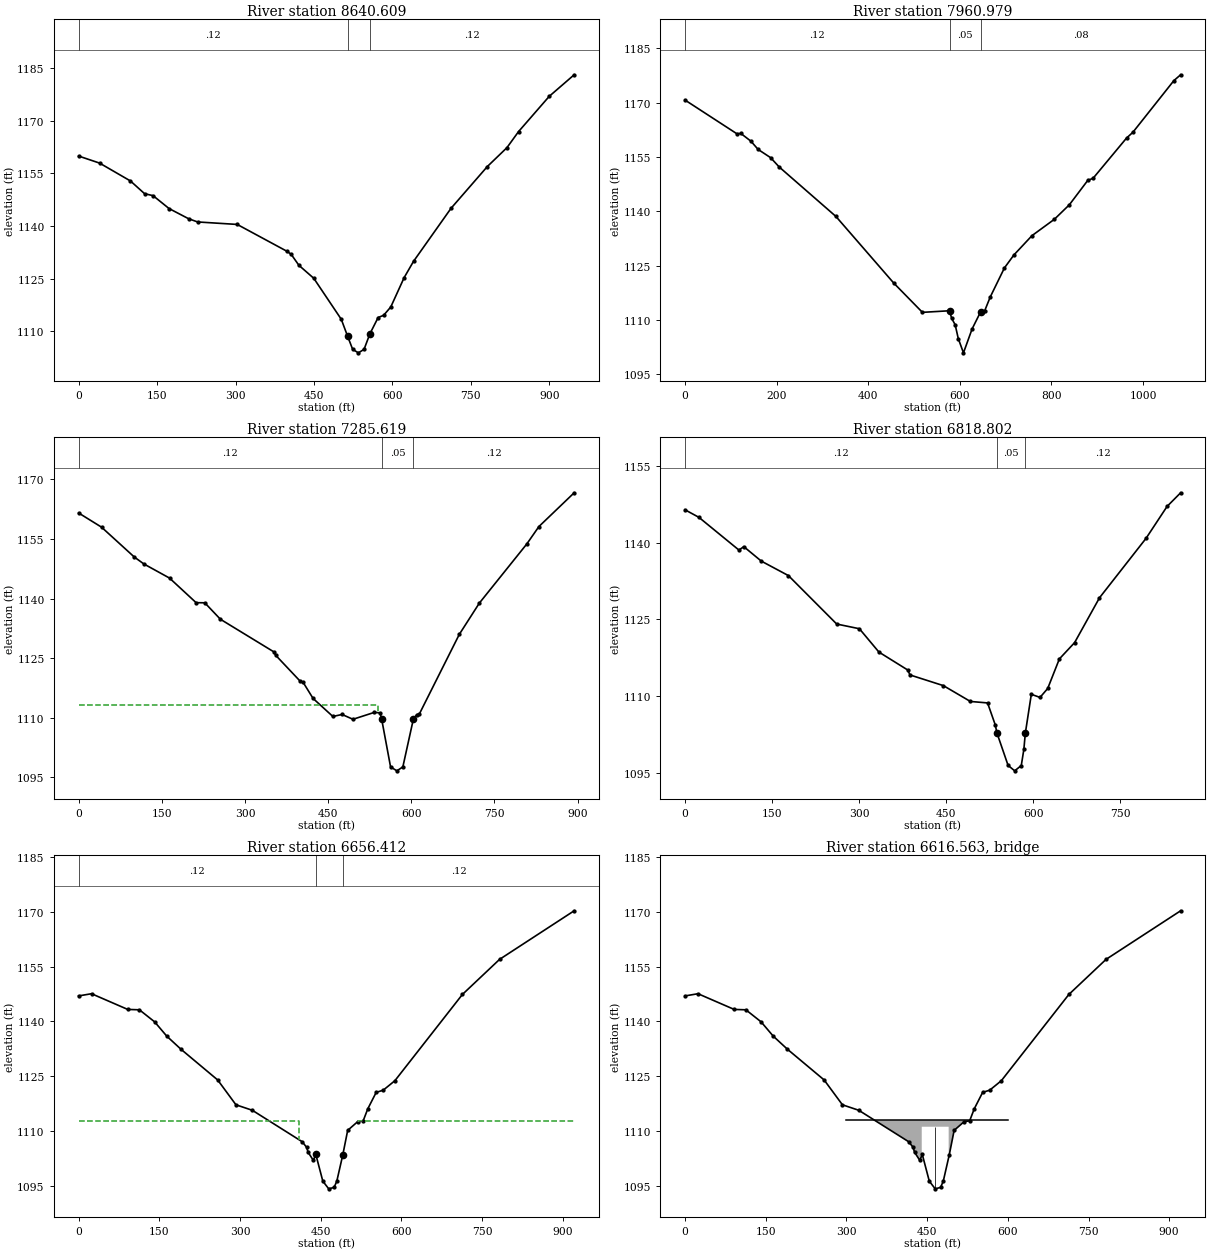
Type RM Length L Ch R = 1 ,8640.609,668.98,679.63,689.95
XS GIS Cut Line= 5
   1333322.55013   808368.001943  1333136.368968   808409.375529
  1332925.363636   808550.045751  1332701.946242   808492.122702
  1332519.902434   808289.392124
#Sta/Elev= 30
       0 1159.98   40.04 1157.97   99.04 1152.87  126.13 1149.23  142.33 1148.67
  172.89 1144.99  210.17 1142.09  227.49 1141.16  303.26 1140.45  398.14  1132.8
  406.43 1131.92  421.19 1128.78  449.65 1125.07  502.25 1113.36   514.4 1108.49
  524.05 1104.77  534.95 1103.78  545.82 1104.78  556.83 1109.17  572.73 1113.87
  583.23  1114.5  596.94 1116.89  622.48 1125.27  640.35  1129.9  712.09 1145.05
   781.5 1156.98  819.05 1162.38  841.27 1166.97     900 1177.05  947.59 1183.19
#Mann= 3 , 0 , 0
       0     .12       0   514.4     .05       0  556.83     .12       0
Bank Sta=514.4,556.83
Exp/Cntr=0.3,0.1

Type RM Length L Ch R = 1 ,7960.979,674.2,675.36,674.17
XS GIS Cut Line= 4
  1333500.797727   808306.047105  1333210.141637   807995.483064
  1332971.246221   807832.237863  1332604.939915   807860.108994
#Sta/Elev= 30
       0 1170.69  113.05 1161.41   121.8 1161.49  143.73 1159.36  159.48 1157.08
  186.77 1154.81  205.34 1152.26  329.24 1138.61  455.52 1120.23   518.2 1112.14
   577.4 1112.58  582.13 1110.47  589.73 1108.72  596.54 1104.89  607.86 1100.97
  626.68 1107.56  645.57 1112.35  654.16 1112.56  666.33 1116.38   697.3  1124.4
  718.09 1127.99  757.45  1133.3  806.41 1137.82   839.1 1141.82  879.42 1148.57
   890.8 1149.11  963.92 1160.22  977.82 1161.82 1067.35 1176.08 1082.07 1177.68
#Mann= 3 , 0 , 0
       0     .12       0   577.4     .05       0  645.57     .08       0
Bank Sta=577.4,645.57
Exp/Cntr=0.3,0.1

Type RM Length L Ch R = 1 ,7285.619,467.95,466.82,465.54
XS GIS Cut Line= 3
  1333855.159262   807573.434495  1333457.000234   807394.262932
  1333074.767568   807143.422745
#Sta/Elev= 30
       0 1161.56   41.27 1157.99  100.51 1150.45  117.76 1148.71  163.92 1145.16
  211.91 1138.96  227.57 1138.93  255.65 1134.79  352.31 1126.55  355.58 1125.69
  399.44  1119.2  404.77 1118.92  422.88 1114.83  458.56 1110.29  475.17 1110.79
  494.85 1109.58  533.41 1111.32  543.75 1111.19  546.52 1109.67  562.62 1097.59
  574.01 1096.59   584.8 1097.58  603.95 1109.75   610.1 1110.75  614.19 1110.81
   686.6 1130.97  722.81 1138.86  808.35 1153.75  830.21 1158.14  893.81 1166.65
#Mann= 3 , 0 , 0
       0     .12       0  546.52     .05       0  603.95     .12       0
#XS Ineff= 2 , 0
          539.91  1113.3
Permanent Ineff=
       F       F
Bank Sta=546.52,603.95
Exp/Cntr=0.3,0.1

Type RM Length L Ch R = 1 ,6818.802,157.05,162.39,167.73
XS GIS Cut Line= 4
  1333986.551741   807262.870453  1333824.400704   807069.856643
  1333508.760908   806880.637833  1333349.497297   806709.429451
#Sta/Elev= 30
       0 1146.45    23.8 1144.98   92.79 1138.57  101.15 1139.24  131.26 1136.41
  178.03 1133.57  261.29 1124.08  300.38 1123.16     334 1118.59  383.49 1115.09
  387.59 1114.11  445.03 1112.02  491.62 1108.92  521.23 1108.63   534.4 1104.36
  537.43 1102.73  556.57  1096.4  567.97 1095.33  579.32 1096.37  583.75 1099.53
  586.25 1102.66  596.62 1110.32  611.61 1109.71  624.85 1111.46  644.96 1117.25
  671.26 1120.45  714.08 1129.22  794.34 1140.87  830.57 1147.12  853.93 1149.79
#Mann= 3 , 0 , 0
       0     .12       0  537.43     .05       0  586.25     .12       0
Bank Sta=537.43,586.25
Exp/Cntr=0.5,0.3

Type RM Length L Ch R = 1 ,6656.412,74.79,74.79,74.88
BEGIN DESCRIPTION:
Upstream xs of Bridge 37003-0015
END DESCRIPTION:
XS GIS Cut Line= 4
  1334089.156993   806856.438953  1333726.832278   806844.494182
  1333571.550257   806709.120112  1333241.078264   806585.690814
#Sta/Elev= 30
       0    1147      24  1147.6    91.3  1143.3     113  1143.2   141.3  1139.9
   163.8    1136   190.3  1132.4   258.5    1124   292.5  1117.2   322.9  1115.7
   415.6  1107.1   423.7  1105.6   426.7  1104.2   436.3    1102     441  1103.6
     454  1096.3     465  1094.2     475  1094.6     480  1096.3   491.1 1103.48
   500.2  1110.2   518.9  1112.6     529  1112.8   537.6  1116.1   553.2  1120.6
   566.3  1121.2     588  1123.8   713.5  1147.4   782.6    1157   921.3  1170.3
#Mann= 3 , 0 , 0
       0     .12       0     441     .05       0   491.1     .12       0
#XS Ineff= 2 , 0
       0   410.2  1112.9   519.8       0  1112.9
Permanent Ineff=
       F       F
Bank Sta=441,491.1
Exp/Cntr=0.5,0.3

Type RM Length L Ch R = 3 ,6616.563,,,
BEGIN DESCRIPTION:
Lindsay Bebber Road, SR 1317; Bridge : 37003-0015
END DESCRIPTION:
Bridge Culvert--1,0,-1,-1, 0
Deck Dist Width WeirC Skew NumUp NumDn MinLoCord MaxHiCord MaxSubmerge Is_Ogee
29.8,20,2.6,0, 6, 6, , , 0.95, 0, 0,0,,
     300     440     440     490     490     600
    1113    1113    1113    1113    1113    1113
                  1111.2  1111.2
     300     408     408     458     458     600
    1113    1113    1113    1113    1113    1113
                  1111.2  1111.2
Pier Skew, UpSta & Num, DnSta & Num=  ,465, 2 ,433, 2 , 0 , 0 , 0 ,,
       1       1
  1093.2  1111.7
       1       1
  1093.2  1111.7
BR Coef=-1 , 1 , 0 ,, 0 ,,,0.8,0,2,0,
WSPro=,,,, 1 ,,,, 0 ,,,, 0 ,,,,-1 ,-1 ,-1 , 0 , 0 , 0 , 0 , 0
BC Design=,, 0 ,, 0 ,,,,,,