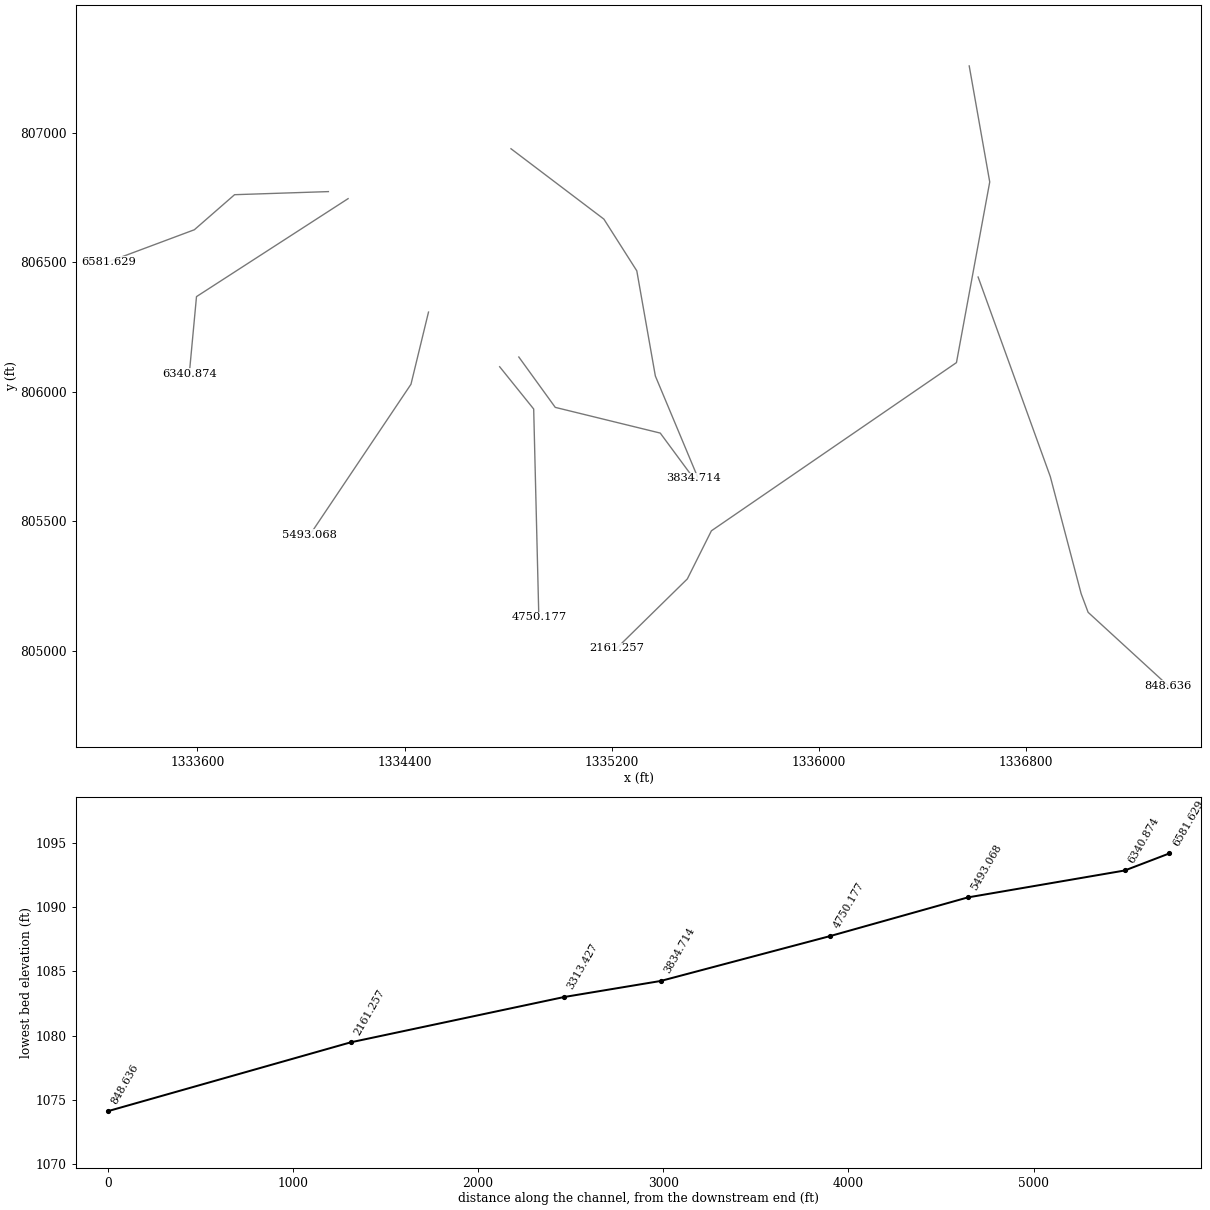
HEC-RAS study LambertCreek.prj: LambertCreek

--- LambertCreek.g01 (geometry) --- (continued)

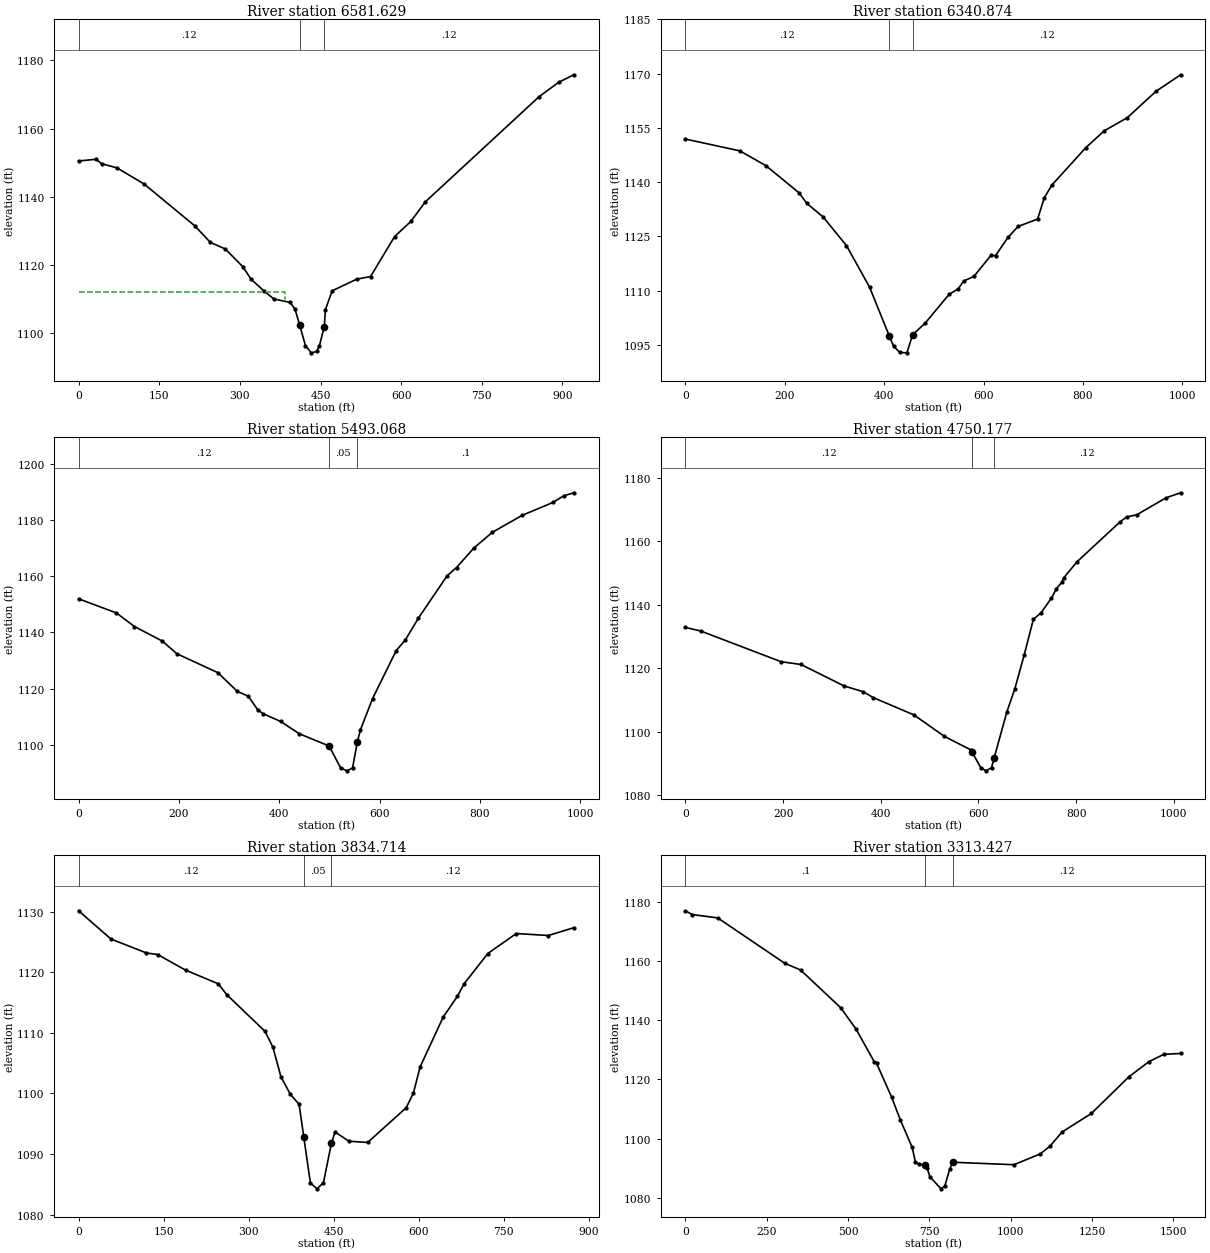
Type RM Length L Ch R = 1 ,6581.629,245.07,240.76,236.34
BEGIN DESCRIPTION:
Down stream xs of Bridge 37003-0015
END DESCRIPTION:
XS GIS Cut Line= 4
  1334105.694069   806772.520176  1333743.369354   806760.575405
  1333588.087333   806625.201336   1333257.61534   806501.772037
#Sta/Elev= 30
       0  1150.5    32.5    1151    42.8  1149.7    71.1  1148.5   122.2  1143.7
   216.6  1131.4   245.1  1126.6   272.7  1124.7   305.3  1119.5   320.9  1115.8
   345.2  1112.3   363.3    1110   393.6    1109   402.6    1107  411.03 1102.46
     422  1096.3     433  1094.2     443  1094.6     448  1096.3     457  1101.9
  459.06 1106.85   471.6  1112.4   517.1  1115.8   543.1  1116.6   587.7  1128.3
   618.2  1132.8   644.9  1138.5   856.8  1169.4   893.1  1173.6   921.3  1175.8
#Mann= 3 , 0 , 0
       0     .12       0  411.03     .05       0     457     .12       0
#XS Ineff= 2 , 0
       0     383  1112.1               0
Permanent Ineff=
       F       F
Bank Sta=411.03,457
Exp/Cntr=0.5,0.3

Type RM Length L Ch R = 1 ,6340.874,835.2,847.81,859.97
XS GIS Cut Line= 3
  1334181.649665   806745.263764  1333596.355894   806367.012687
  1333568.484762   806068.393417
#Sta/Elev= 30
       0  1151.9  109.37 1148.65  162.14 1144.55  228.89 1137.03  244.27 1134.16
  277.01 1130.42  324.07  1122.5  370.58 1111.04     4101097.648  418.95 1094.71
  431.36 1092.97  445.84 1092.87   457.2 1097.84  482.75 1101.09  530.62    1109
   549.2 1110.55  559.98  1112.7  580.69 1113.97  614.95 1119.78  624.14  1119.7
  649.25 1124.75   669.6 1127.77  708.84 1129.81  722.38 1135.68  737.32 1139.14
  805.83 1149.52  843.24  1154.2  889.56 1157.81  947.47 1165.13   996.8 1169.65
#Mann= 3 , 0 , 0
       0     .12       0     410     .05       0   457.2     .12       0
Bank Sta=410,457.2
Exp/Cntr=0.3,0.1

Type RM Length L Ch R = 1 ,5493.068,723.87,742.89,761.16
XS GIS Cut Line= 3
  1334492.213706   806307.288833  1334424.526672   806028.577514
  1334034.330824   805447.265333
#Sta/Elev= 30
       0 1151.92    75.4 1146.88  111.21 1142.07  166.96 1136.88  195.76 1132.39
   277.6 1125.66   315.9 1119.07  338.29 1117.27  357.01 1112.44  368.01 1111.05
  402.84 1108.31   439.7 1103.95  499.12 1099.61   522.1 1091.82  534.48 1090.77
  545.88 1091.77  555.41 1100.99  561.47 1105.27  585.68  1116.4  632.92 1133.52
  651.21 1137.31  677.22 1145.07  734.46 1160.13  753.22 1163.04  787.75 1169.98
  824.51 1175.56  884.27 1181.61  945.36 1186.17  966.41 1188.51  986.94  1189.6
#Mann= 3 , 0 , 0
       0     .12       0  499.12     .05       0  555.41      .1       0
Bank Sta=499.12,555.41
Exp/Cntr=0.3,0.1

Type RM Length L Ch R = 1 ,4750.177,873.31,915.46,953.76
XS GIS Cut Line= 3
  1334766.943435   806096.264549  1334898.335914   805933.019347
  1334918.243866   805128.738111
#Sta/Elev= 30
       0 1132.91   31.57 1131.77  195.75 1122.12  236.76 1121.24  324.39 1114.52
  364.52 1112.63  384.51 1110.83  467.91 1105.37  530.43  1098.6  585.09  1094.3
  586.98 1093.68  604.67 1088.77  615.63 1087.76  626.85 1088.77  632.18 1091.83
  658.28 1106.34  674.57  1113.6  693.78 1124.28  712.53 1135.49  728.34 1137.53
  749.54 1142.17   759.7 1145.07  770.64 1147.12  775.06 1148.59   801.6 1153.54
  889.18 1166.02  903.37 1167.68  924.38 1168.38   984.4 1173.74 1014.08  1175.3
#Mann= 3 , 0 , 0
       0     .12       0  586.98     .05       0  632.18     .12       0
Bank Sta=586.98,632.18
Exp/Cntr=0.3,0.1

Type RM Length L Ch R = 1 ,3834.714,555.57,521.29,484.25
XS GIS Cut Line= 4
  1334840.960949   806133.827954   1334981.63117   805939.372085
  1335387.092372    805840.07545  1335515.350485   805666.306396
#Sta/Elev= 30
       0 1130.12   56.89 1125.47  119.36 1123.17  139.51  1122.9  188.66 1120.33
  246.27 1118.08  261.11  1116.3  328.69 1110.24  342.65 1107.62  356.79 1102.76
  373.13 1099.89  388.82 1098.19     3971092.867  408.73 1085.25  420.25 1084.26
  431.76 1085.26  445.92  1091.8  452.25 1093.64  476.65 1092.11  509.74 1091.91
  577.77 1097.64  590.43 1100.05  602.35 1104.39  643.05 1112.61  668.05 1116.01
  679.68 1118.06  721.65 1123.07  771.92 1126.37  828.31 1126.04  873.42 1127.33
#Mann= 3 , 0 , 0
       0     .12       0     397     .05       0  445.92     .12       0
Bank Sta=397,445.92
Exp/Cntr=0.3,0.1

Type RM Length L Ch R = 1 ,3313.427,1182.97,1152.17,1112.85
XS GIS Cut Line= 5
  1334810.733757   806937.975592  1335169.377327    806666.30875
  1335296.494942   806466.552444  1335368.163567   806060.430236
  1335531.408768   805670.234389
#Sta/Elev= 30
       0 1176.91    20.9 1175.64    99.4  1174.5  304.93 1159.21  353.85 1156.92
  477.84 1144.11  524.39 1136.95   580.2 1125.97  587.34 1125.46  633.64 1114.01
  660.38 1106.35  696.81 1097.04  706.75 1092.15  717.73 1091.31  737.85 1091.06
  742.52 1090.18  751.33 1087.11  785.79 1083.01  797.26 1084.01  812.15 1089.61
  821.34 1091.99 1009.87 1091.16 1091.09 1094.84 1120.94 1097.47 1157.24 1102.17
 1247.72 1108.47 1362.92 1120.83 1425.11    1126    1470 1128.42 1522.06 1128.73
#Mann= 3 , 0 , 0
       0      .1       0  737.85     .05       0  821.34     .12       0
Bank Sta=737.85,821.34
Exp/Cntr=0.3,0.1

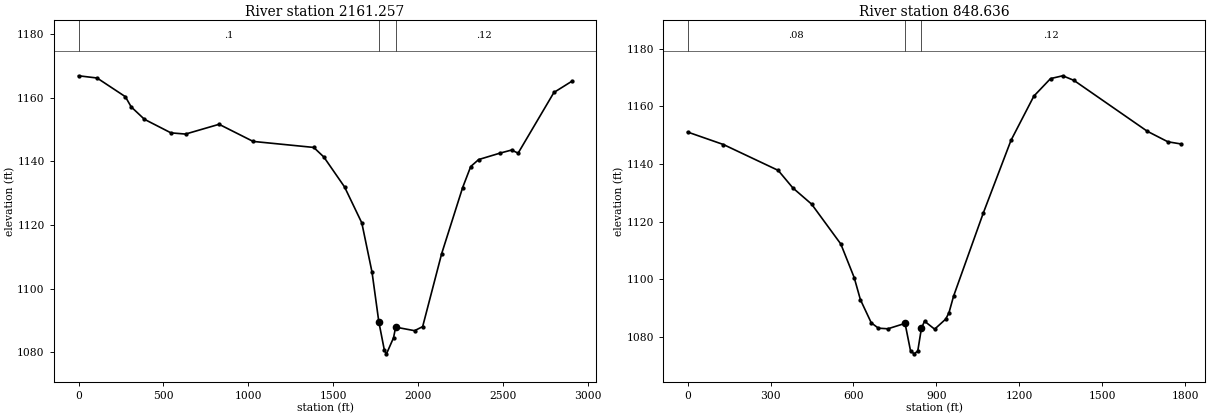
Type RM Length L Ch R = 1 ,2161.257,1270.36,1312.62,1347.44
XS GIS Cut Line= 6
  1336580.060433   807257.795583  1336659.293633   806809.704068
  1336530.787881    806112.19091   1335584.49178   805462.676999
  1335491.640829   805276.975049  1335218.246337    805008.73892
#Sta/Elev= 30
       0 1166.87   109.3 1166.17  275.92  1160.3  310.25  1157.1  388.11  1153.2
  544.46 1148.93  630.32 1148.55  828.11 1151.62 1028.64 1146.24 1385.79 1144.35
 1445.31 1141.34 1567.42 1131.92 1668.92 1120.63 1729.24 1105.11  1769.2 1089.53
 1802.06 1080.55 1814.27 1079.48 1855.67 1084.51 1868.39 1087.87 1979.65 1086.76
 2027.33 1088.03 2139.43 1110.98 2262.88 1131.73 2310.52 1138.35 2357.21 1140.54
  2482.3 1142.55 2551.27 1143.53 2589.72 1142.55  2800.7 1161.63 2905.48 1165.12
#Mann= 3 , 0 , 0
       0      .1       0  1769.2     .05       0 1868.39     .12       0
Bank Sta=1769.2,1868.39
Exp/Cntr=0.3,0.1

Type RM Length L Ch R = 1 ,848.636 ,860.41,848.64,837.39
XS GIS Cut Line= 5
  1336614.401277   806442.662903  1336893.213692   805671.928604
  1337012.235692   805219.935453  1337039.156829   805148.015371
  1337348.660047   804864.304107
#Sta/Elev= 30
       0 1151.06  129.72 1146.72   327.8 1137.75  380.87 1131.66   448.7 1126.04
  554.25 1112.21  602.63 1100.57   625.1  1092.9   664.5 1084.85  690.35 1083.01
  724.62  1082.8  786.57 1084.68   806.5  1075.1  819.61 1074.11   832.6 1075.11
  845.69 1082.93  856.96 1085.44  893.55 1082.67  933.61 1086.16  945.48 1088.39
  962.02 1094.11 1069.08 1122.84 1169.67 1148.16 1252.46 1163.52 1312.72 1169.59
 1356.91 1170.57 1397.21 1168.98 1662.72 1151.32  1737.1 1147.67 1783.67 1146.93
#Mann= 3 , 0 , 0
       0     .08       0  786.57     .05       0  845.69     .12       0
Bank Sta=786.57,845.69
Exp/Cntr=0.3,0.1

Chan Stop Cuts=-1
Use User Specified Reach Order=0
User Specified Reach Order=LambertCreek    ,Main